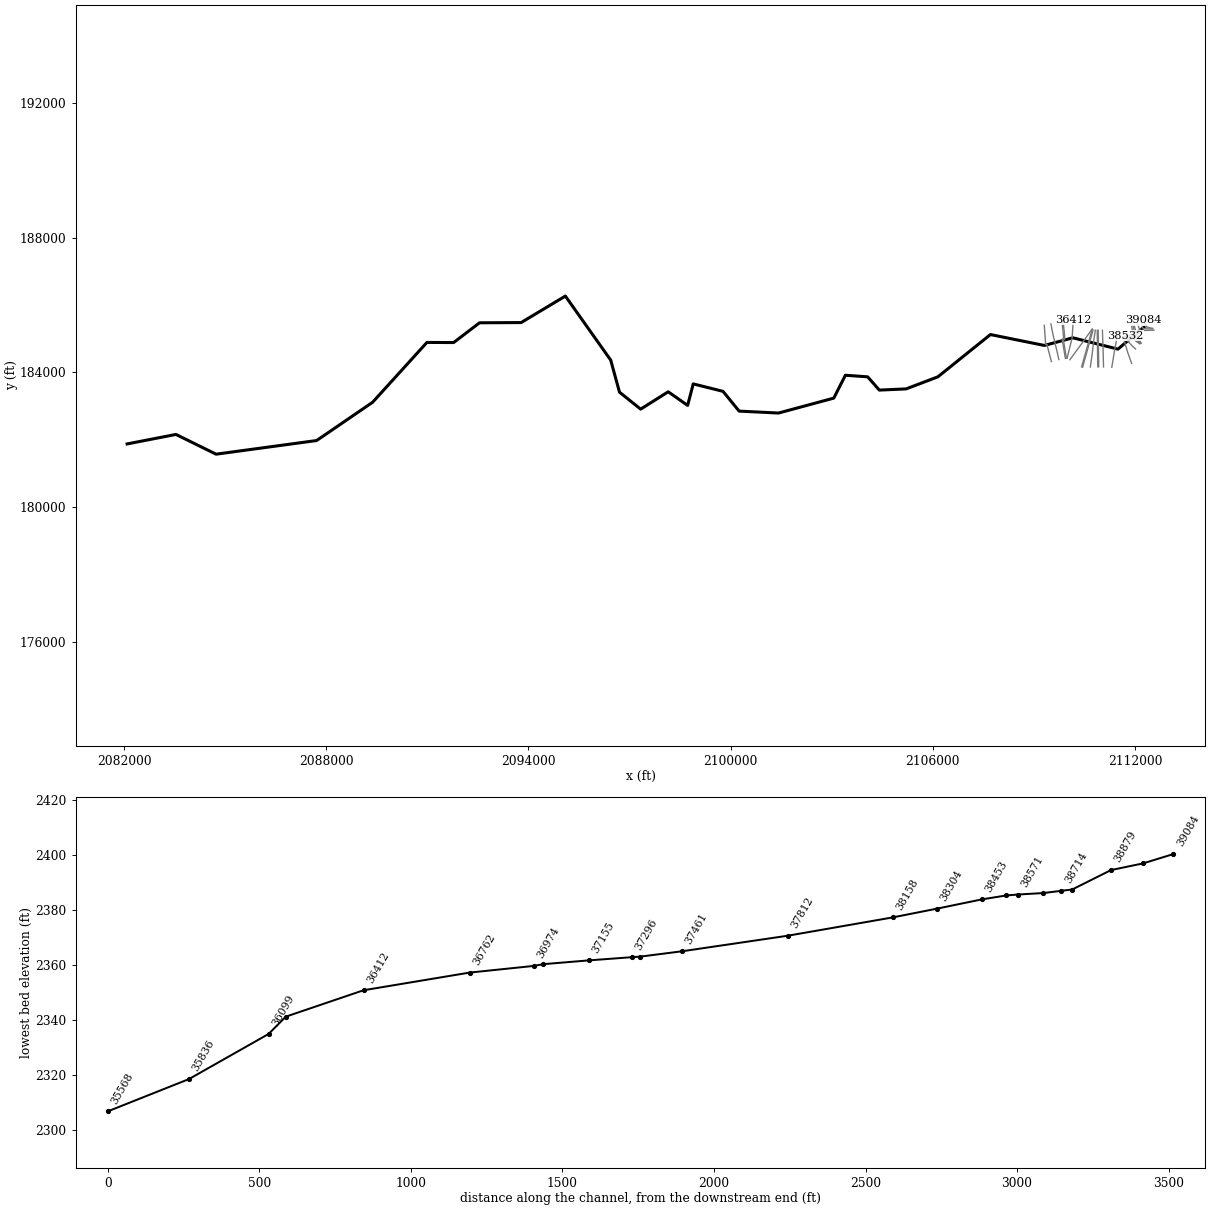
--- DRPLKCR.prj (project) ---

Proj Title=DRPLKCR
Current Plan=p01
Default Exp/Contr=0,0
English Units
Geom File=g01
Flow File=f01
Plan File=p01
BEGIN DESCRIPTION:
Stream Name: Dropping Lick Creek
Flood Zone: Approximate
Monroe County, West Virginia
HEC-RAS Version: 5.0.7
Vertical Datum: NAVD88
Projection: NAD 1983 StatePlane West Virginia S FIPS 4702 (US Feet)
LiDAR: 2016, 1-meter
Land Use: 2016 NLCD
Hydrology Method:
Regression.
Model Notes:
END DESCRIPTION:
DSS File=dss
DSS Export Rating Curves= 0
DSS Export Rating Curve Sorted= 0
DSS Export Volume Flow Curves= 0
DXF OffsetX= 0
DXF OffsetY= 0
DXF ScaleX= 0
DXF ScaleY= 0

--- DRPLKCR.p01 (plan) ---

Plan Title=Floodplain
Program Version=5.07
Short Identifier=Floodplain
Geom File=g01
Flow File=f01
Subcritical Flow
K Sum by GR= 0
Std Step Tol= 0.01
Critical Tol= 0.01
Num of Std Step Trials= 20
Max Error Tol= 0.3
Flow Tol Ratio= 0.001
Split Flow NTrial= 30
Split Flow Tol= 0.02
Split Flow Ratio= 0.02
Log Output Level= 0
Friction Slope Method= 1
Unsteady Friction Slope Method= 2
Unsteady Bridges Friction Slope Method= 1
Parabolic Critical Depth
Global Vel Dist= 0 , 0 , 0
Global Log Level= 0
CheckData=True
Encroach Param=-1 ,0,0, 0
Computation Interval=0.1SEC
Output Interval=1MIN
Instantaneous Interval=Max Profile
Mapping Interval=1HOUR
Computation Time Step Use Courant=        0
Computation Time Step Use Time Series=    0
Computation Time Step Count To Double=0
Computation Time Step Max Doubling=0
Computation Time Step Max Halving=0
Computation Time Step Residence Courant=0
Run HTab= 0
Run UNet= 0
Run Sediment= 0
Run PostProcess= 0
Run WQNet= 0
Run RASMapper=-1
UNET Theta= 0
UNET Theta Warmup= 0
UNET ZTol= 0
UNET ZSATol= 0
UNET MxIter= 0
UNET Max Iter WO Improvement= 0
UNET MaxInSteps= 0
UNET DtIC= 0
UNET DtMin= 0
UNET MaxCRTS= 0
UNET WFStab= 0
UNET SFStab= 0
UNET WFX= 1
UNET SFX= 1
UNET 1D Methodology=Finite Difference
UNET DSS MLevel= 1
UNET Pardiso=0
UNET DZMax Abort= 0
UNET Use Existing IB Tables= 0
UNET Froude Reduction=False
UNET Froude Limit= 0
UNET Froude Power= 0
UNET D1 Cores= 0
UNET D2 Coriolis=0
UNET D2 Cores= 0
UNET D2 Theta= 1
UNET D2 Theta Warmup= 1
UNET D2 Z Tol= 0.01
UNET D2 Volume Tol= 0.01
UNET D2 Max Iterations= 20
UNET D2 Equation= 0
UNET D2 RampUpFraction=0.1
UNET D2 TimeSlices= 1
UNET D2 BCVolumeCheck=0
UNET D1D2 MaxIter= 0
UNET D1D2 ZTol=0.01
UNET D1D2 QTol=0.1
UNET D1D2 MinQTol=1
DSS File=dss
Write IC File= 0
Write IC File at Fixed DateTime=0
Write IC File at Sim End=0
Echo Input=False
Echo Parameters=False
Echo Output=False
Write Detailed= 0
HDF Write Warmup=0
HDF Write Time Slices=0
HDF Flush=0
HDF Face Node Velocities=0
HDF Compression= 1
HDF Chunk Size= 1
HDF Spatial Parts= 1
HDF Use Max Rows=0
HDF Fixed Rows= 1
Calibration Method= 0
Calibration Iterations= 20
Calibration Max Change=0.05
Calibration Tolerance=0.2
Calibration Maximum=1.5
Calibration Minimum=0.5
Calibration Optimization Method= 1
WQ AD Non Conservative
WQ ULTIMATE=-1
WQ Max Comp Step=1HOUR
WQ Output Interval=15MIN
WQ Output Selected Increments= 0
WQ Output face flow=0
WQ Output face velocity=0
WQ Output face area=0
WQ Output face dispersion=0
WQ Output cell volume=0
WQ Output cell surface area=0
WQ Output cell continuity=0
WQ Output cumulative cell continuity=0
WQ Output face conc=0
WQ Output face dconc_dx=0
WQ Output face courant=0
WQ Output face peclet=0
WQ Output face adv mass=0
WQ Output face disp mass=0
WQ Output cell mass=0
WQ Output cell source sink temp=0
WQ Output nsm pathways=0
WQ Output nsm derived pathways=0
WQ Output MaxMinRange=-1
WQ Daily Max Min Mean=-1
WQ Daily Range=0
WQ Daily Time=0
WQ Create Restart=0
WQ Fixed Restart=0
WQ System Summary=0
WQ Write To DSS=0
WQ Use Fixed Temperature=0
Sorting and Armoring Iterations= 10
XS Update Threshold= 0.02
Bed Roughness Predictor= 0
Hydraulics Update Threshold= 0.02
Energy Slope Method= 1
Volume Change Method= 1
Sediment Retention Method= 0
XS Weighting Method= 0
Number of US Weighted Cross Sections= 1
Number of DS Weighted Cross Sections= 1
Upstream XS Weight=0
Main XS Weight=1
Downstream XS Weight=0
Number of DS XS's Weighted with US Boundary= 1
Upstream Boundary Weight= 1
Weight of XSs Associated with US Boundary= 0
Number of US XS's Weighted with DS Boundary= 1
Downstream Boundary Weight= 0.5
Weight of XSs Associated with DS Boundary= 0.5
Percentile Method= 0
Sediment Output Level= 3
Mass or Volume Output= 0
Output Increment Type= 1
Profile and TS Output Increment= 1
XS Output Flag= 0
XS Output Increment= 10
Write Gradation File= 0
Read Gradation Hotstart= 0
Write HDF5 File= 1
Write Binary Output= 1
Write DSS Sediment File= 0
SV Curve= 0
Specific Gage Flag= 0

--- DRPLKCR.f01 (steady flow) ---

Flow Title=Flow
Program Version=5.07
Number of Profiles= 6
Profile Names=01pct,10pct,04pct,02pct,0_2pct,01plus
River Rch & RM=DRPLKCR,Main            ,39084
     550     290     386     465     769     813
River Rch & RM=DRPLKCR,Main            ,37005
     573     303     402     485     800     847
River Rch & RM=DRPLKCR,Main            ,36412
     626     332     440     530     872     925
River Rch & RM=DRPLKCR,Main            ,33969
     692     368     488     587     963    1020
River Rch & RM=DRPLKCR,Main            ,31070
    1050     567     745     891    1450    1550
River Rch & RM=DRPLKCR,Main            ,28359
    1270     694     909    1090    1750    1880
River Rch & RM=DRPLKCR,Main            ,27956
    1350     738     966    1150    1860    2000
River Rch & RM=DRPLKCR,Main            ,23458
    1790     990    1290    1530    2450    2650
River Rch & RM=DRPLKCR,Main            ,19955
    1920    1060    1380    1640    2620    2830
River Rch & RM=DRPLKCR,Main            ,12951
    2130    1180    1530    1820    2900    3140
River Rch & RM=DRPLKCR,Main            ,8568
    2320    1300    1680    1990    3160    3440
River Rch & RM=DRPLKCR,Main            ,934
    2330    1300    1680    2000    3170    3440
River Rch & RM=DRPLKCR,Main            ,0
    3730    2120    2720    3210    5030    5510
Boundary for River Rch & Prof#=DRPLKCR,Main            , 1
Up Type= 0
Dn Type= 1
Dn Known WS=1807.751
Boundary for River Rch & Prof#=DRPLKCR,Main            , 2
Up Type= 0
Dn Type= 1
Dn Known WS=1806.125
Boundary for River Rch & Prof#=DRPLKCR,Main            , 3
Up Type= 0
Dn Type= 1
Dn Known WS=1807.067
Boundary for River Rch & Prof#=DRPLKCR,Main            , 4
Up Type= 0
Dn Type= 1
Dn Known WS=1807.447
Boundary for River Rch & Prof#=DRPLKCR,Main            , 5
Up Type= 0
Dn Type= 1
Dn Known WS=1808.816
Boundary for River Rch & Prof#=DRPLKCR,Main            , 6
Up Type= 0
Dn Type= 1
Dn Known WS=1809.173
DSS Import GetInterval= 0
DSS Import GetPeak= 0
DSS Import FillOption= 0

--- DRPLKCR.g01 (geometry) ---

Geom Title=Geometry
Program Version=5.07

River Reach=DRPLKCR         ,Main
Reach XY= 30
2112316.12009516185383.8888099872111495.23989873 184689.97201959
2110156.81200004185026.4910000062109312.02000003184798.886000005
2107711.11200004185122.7750000272106150.74600001183867.534999995
2105208.35600002183509.799000024     2104412.935183473.977000031
2104067.44900005183867.6399999912103406.85800004183914.949000015
     2103061.806183236.1300000352101422.04900002182792.987000017
2100252.77800005182850.2789999972099774.82700001183436.824000021
2098891.14700003183658.1780000082098724.48000004183019.289000041
2098148.34400005183423.7470000062097330.50600005182908.837000042
     2096702.584183412.4460000142096442.36200004184363.039000043
2095096.00799999186264.949000023     2093784.376185478.491000023
     2092549.133185471.5460000312091780.03600006184885.175000018
2090987.24000001 184888.647000032089376.12900004183113.473000011
     2087714.671181977.1889999952084729.52599999181572.206000022
     2083539.422 182158.144000022082090.73099516181876.368496227

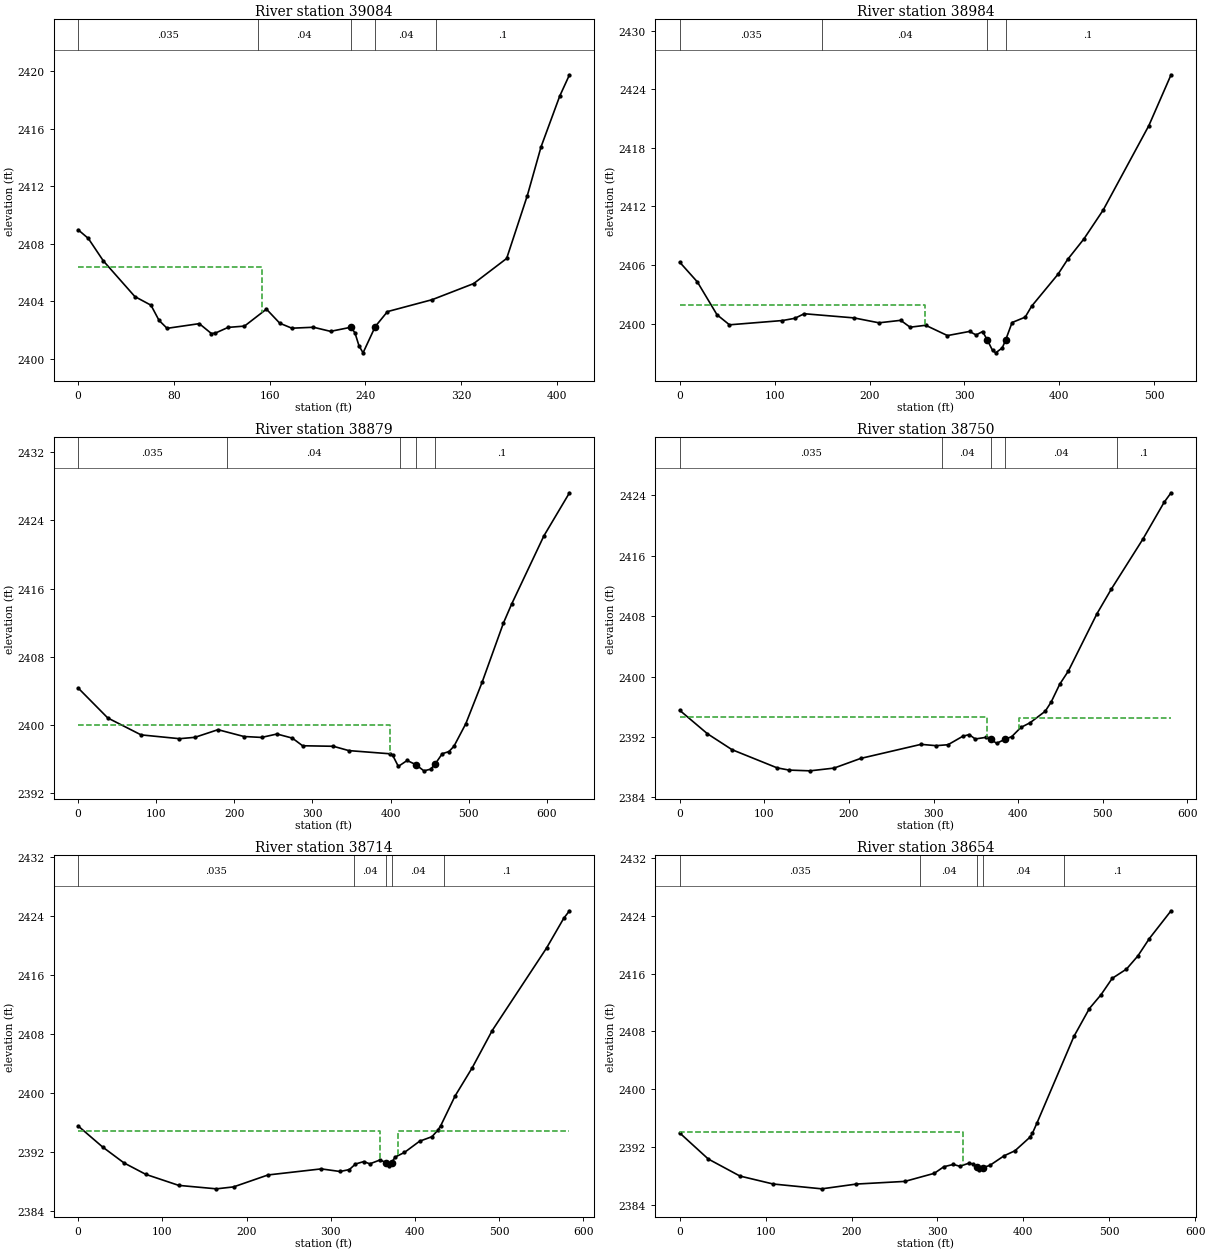
Type RM Length L Ch R = 1 ,39084   ,97.1,100.3,99.9
XS GIS Cut Line= 4
2112523.23171169185306.4061300442112319.24296974185352.503581569
 2112298.5977548185429.3496593972112260.74819407185545.192254332
#Sta/Elev= 30
       02408.979   8.4912408.377  21.0152406.818   47.39 2404.33  60.8442403.731
  67.5712402.675  74.2982402.121 101.2072402.447 111.2982401.761 114.661 2401.79
 125.2712402.186 138.9882402.276 157.3342403.457 168.4782402.476 178.569 2402.13
 196.6032402.196 210.899 2401.91 227.8852402.195 231.2822401.811 234.6792400.904
 238.0762400.415 248.2682402.246 258.4592403.285 295.7742404.114 330.4572405.234
 358.0692406.984 375.3272411.357 386.8272414.756 402.4362418.289 410.5732419.769
#Mann= 5 ,-1 , 0
       0    .035       0     150     .04       0 227.885    .045       0
 248.268     .04       0   298.7      .1       0
#XS Ineff= 2 , 0
           153.3 2406.36
Permanent Ineff=
       F       F
Bank Sta=227.885,248.268
XS Rating Curve= 0 ,0
Exp/Cntr(USF)=0,0
Exp/Cntr=0.3,0.1

Type RM Length L Ch R = 1 ,38984   ,99.9,105.5,106.4
XS GIS Cut Line= 4
2112529.39341627185289.1571804022112240.10297914 185296.30271868
2112202.25341841    185413.292272112175.87342155185515.371388309
#Sta/Elev= 30
       02406.284  18.5612404.268  39.2752400.905  52.4022399.873 108.1932400.311
 121.321 2400.54 131.1662401.008 183.6752400.581  209.932400.078 232.9032400.333
 242.7452399.628 259.1582399.826  282.132398.771 305.4132399.195  312.312398.833
 319.2062399.188  324.32 2398.28 329.6092397.261 332.9992397.003 339.8962397.511
 343.3442398.292 350.2412400.106 364.0342400.658  370.93 2401.79 398.5162405.038
 408.8612406.578 425.8642408.659 446.1962411.617 494.355 2420.27 517.7712425.479
#Mann= 4 ,-1 , 0
       0    .035       0     150     .04       0  324.32    .045       0
 343.344      .1       0
#XS Ineff= 2 , 0
          258.74 2401.95
Permanent Ineff=
       F       F
Bank Sta=324.32,343.344
XS Rating Curve= 0 ,0
Exp/Cntr(USF)=0,0
Exp/Cntr=0.3,0.1

Type RM Length L Ch R = 1 ,38879   ,129.4,128.3,127.4
XS GIS Cut Line= 4
2112567.32326394185253.9316010122112165.04615327 185239.47102978
2112119.67255866185321.5357591612112078.38212878185447.700961565
#Sta/Elev= 30
       02404.316  37.9132400.796  80.525 2398.81 129.7212398.363 149.4672398.522
 179.0142399.419  212.212398.619 234.8242398.511 254.5222398.912  274.222398.429
 287.3512397.532 326.747 2397.47 346.4452396.963 398.7452396.592 402.5372396.441
 409.9312395.106 421.1782395.802 432.4252395.309 442.6372394.585 451.1692394.776
  456.61 2395.33 466.1652396.596 474.6872396.847 481.1612397.476  496.312400.122
 517.229    2405 544.4972411.951 554.8532414.147 596.2782422.188  629.062427.253
#Mann= 5 ,-1 , 0
       0    .035       0     190     .04       0  412.54      .1       0
 432.425    .045       0  456.61      .1       0
#XS Ineff= 2 , 0
          399.14 2399.98
Permanent Ineff=
       F       F
Bank Sta=432.425,456.61
XS Rating Curve= 0 ,0
Exp/Cntr(USF)=0,0
Exp/Cntr=0.5,0.3

Type RM Length L Ch R = 1 ,38750   ,35.4,35.8,37.1
XS GIS Cut Line= 4
2112180.36033666 184860.686522172112055.44300107185165.549690734
2112011.85865842185263.0409835012111976.30301047185402.969662531
#Sta/Elev= 30
       02395.522  32.7152392.419  61.7852390.307 114.9692387.903 129.1512387.603
  153.972387.503 182.3352387.867 213.7982389.148 285.1562391.013 302.8842390.838
 317.0662390.963 334.4562392.082 342.0542392.306 349.2422391.725 361.775 2391.94
   367.52391.722 374.3982391.149 384.1262391.667 392.3672392.038 403.1482393.254
  413.932393.868 431.8982395.396 438.9212396.614 449.0772398.985 459.2322400.722
 493.0832408.327 510.0082411.583 547.2442418.191 572.4352423.088 580.629 2424.35
#Mann= 5 ,-1 , 0
       0    .035       0     310     .04       0   367.5    .045       0
 384.126     .04       0  516.25      .1       0
#XS Ineff= 2 , 0
          362.93 2394.63  400.43         2394.54
Permanent Ineff=
       F       F
Bank Sta=367.5,384.126
XS Rating Curve= 0 ,0
Exp/Cntr(USF)=0,0
Exp/Cntr=0.5,0.3

Type RM Length L Ch R = 1 ,38714   ,59.7,60.1,60.5
XS GIS Cut Line= 4
2112179.02218624184860.0780101122112029.06300421185140.316650254
2111983.18474879185236.6609866352111941.89431891185390.353142291
#Sta/Elev= 30
       02395.554  29.0242392.706   54.372390.549  80.4172388.988 119.4232387.498
 164.3082387.028 184.6062387.291 225.5372388.911 288.7952389.734 311.121 2389.38
  322.182389.641 329.4482390.396 339.1592390.721 346.5442390.421 358.518 2390.94
 365.786  2390.6  369.422390.116  372.26  2390.6 376.6872391.348 387.5892391.962
 405.6222393.488 420.293  2394.1 427.3652394.995 430.7622395.601 447.748 2399.62
 468.1312403.449 491.9112408.504 556.4572419.692  576.842423.721 583.6912424.744
#Mann= 5 ,-1 , 0
       0    .035       0  327.84     .04       0 365.786    .045       0
  372.26     .04       0  434.55      .1       0
#XS Ineff= 2 , 0
          358.27 2394.85  380.39         2394.93
Permanent Ineff=
       F       F
Bank Sta=365.786,372.26
XS Rating Curve= 0 ,0
Exp/Cntr(USF)=0,0
Exp/Cntr=0.5,0.3

Type RM Length L Ch R = 1 ,38654   ,53.5,82.9,105.4
XS GIS Cut Line= 4
2112147.15424145184863.3472752042111982.41242735185103.574479364
2111929.38247794185206.5866799542111903.17227305185369.333766093
#Sta/Elev= 30
       0 2393.94    33.2 2390.34    70.1 2387.98   108.7 2386.88   165.4 2386.21
   205.5 2386.87   262.1 2387.24   296.4 2388.36   307.5 2389.27   318.6 2389.59
     326 2389.33   336.7 2389.76   341.6 2389.64   345.6 2389.21   348.9 2388.84
 352.9112389.149   361.1 2389.46   377.6 2390.78   390.3 2391.48   407.4 2393.32
   410.5 2393.87     416 2395.35   458.9  2407.3   476.9 2411.16   490.4 2413.06
   503.5 2415.34   520.1 2416.62   533.3 2418.43   546.7 2420.84     572 2424.69
#Mann= 5 ,-1 , 0
       0    .035       0     280     .04       0   345.6    .045       0
 352.911     .04       0  447.15      .1       0
#XS Ineff= 2 , 0
          330.09 2394.02
Permanent Ineff=
       F       F
Bank Sta=345.6,352.911
XS Rating Curve= 0 ,0
Exp/Cntr(USF)=0,0
Exp/Cntr=0.5,0.3

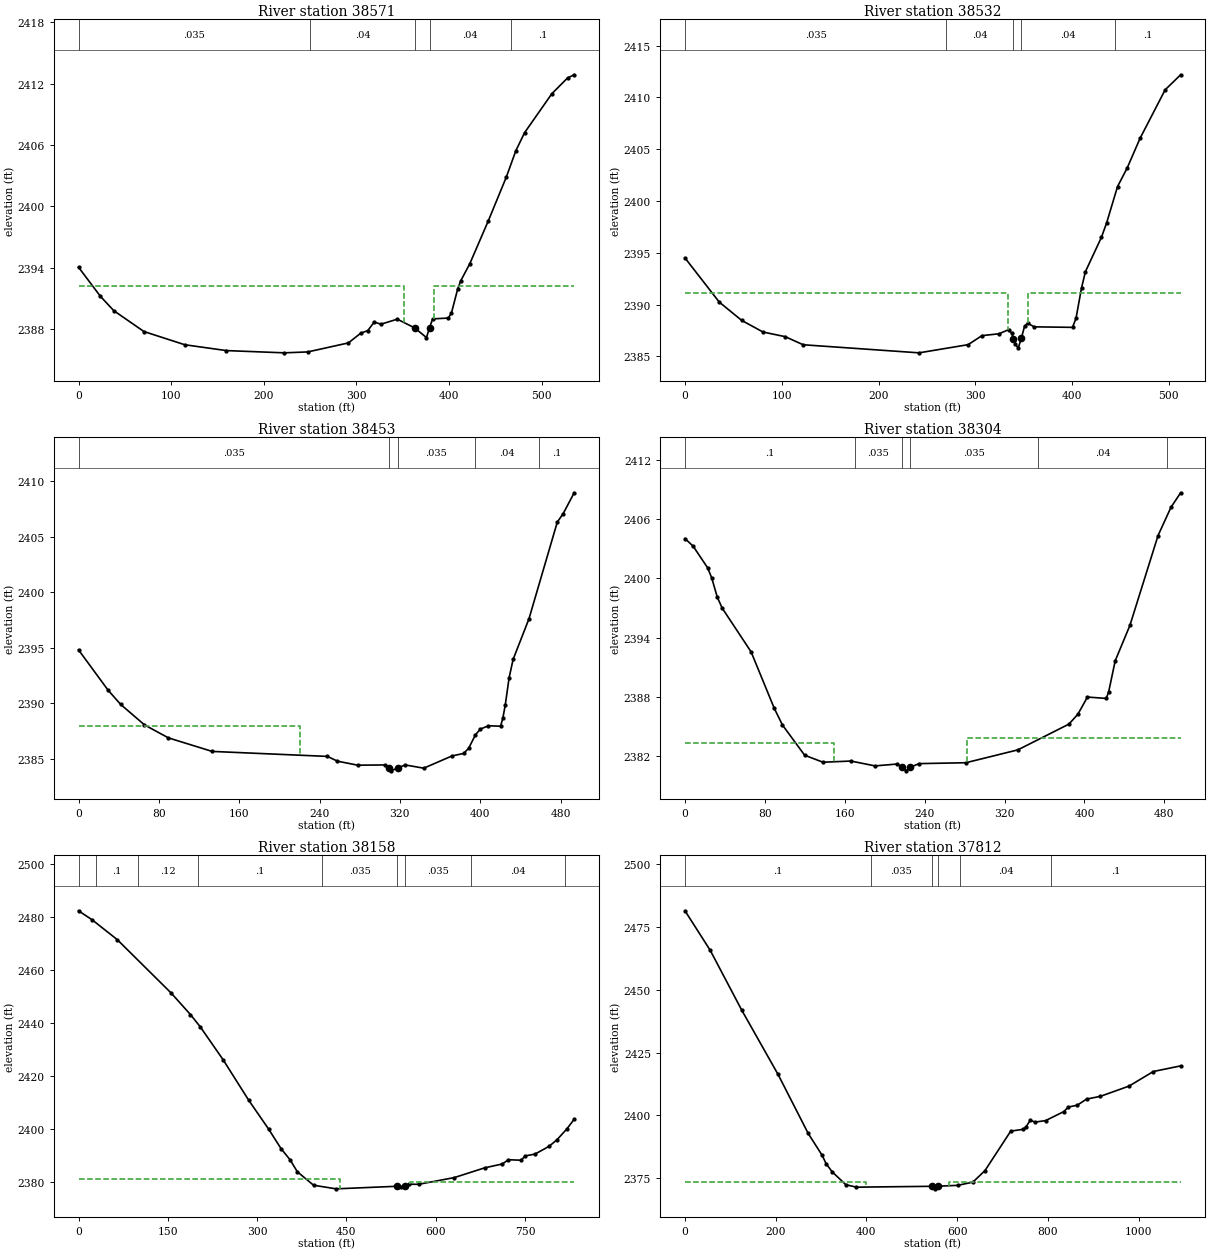
Type RM Length L Ch R = 1 ,38571   ,47.2,39,36
XS GIS Cut Line= 4
2112142.52058933184860.8785542642111913.53444708185118.203430927
2111852.58048223185103.5744793642111724.57715605185098.698162176
#Sta/Elev= 30
       0 2394.05    23.6 2391.21    38.1  2389.8    70.7 2387.76   114.8 2386.47
   159.7  2385.9   222.3 2385.68   247.6 2385.77   291.4 2386.65   304.6 2387.59
   312.4 2387.86   319.3 2388.69   326.6 2388.48   344.2 2388.97 363.1072388.111
   375.7 2387.17   379.1 2388.15   382.4    2389   399.3 2389.08   402.7 2389.58
   409.4 2391.91   412.6  2392.7   422.5 2394.39   442.2 2398.52   461.9 2402.85
   472.2 2405.43   481.6 2407.19   511.1 2411.01   528.2 2412.56   535.2 2412.86
#Mann= 5 ,-1 , 0
       0    .035       0     250     .04       0 363.107    .045       0
   379.1     .04       0  467.14      .1       0
#XS Ineff= 2 , 0
          351.58 2392.22  384.24         2392.22
Permanent Ineff=
       F       F
Bank Sta=363.107,379.1
XS Rating Curve= 0 ,0
Exp/Cntr(USF)=0,0
Exp/Cntr=0.5,0.3

Type RM Length L Ch R = 1 ,38532   ,84,79.6,75.9
XS GIS Cut Line= 4
2112140.68356419184856.2936235122111918.41076426185075.535655534
2111856.23772012185070.6593383472111720.31037851185091.383686394
#Sta/Elev= 30
       0  2394.5    35.4 2390.24    58.6 2388.47    80.6 2387.35   103.6  2386.9
   122.1 2386.12   241.8 2385.34   292.6 2386.13   306.8    2387   324.5 2387.18
   334.4 2387.58   337.7 2387.21  339.28 2386.72     341 2386.22   344.3  2385.8
   347.5 2386.74   350.8 2387.89   354.1  2388.2   360.7 2387.85   400.4  2387.8
     404 2388.67   409.7  2391.6   413.7 2393.17   430.3  2396.5   435.7  2397.9
   446.9 2401.39   456.8 2403.17   470.2 2406.05   496.1 2410.73   512.1 2412.18
#Mann= 5 ,-1 , 0
       0    .035       0     270     .04       0  339.28    .045       0
   347.5     .04       0  444.57      .1       0
#XS Ineff= 2 , 0
          333.52 2391.09  354.15         2391.09
Permanent Ineff=
       F       F
Bank Sta=339.28,347.5
XS Rating Curve= 0 ,0
Exp/Cntr(USF)=0,0
Exp/Cntr=0.5,0.3

Type RM Length L Ch R = 1 ,38453   ,158,148.7,139.8
XS GIS Cut Line= 4
2112137.65739765184852.5251854612111951.93544493184978.618851429
2111772.12124863185016.4103096342111702.02418906 185065.17348151
#Sta/Elev= 30
       0 2394.82    29.5 2391.18    41.9 2389.91    65.7 2388.06    89.5 2386.89
   133.1 2385.67   247.9 2385.22   257.9 2384.79     278 2384.43   304.8 2384.45
   308.8 2384.21   311.5 2383.92 318.3052384.205   325.4 2384.45   343.8 2384.16
   371.9 2385.26   383.6 2385.49   388.6 2385.96   395.3 2387.17   400.2 2387.68
   408.2 2387.98   420.3 2387.94   422.6 2388.67     425 2389.86   428.8  2392.3
   432.8 2393.96   448.6 2397.62   476.8 2406.33   482.7  2407.1   493.6 2408.97
#Mann= 5 ,-1 , 0
       0    .035       0   308.8    .045       0 318.305    .035       0
  394.48     .04       0  458.22      .1       0
#XS Ineff= 2 , 0
          220.92 2387.95
Permanent Ineff=
       F       F
Bank Sta=308.8,318.305
XS Rating Curve= 0 ,0
Exp/Cntr(USF)=0,0
Exp/Cntr=0.3,0.1

Type RM Length L Ch R = 1 ,38304   ,153.3,146.5,140.2
XS GIS Cut Line= 4
2112017.15618732184695.7924545432111889.76240079184813.433606696
2111729.45347324184991.4191840472111684.34753926 185061.51624362
#Sta/Elev= 30
       0 2404.02     8.2 2403.25    22.7 2401.06    26.8 2400.04    32.3 2398.11
    37.2    2397    66.2 2392.57    89.4 2386.86    97.5 2385.19   119.8 2382.12
   138.2 2381.41   166.1 2381.53   190.3 2381.04   212.7 2381.23   217.2 2380.93
   221.2 2380.54   225.6 2380.91   234.5 2381.27   281.3 2381.36   333.3 2382.66
   384.4 2385.26   393.4 2386.26     403    2388   421.8 2387.86   424.2 2388.51
   430.8 2391.67   445.5 2395.24   473.7 2404.33   486.6 2407.18   496.3 2408.65
#Mann= 6 ,-1 , 0
       0      .1       0     170    .035       0   217.2    .045       0
   225.6    .035       0   353.4     .04       0  482.94      .1       0
#XS Ineff= 2 ,-1
       0     149 2383.31  282.23 496.295 2383.91
Permanent Ineff=
       F       F
Bank Sta=217.2,225.6
XS Rating Curve= 0 ,0
Exp/Cntr(USF)=0,0
Exp/Cntr=0.3,0.1

Type RM Length L Ch R = 1 ,38158   ,352,345.6,335.7
XS GIS Cut Line= 4
2111901.79848122184266.1540194042111787.41383941184585.567736171
2111679.50379996184948.145468718 2111656.6034647185060.953347025
#Sta/Elev= 30
       0 2482.27    23.1 2478.83      65  2471.4   155.6 2451.24   188.1  2443.1
   204.4 2438.52   242.7 2426.14   285.6 2410.89   319.4 2399.88   340.2 2392.53
   355.4 2388.31   367.6 2383.79   394.9  2378.7   432.7 2377.34 535.3582378.311
   542.2 2378.01  549.052378.386   555.8 2379.07   571.7 2379.06   631.2 2381.58
   682.5 2385.27     712 2386.73   722.3 2388.32   743.6 2388.14   750.3 2389.75
   766.8 2390.45   790.4 2393.36   803.8 2395.85   820.6    2400   832.7  2403.6
#Mann= 9 ,-1 , 0
       0     .12       0      30      .1       0     100     .12       0
     200      .1       0  409.28    .035       0 535.358    .045       0
  549.05    .035       0  659.28     .04       0  817.57      .1       0
#XS Ineff= 2 ,-1
       0  438.83 2381.16   556.5 832.681 2379.98
Permanent Ineff=
       F       F
Bank Sta=535.358,549.05
XS Rating Curve= 0 ,0
Exp/Cntr(USF)=0,0
Exp/Cntr=0.3,0.1

Type RM Length L Ch R = 1 ,37812   ,347.3,350.5,356.6
XS GIS Cut Line= 3
     2111312.755      184151.107     2111401.813      184690.524
     2111508.004      185226.332
#Sta/Elev= 30
       0 2481.48    55.6 2465.74   125.4  2441.8   205.2 2416.29   271.7 2392.76
   302.1 2384.14   311.6 2380.59   324.9  2377.4   354.8 2372.32   378.1 2371.36
   544.4  2371.7     551 2370.69  558.772371.744   601.2 2372.08   634.7 2373.35
   661.4 2377.94   718.3 2393.69   745.2 2394.39   751.7 2395.32   761.4 2398.01
   771.8 2397.28   795.2 2397.88   835.3 2401.47   845.4 2403.28     865 2404.02
   885.5 2406.45   915.6 2407.53   979.2 2411.63  1032.7 2417.44  1092.9 2419.68
#Mann= 6 ,-1 , 0
       0      .1       0     410    .035       0   544.4    .045       0
  558.77    .035       0  606.72     .04       0  806.72      .1       0
#XS Ineff= 2 , 0
          398.58 2373.54  582.08         2373.42
Permanent Ineff=
       F       F
Bank Sta=544.4,558.77
XS Rating Curve= 0 ,0
Exp/Cntr=0.3,0.1

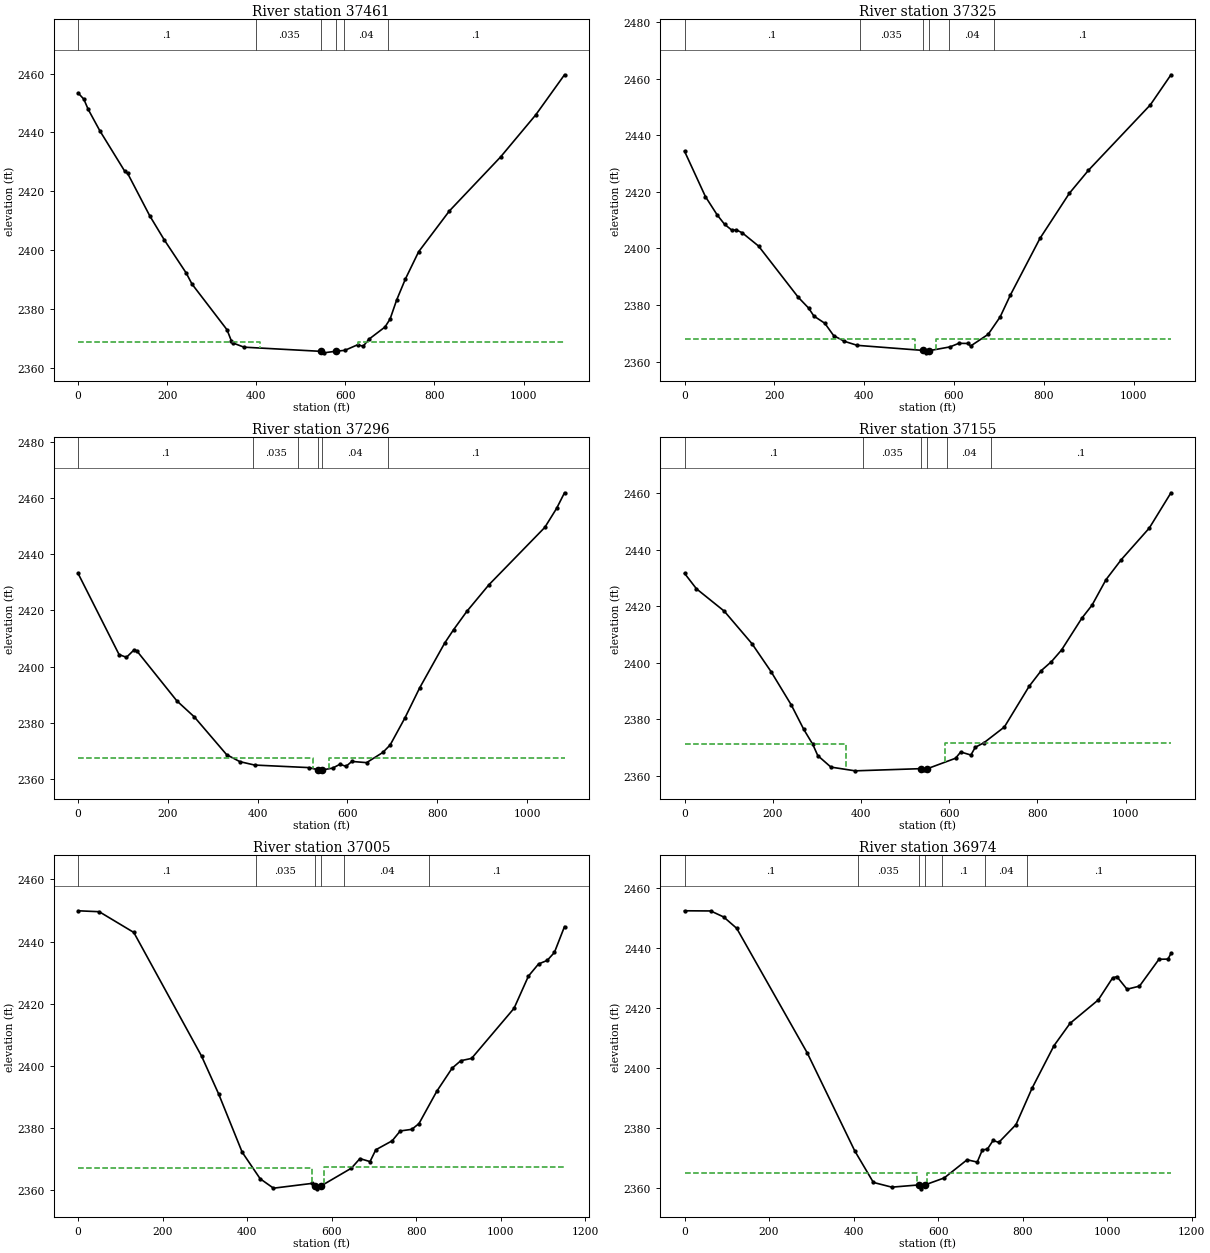
Type RM Length L Ch R = 1 ,37461   ,136.9,136.6,139.1
XS GIS Cut Line= 3
       2111067.4      184160.193     2111053.461      184705.996
     2111034.263      185251.702
#Sta/Elev= 30
       0 2453.44    12.9 2451.34    22.8 2447.84    48.9 2440.57   104.8  2426.8
   111.4 2426.04   160.9 2411.64   193.4 2403.47   242.7 2392.18   255.8  2388.4
   334.5 2372.83   344.4 2368.96   347.7 2368.36   372.4 2366.93     545 2365.51
   551.2    2365   579.8 2365.56   598.9 2365.85   627.4 2367.73   640.1 2367.26
   652.9 2369.62     689 2373.79   700.4 2376.48   715.3 2383.02   734.7 2390.08
   764.5 2399.39   833.5 2413.27   948.4 2431.64  1027.4 2445.97    1092 2459.62
#Mann= 6 ,-1 , 0
       0      .1       0     400    .035       0     545    .045       0
   579.8    .035       0  595.98     .04       0  695.98      .1       0
#XS Ineff= 2 , 0
          408.93 2368.72  627.72         2368.56
Permanent Ineff=
       F       F
Bank Sta=545,579.8
XS Rating Curve= 0 ,0
Exp/Cntr=0.5,0.3

Type RM Length L Ch R = 1 ,37325   ,28.6,28.5,28.5
XS GIS Cut Line= 2
     2110924.719      184165.855     2110909.094      185249.188
#Sta/Elev= 30
       0 2434.32    46.6 2418.27    72.9 2411.77    89.3 2408.48   105.7 2406.38
   115.5 2406.51   128.7 2405.47   164.8 2400.82   253.3 2382.71   276.3 2378.91
   288.1 2376.08   312.4 2373.53   332.1 2369.18     356 2367.15   384.6 2365.73
   531.5 2363.93   538.8 2363.08   543.8 2363.81   591.3 2365.18     611 2366.45
   630.7 2366.39   637.2 2365.49   676.3 2369.62   702.9 2375.76   725.8 2383.52
   791.5 2403.48   857.1 2419.45   899.7 2427.59  1037.5  2450.7  1083.4 2461.32
#Mann= 6 ,-1 , 0
       0      .1       0     390    .035       0   531.5    .045       0
   543.8    .035       0     590     .04       0     690      .1       0
#XS Ineff= 2 , 0
          512.45 2367.93  559.27         2367.93
Permanent Ineff=
       F       F
Bank Sta=531.5,543.8
XS Rating Curve= 0 ,0
Exp/Cntr=0.5,0.3

Type RM Length L Ch R = 1 ,37296   ,143.2,141,138.5
XS GIS Cut Line= 2
     2110896.247      184163.772     2110880.622      185247.105
#Sta/Elev= 30
       0 2433.18    91.4 2404.26   107.8 2403.29   124.2 2405.85   130.7 2405.62
     220 2387.79   258.9 2382.08   330.9 2368.63   360.4 2366.14   393.2 2364.93
   514.6 2364.02  535.25  2363.2   537.6 2362.87   544.2 2363.19   567.1 2363.85
   583.5 2365.23   596.7 2364.45   609.8 2366.22   642.6 2365.79   678.7 2369.41
   695.1 2372.08     728 2381.71   760.7 2392.37   816.5 2408.35   836.2 2413.09
   865.7 2419.61   914.9 2429.09  1039.6 2449.56  1065.9 2456.34  1083.4 2461.87
#Mann= 6 ,-1 , 0
       0      .1       0     390    .035       0     490     .04       0
  535.25    .045       0   544.2     .04       0     690      .1       0
#XS Ineff= 2 , 0
          523.55  2367.6  559.84         2367.51
Permanent Ineff=
       F       F
Bank Sta=535.25,544.2
XS Rating Curve= 0 ,0
Exp/Cntr=0.5,0.3

Type RM Length L Ch R = 1 ,37155   ,152.9,150.5,147.7
XS GIS Cut Line= 4
2110675.84392419184159.4318610162110728.28820337184530.038100521
2110775.48805462184932.1109075312110824.43604852185252.021010501
#Sta/Elev= 30
       0 2431.59    27.1 2426.11      90 2418.22     153 2406.68   196.1 2396.83
   242.4 2384.92   270.4 2376.36   290.8 2371.07   302.1  2367.1   331.9 2363.03
   386.8 2361.71   536.42362.487   543.5 2361.86   550.1 2362.44   614.4 2366.16
   626.2 2368.39   649.2  2367.3   659.1 2370.04   678.9 2371.66   725.1 2377.22
   781.3 2391.63   808.7 2397.17   831.8 2400.34   854.8 2404.48   900.7 2415.71
   923.9 2420.34   955.5 2429.35   990.4 2436.48  1053.6  2447.6  1102.8 2460.09
#Mann= 6 ,-1 , 0
       0      .1       0   404.3    .035       0   536.4    .045       0
   550.1    .035       0   594.3     .04       0   694.3      .1       0
#XS Ineff= 2 , 0
           365.9 2371.22   591.4         2371.66
Permanent Ineff=
       F       F
Bank Sta=536.4,550.1
XS Rating Curve= 0 ,0
Exp/Cntr(USF)=0,0
Exp/Cntr=0.5,0.3

Type RM Length L Ch R = 1 ,37005   ,30.7,30.7,30.8
XS GIS Cut Line= 2
     2110445.306      184151.128     2110756.563      185259.141
#Sta/Elev= 30
       0 2449.92    50.1 2449.62   131.9 2442.94   292.1 2403.13   332.5 2390.94
   388.3 2372.14   430.9 2363.57   462.4 2360.54   554.5  2362.1  559.962361.195
   564.7 2360.33   573.82361.183   646.5 2366.97   666.9 2370.07   690.8 2369.11
   704.4 2372.91   743.2 2375.81   762.3 2378.98   789.6  2379.5   806.6 2381.35
   848.6 2391.74     885 2399.21   905.5 2401.61   931.1 2402.36  1031.5 2418.49
  1065.6 2428.88  1089.5 2432.78  1109.9 2433.92    1127 2436.49  1150.9 2444.83
#Mann= 6 ,-1 , 0
       0      .1       0     420    .035       0  559.96    .045       0
   573.8    .035       0     630     .04       0     830      .1       0
#XS Ineff= 2 , 0
          553.66 2367.19  580.94         2367.28
Permanent Ineff=
       F       F
Bank Sta=559.96,573.8
XS Rating Curve= 0 ,0
Exp/Cntr=0.5,0.3

Type RM Length L Ch R = 1 ,36974   ,218.6,212,205.3
XS GIS Cut Line= 2
     2110417.528      184165.885     2110728.785      185273.898
#Sta/Elev= 30
       0  2452.3      62 2452.24    92.7 2450.23   123.4 2446.47   290.4 2404.96
   402.8 2372.33   446.8 2361.84   490.4 2360.26   554.12361.003   559.6  2359.7
  568.992361.014   614.4 2363.33   668.6 2369.38   692.5 2368.61   704.8 2372.71
   716.3 2372.87     730  2375.8   743.6 2375.17   784.2 2381.08   822.1 2393.17
   874.2 2407.39   912.1 2414.81   978.9 2422.61  1012.8 2429.94    1023 2430.37
  1046.9 2426.18  1076.4  2427.2  1122.5 2436.15  1143.8 2436.21  1150.9  2438.1
#Mann= 7 ,-1 , 0
       0      .1       0     410    .035       0   554.1    .045       0
  568.99    .035       0     610      .1       0     710     .04       0
     810      .1       0
#XS Ineff= 2 , 0
           550.3 2365.08  573.24          2364.9
Permanent Ineff=
       F       F
Bank Sta=554.1,568.99
XS Rating Curve= 0 ,0
Exp/Cntr=0.5,0.3

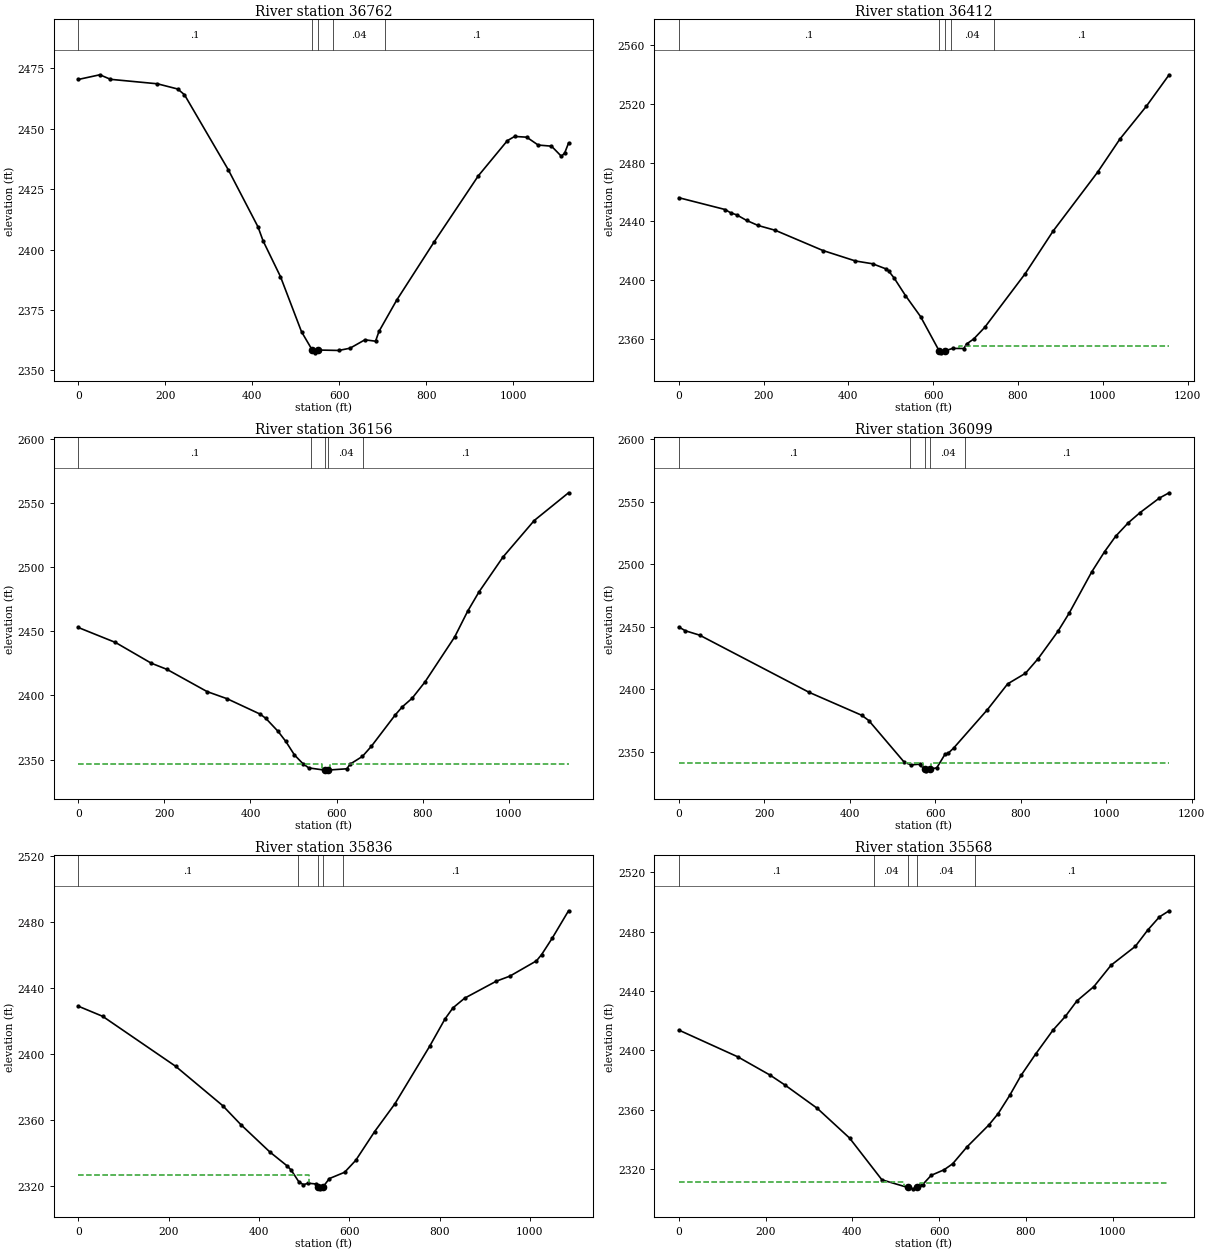
Type RM Length L Ch R = 1 ,36762   ,341.8,350,357.1
XS GIS Cut Line= 3
     2110069.723      184375.775      2110391.72      184815.892
     2110731.293      185287.932
#Sta/Elev= 30
       0  2470.4    49.7 2472.34    74.1 2470.46   181.9 2468.61   228.6 2466.45
   244.1 2464.09     345 2432.98   413.1  2409.4   424.8 2403.61   464.8 2388.79
   513.1 2366.01   537.5 2358.51   543.1 2357.27  550.732358.439   598.6 2358.26
   624.5 2359.18   658.8 2362.66   683.3 2362.09   691.1 2366.12   731.6    2379
   817.2 2402.98   919.5 2430.54   986.2 2445.08  1002.9 2446.82  1030.6 2446.52
    1057 2443.26  1087.6  2442.8  1110.5 2438.58  1118.1 2440.05  1126.8 2444.07
#Mann= 5 ,-1 , 0
       0      .1       0   537.5    .045       0  550.73      .1       0
  585.33     .04       0  705.33      .1       0
Bank Sta=537.5,550.73
XS Rating Curve= 0 ,0
Exp/Cntr=0.3,0.1

Type RM Length L Ch R = 1 ,36412   ,264,256.5,236.9
XS GIS Cut Line= 3
     2109986.584      184421.473     2110135.847      185025.651
     2110169.876      185558.654
#Sta/Elev= 30
       0 2456.15   109.2 2448.13   122.7 2445.83   136.5 2444.52   159.8 2440.74
   186.9  2437.3   227.4 2434.04   339.8 2420.31   416.7 2413.19   457.2 2411.29
   487.7 2407.93   494.7 2406.47   507.8 2401.65   534.6 2389.71   570.1 2375.49
  614.112352.139   616.1  2351.2   619.5 2350.84  627.272352.137   645.8 2353.85
   672.1 2353.78   678.7 2356.84   695.7  2360.3   721.4 2368.11   816.8 2404.53
   882.5 2433.39   987.7 2473.46  1040.3 2495.96  1102.8 2518.27  1156.4  2539.6
#Mann= 5 ,-1 , 0
       0      .1       0  614.11    .045       0  627.27      .1       0
  642.34     .04       0  742.34      .1       0
#XS Ineff= 2 , 0
                          659.87         2355.44
Permanent Ineff=
       F       F
Bank Sta=614.11,627.27
XS Rating Curve= 0 ,0
Exp/Cntr=0.5,0.3

Type RM Length L Ch R = 1 ,36156   ,47.8,56.9,58.7
XS GIS Cut Line= 4
     2109966.411      184419.189     2109876.568      184959.554
     2109922.141      184986.898     2109867.453      185522.054
#Sta/Elev= 30
       0 2453.02    86.5 2441.33   169.6 2425.17   206.2 2420.33   299.3 2403.02
   345.9 2397.44   422.4 2385.48   435.7 2382.16   464.2    2372   482.2 2364.14
   502.2 2353.63   522.1 2346.75   535.4 2343.52   573.1 2341.74   576.3 2341.23
     581 2341.85   623.9 2342.82   631.5 2346.46   660.1 2352.48   680.6 2360.25
     736 2384.68   752.5 2391.06   775.6 2397.84   805.3 2410.48   874.5 2445.69
   904.6 2465.73   930.8  2480.7   986.6 2507.93  1059.2 2536.42  1138.9 2558.05
#Mann= 5 ,-1 , 0
       0      .1       0     540     .04       0   573.1    .045       0
     581     .04       0  660.93      .1       0
#XS Ineff= 2 , 0
           565.8  2346.4  585.67         2346.56
Permanent Ineff=
       F       F
Bank Sta=573.1,581
XS Rating Curve= 0 ,0
Exp/Cntr=0.5,0.3

Type RM Length L Ch R = 1 ,36099   ,253.2,262.9,281.5
XS GIS Cut Line= 4
     2109935.161      184413.981     2109838.807      184982.991
      2109884.38      185010.335     2109833.599      185524.658
#Sta/Elev= 30
       0 2449.95    15.2 2446.93    48.5 2443.44   304.7 2397.72   427.9 2379.35
   444.5 2375.13   527.7 2341.71   544.3 2339.63   564.3 2340.34   567.6 2339.94
  574.952336.025   577.6 2334.92   587.3  2336.2   603.6 2337.38   622.7 2348.13
   630.3 2349.04   642.8 2353.05     722 2383.84   769.4 2404.47     811 2412.92
   840.6 2424.59   886.8 2446.36   913.2 2460.98   965.9 2493.91   996.2 2510.21
  1021.8 2522.39  1051.6 2533.28  1079.1 2541.39  1124.1 2552.97  1147.1 2557.25
#Mann= 5 ,-1 , 0
       0      .1       0     540     .04       0  574.95    .045       0
   587.3     .04       0  670.26      .1       0
#XS Ineff= 2 , 0
          571.86  2341.3  590.82         2341.43
Permanent Ineff=
       F       F
Bank Sta=574.95,587.3
XS Rating Curve= 0 ,0
Exp/Cntr=0.5,0.3

Type RM Length L Ch R = 1 ,35836   ,248.4,267.6,286.5
XS GIS Cut Line= 4
2109742.33575487184379.6978335522109667.16562139184708.348649717
2109567.52149095185120.9103125622109506.33649858185439.072272892
#Sta/Elev= 30
       0 2429.05      54 2422.92   215.5  2392.7   319.8 2368.86     360 2357.37
   424.4 2340.77   463.1 2332.26   471.5 2329.82   488.5 2322.72   498.7 2321.01
   508.8  2321.9   525.4 2321.47  530.272319.792   535.8  2318.5  542.282319.793
     556 2324.71   589.8 2328.53   614.4 2335.74   656.3 2353.17   701.2    2370
   777.8 2404.65     812 2421.29   829.6    2428   855.5 2433.88   925.6 2444.16
   955.7 2447.23  1014.6 2456.48    1026 2460.29  1049.3 2470.13  1085.6 2486.78
#Mann= 5 ,-1 , 0
       0      .1       0  487.14     .04       0  530.27    .045       0
  542.28     .04       0  587.14      .1       0
#XS Ineff= 2 , 0
          509.88 2326.92
Permanent Ineff=
       F       F
Bank Sta=530.27,542.28
XS Rating Curve= 0 ,0
Exp/Cntr(USF)=0,0
Exp/Cntr=0.5,0.3

Type RM Length L Ch R = 1 ,35568   ,52.9,44.5,31.8
XS GIS Cut Line= 4
     2109519.276      184320.513     2109387.983      184826.155
      2109348.92      184832.666     2109309.858      185399.072
#Sta/Elev= 30
       0 2413.65   135.8 2395.65   210.4 2383.31   244.3 2376.72   318.9    2361
   393.4 2340.98     468 2312.84  527.072307.743   540.4 2306.77  548.062307.743
     555 2309.69     562 2309.69   581.6 2315.87   611.2  2319.6     631 2323.63
   663.8 2334.93   714.4 2349.77   735.9 2357.43   762.5  2369.7   788.8 2383.22
     822 2397.42     862 2413.54   890.8  2422.9   917.4 2433.32   956.5 2442.94
     996 2457.31  1051.9    2470  1080.5 2480.97  1107.4 2489.83  1129.8 2493.96
#Mann= 5 ,-1 , 0
       0      .1       0     450     .04       0  527.07    .045       0
  548.06     .04       0  682.01      .1       0
#XS Ineff= 2 , 0
           518.1 2311.13  555.34         2311.03
Permanent Ineff=
       F       F
Bank Sta=527.07,548.06
XS Rating Curve= 0 ,0
Exp/Cntr=0.5,0.3