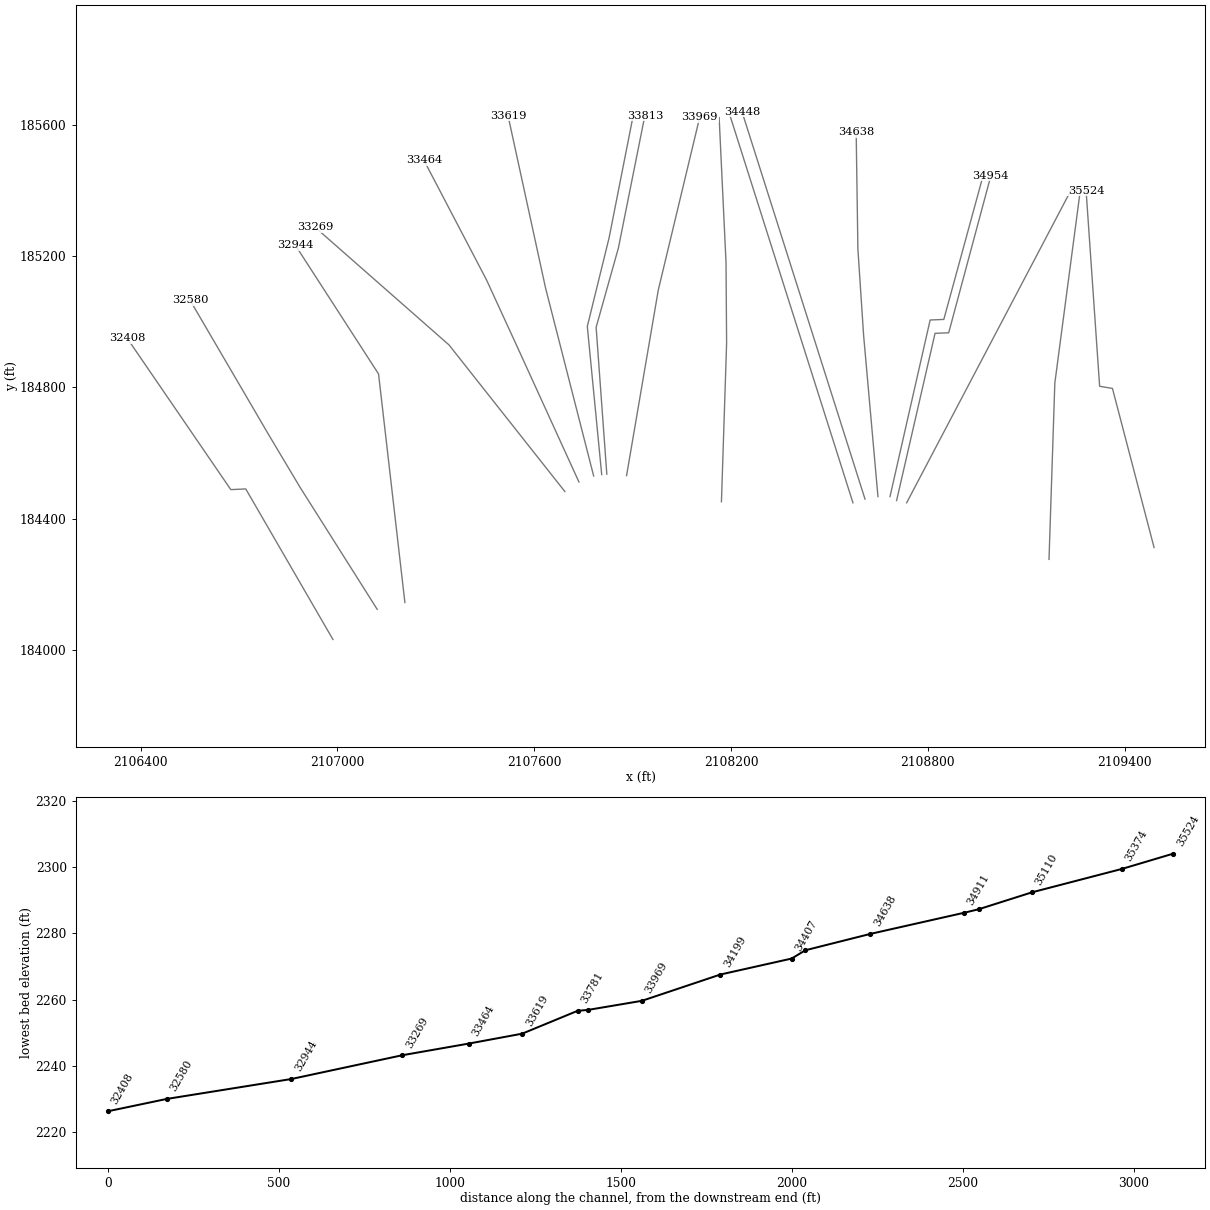
HEC-RAS study DRPLKCR.prj: DRPLKCR

--- DRPLKCR.g01 (geometry) --- (continued)

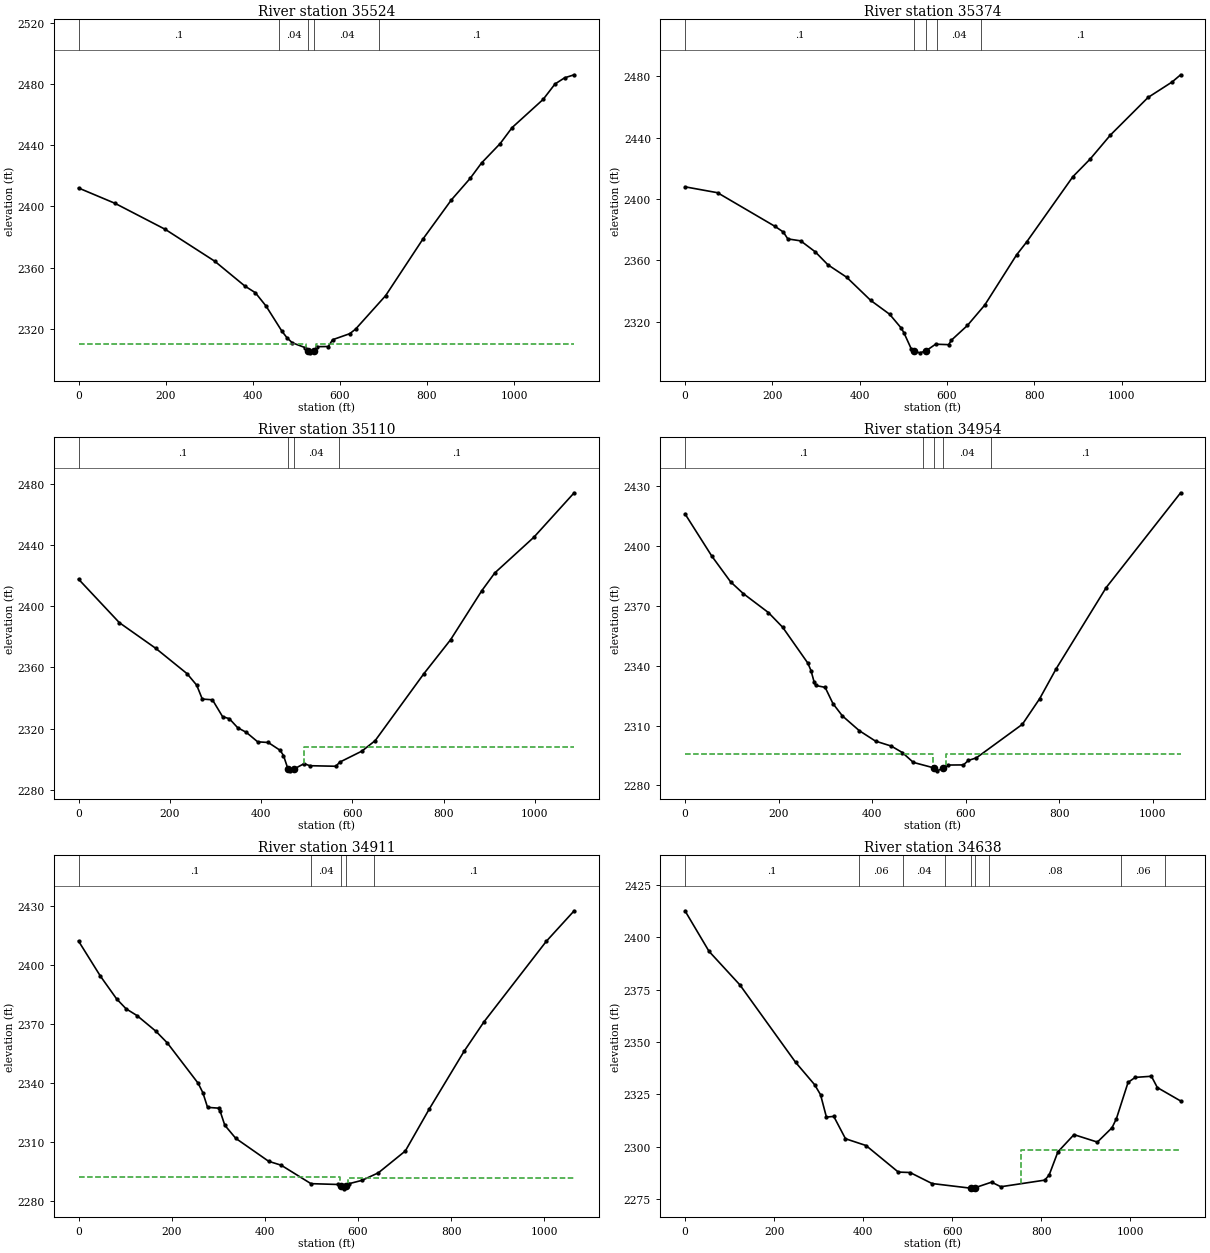
Type RM Length L Ch R = 1 ,35524   ,155.6,150.2,136.1
XS GIS Cut Line= 4
     2109489.979      184311.832     2109363.026      184796.859
     2109323.963      184803.369     2109282.731      185399.072
#Sta/Elev= 30
       0 2412.07    83.8 2402.03   199.1 2385.01   312.5 2364.21     382 2347.89
     406 2343.54   430.8 2334.73     467 2318.37   478.5 2314.11   490.8 2310.76
   520.6 2307.57  527.332305.346     532 2304.18  541.152305.346   547.2 2308.22
   573.5 2308.32   583.4 2312.76   622.8 2316.72   636.2 2319.71   705.1 2341.58
   790.6 2378.56   856.3 2404.33   899.1 2418.29   925.4 2428.43   968.2 2441.14
   995.7 2451.63  1066.8 2470.03  1094.1 2480.13  1116.1 2484.16  1138.1 2486.16
#Mann= 5 ,-1 , 0
       0      .1       0     460     .04       0  527.33    .045       0
  541.15     .04       0  690.97      .1       0
#XS Ineff= 2 , 0
          523.34 2310.28  545.01         2310.28
Permanent Ineff=
       F       F
Bank Sta=527.33,541.15
XS Rating Curve= 0 ,0
Exp/Cntr=0.5,0.3

Type RM Length L Ch R = 1 ,35374   ,270,263.3,255.8
XS GIS Cut Line= 3
     2109169.602      184275.693     2109187.347      184813.078
     2109265.606      185405.225
#Sta/Elev= 30
       0 2407.91    74.6 2404.05   205.9 2382.13   225.1 2378.43   235.5 2373.91
     265 2372.63   298.2  2365.5   327.4 2356.99   370.1 2348.92   425.3 2333.77
   468.5 2324.76   494.8 2315.85   501.4 2312.63   518.1 2302.17  524.432300.783
   537.5 2299.55  551.612300.783   573.9 2305.19   603.7 2304.89   610.3 2307.87
   646.7 2317.41   686.4 2330.71   759.2 2363.43   782.4 2371.91   888.3 2414.54
     928 2426.09   974.3 2441.73  1060.3 2466.21  1115.4 2476.32    1135 2481.03
#Mann= 5 ,-1 , 0
       0      .1       0  524.43    .045       0  551.61      .1       0
  577.68     .04       0  677.68      .1       0
Bank Sta=524.43,551.61
XS Rating Curve= 0 ,0
Exp/Cntr=0.3,0.1

Type RM Length L Ch R = 1 ,35110   ,172.6,156.4,134.8
XS GIS Cut Line= 2
     2108735.443      184448.145     2109241.086      185409.516
#Sta/Elev= 30
       0 2417.59    89.6 2389.15   169.1 2372.46   237.9 2355.88     259 2348.38
   271.2 2339.32   293.5 2338.83   315.7 2327.85   330.5  2326.5   348.8 2320.61
   367.6 2317.61   392.6 2311.41   415.8 2310.96   441.8 2305.86   449.2 2302.46
  458.942293.733     464 2292.46   471.4 2293.53   494.6 2297.18   506.7 2295.81
   564.1 2295.45   572.3 2298.11   620.9 2305.32   650.1 2312.17   756.8 2355.86
   815.3    2378     884 2410.14   912.2 2421.63   997.8 2444.92  1086.2 2473.96
#Mann= 4 ,-1 , 0
       0      .1       0  458.94    .045       0   471.4     .04       0
     570      .1       0
#XS Ineff= 2 , 0
                          495.13         2307.95
Permanent Ineff=
       F       F
Bank Sta=458.94,471.4
XS Rating Curve= 0 ,0
Exp/Cntr=0.5,0.3

Type RM Length L Ch R = 1 ,34954   ,43.7,43.1,45.7
XS GIS Cut Line= 4
     2108704.895      184455.185     2108822.083      184964.734
     2108863.749       184966.47     2108992.221      185444.768
#Sta/Elev= 30
       0 2416.24    57.3 2395.05    97.7 2382.08   124.6 2376.24   178.5 2366.69
   208.8 2359.36   262.7 2341.35   269.4 2337.64   276.1 2331.93   279.5 2330.14
   299.7 2329.19   316.5    2321   336.7 2314.85   372.8 2307.45   407.4 2302.23
   441.1 2299.74   464.7 2296.51   488.2 2291.56  532.752288.762   539.3 2287.32
  552.482288.762     563 2290.23   595.4 2290.29   605.9 2292.54   622.9 2293.81
   721.4 2310.66   758.4 2323.51   793.5 2338.46   900.6 2379.24  1059.8 2426.79
#Mann= 5 ,-1 , 0
       0      .1       0     510     .04       0  532.75    .045       0
  552.48     .04       0  654.55      .1       0
#XS Ineff= 2 , 0
          529.62 2295.99  557.89         2295.93
Permanent Ineff=
       F       F
Bank Sta=532.75,552.48
XS Rating Curve= 0 ,0
Exp/Cntr=0.5,0.3

Type RM Length L Ch R = 1 ,34911   ,239.9,273,298.1
XS GIS Cut Line= 4
     2108684.756      184467.251     2108807.152      185005.445
     2108848.819      185007.182     2108972.951      185461.175
#Sta/Elev= 30
       0 2412.41    47.2 2394.47    81.9 2382.93   102.2  2377.9   125.7 2374.45
     166 2366.52   190.6 2360.56   256.9    2340     267  2335.2   277.1 2327.73
   300.6 2327.33     304 2325.87   314.1 2318.63   337.6 2311.97   408.3 2300.27
   435.2 2298.28   499.1 2288.89   557.1 2288.47   563.92287.655   570.2 2286.25
   575.32287.655   580.1 2288.83   608.7 2290.57   643.9 2294.41   701.7 2305.51
   752.7 2326.71   827.7  2356.2   870.5 2371.22  1004.4 2412.25  1064.3 2427.81
#Mann= 5 ,-1 , 0
       0      .1       0     500     .04       0   563.9    .045       0
   575.3     .04       0  633.64      .1       0
#XS Ineff= 2 , 0
          561.77 2292.25  577.91            2292
Permanent Ineff=
       F       F
Bank Sta=563.9,575.3
XS Rating Curve= 0 ,0
Exp/Cntr=0.5,0.3

Type RM Length L Ch R = 1 ,34638   ,183.9,190.4,196.1
XS GIS Cut Line= 4
2108647.99846275184467.1049655112108604.29489677184958.333047119
2108586.81347037185222.3025856352108581.56904246185577.175541387
#Sta/Elev= 30
       0 2412.64      54 2393.27   123.2 2377.27   248.3 2340.29     291 2329.61
   304.3 2324.82   317.5 2314.13     334 2314.47   360.3  2303.8   406.4 2300.56
   478.9 2287.88   505.2 2287.68   554.5 2282.42   641.3 2280.19   646.6 2279.88
   651.9 2280.47   688.2 2283.07   709.1 2280.88   807.6 2284.04   817.5 2286.51
   837.1 2297.53   873.2 2305.76   925.7  2302.2   958.5 2309.03   968.4 2313.36
   994.6  2330.7  1010.6 2333.09    1047 2333.63  1060.3 2328.24  1112.6 2321.83
#Mann= 9 ,-1 , 0
       0      .1       0     390     .06       0     490     .04       0
  583.17      .1       0   641.3    .045       0   651.9      .1       0
  683.17     .08       0  977.72     .06       0 1077.72      .1       0
#XS Ineff= 2 , 0
                           753.8         2298.19
Permanent Ineff=
       F       F
Bank Sta=641.3,651.9
XS Rating Curve= 0 ,0
Exp/Cntr(USF)=0,0
Exp/Cntr=0.5,0.3

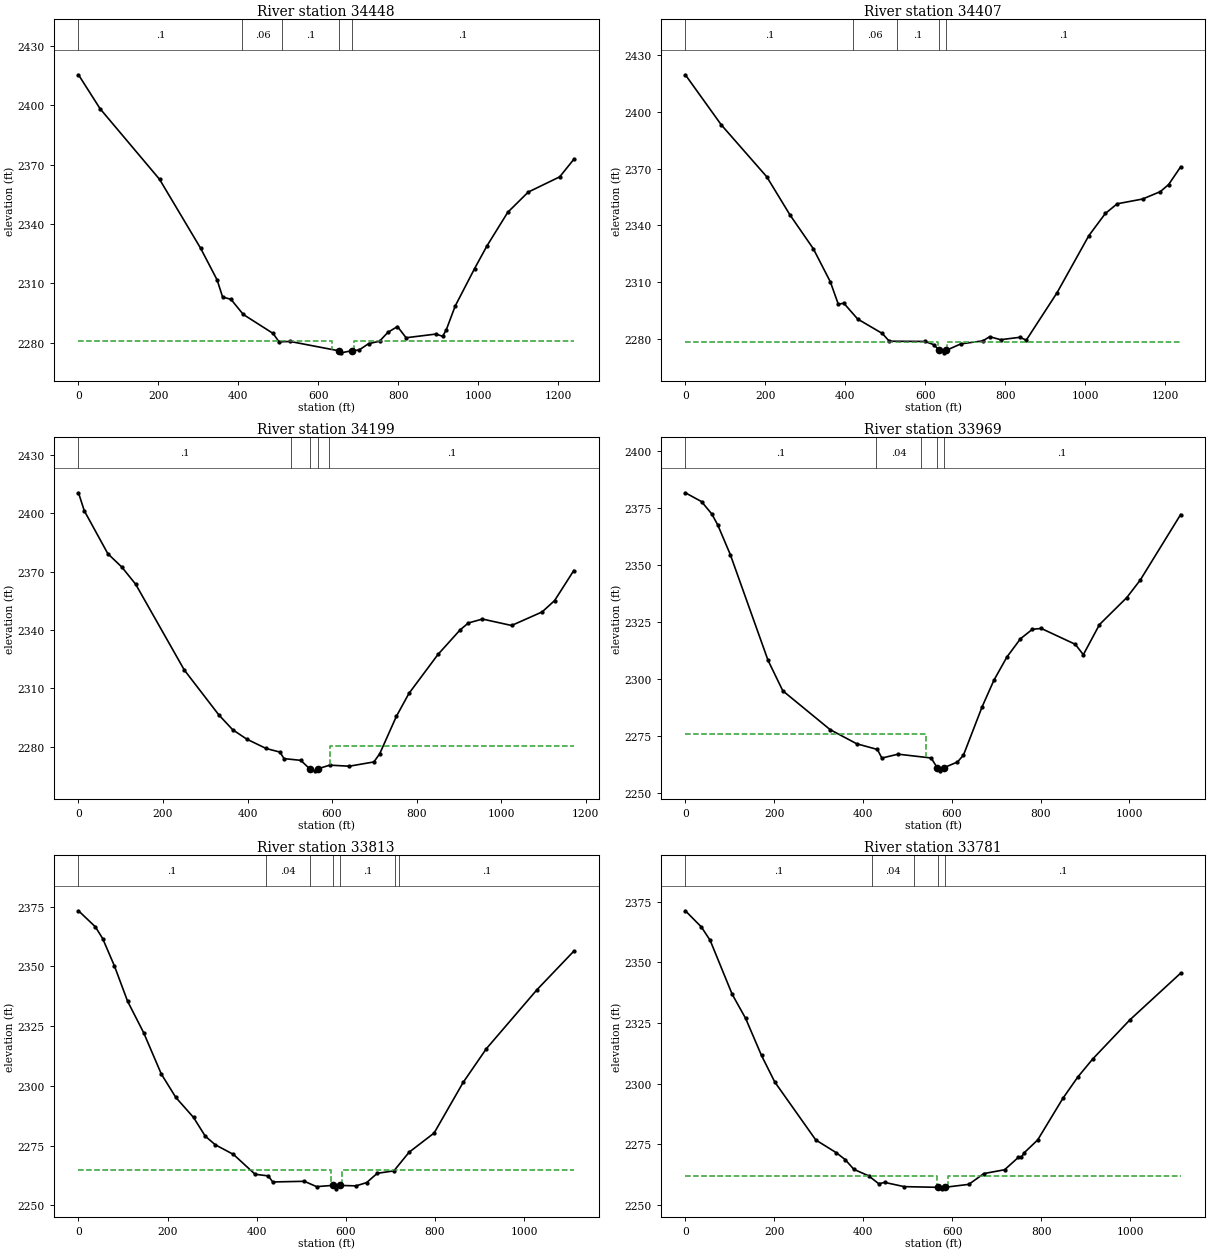
Type RM Length L Ch R = 1 ,34448   ,42.8,40.1,47.8
XS GIS Cut Line= 2
     2108608.541      184459.439     2108233.541      185639.994
#Sta/Elev= 30
       0 2415.36    54.1 2398.19   202.8 2362.54   305.4 2327.75   346.7 2311.74
   360.5 2303.07   381.2 2301.97   412.1 2294.31   486.5 2284.74   501.6 2280.46
   529.3 2280.66   650.3 2275.98   656.6 2274.92  683.342275.979   701.8 2276.36
   725.6 2279.56   752.9 2280.78   773.6 2285.24   797.7  2288.2   819.3 2282.54
   894.1 2284.41   910.8 2283.25     920 2286.64   942.1 2298.56   990.5 2317.45
  1021.4 2328.88  1073.7 2345.94  1124.7 2356.11  1203.4  2363.8  1238.7 2372.66
#Mann= 5 ,-1 , 0
       0      .1       0     410     .06       0     510      .1       0
   650.3    .045       0  683.34      .1       0
#XS Ineff= 2 , 0
          635.18 2280.98  689.05         2280.83
Permanent Ineff=
       F       F
Bank Sta=650.3,683.34
XS Rating Curve= 0 ,0
Exp/Cntr=0.5,0.3

Type RM Length L Ch R = 1 ,34407   ,210.6,208.3,204.3
XS GIS Cut Line= 2
     2108571.735      184448.327     2108196.735      185628.883
#Sta/Elev= 30
       0 2419.71    89.9 2393.17   203.5  2365.7     262 2345.36   320.1 2327.54
   362.6 2310.02   382.5 2298.16   396.3  2298.7     431 2290.31   492.7 2282.66
   509.9 2278.57   599.4 2278.44   621.2 2276.72  635.072273.751   647.3 2272.41
  652.672273.752   688.9 2277.15     744 2278.76   761.2 2280.97   788.4 2279.37
   836.9 2280.65   852.6 2279.13   929.5 2304.23    1009 2334.46  1050.3 2346.23
  1080.1 2351.37  1143.3 2353.88  1187.8  2357.8  1208.7 2361.58  1238.7 2370.95
#Mann= 5 ,-1 , 0
       0      .1       0     420     .06       0     530      .1       0
  635.07    .045       0  652.67      .1       0
#XS Ineff= 2 , 0
          630.79 2277.92  655.43         2277.97
Permanent Ineff=
       F       F
Bank Sta=635.07,652.67
XS Rating Curve= 0 ,0
Exp/Cntr=0.5,0.3

Type RM Length L Ch R = 1 ,34199   ,232.9,229.6,223.5
XS GIS Cut Line= 4
2108170.75552225184451.371681758  2108186.488806184933.859050171
2108184.74066336185180.3471622942108163.76295169185622.627250006
#Sta/Elev= 30
       0 2410.54    13.7  2401.3    69.5 2379.19   102.4 2372.38   135.2 2363.55
   250.3 2319.44   332.1 2296.33   364.7 2288.75   397.8 2283.93   443.8 2279.08
   476.6 2277.22   486.4 2273.86   525.8 2272.98  547.242268.611   558.6 2267.58
  566.152268.611   594.7 2270.51   640.6 2269.96     699 2272.16   712.8 2276.38
   752.2 2295.59   781.9 2307.38   850.6 2327.41   903.3 2340.11   922.7 2343.61
   955.8 2345.62  1024.8 2342.31  1097.1 2349.28  1126.6 2355.12    1172 2370.57
#Mann= 5 ,-1 , 0
       0      .1       0  502.74     .04       0  547.24    .045       0
  566.15     .04       0  592.74      .1       0
#XS Ineff= 2 , 0
                          594.84         2280.49
Permanent Ineff=
       F       F
Bank Sta=547.24,566.15
XS Rating Curve= 0 ,0
Exp/Cntr(USF)=0,0
Exp/Cntr=0.3,0.1

Type RM Length L Ch R = 1 ,33969   ,158,156.4,155
XS GIS Cut Line= 3
     2107881.446      184530.972     2107978.237      185097.025
     2108104.413       185623.07
#Sta/Elev= 30
       0 2381.77    36.4  2377.9    59.7 2372.42      73 2367.61   101.2 2354.62
   186.1 2308.19   219.4 2294.78   325.9 2277.73   385.8 2271.51   432.4 2269.01
   442.4 2265.23     479 2266.94   553.3 2265.27  567.372260.922   573.2 2259.62
  581.352260.923   612.7 2263.51   626.2 2266.53   668.2 2287.76   694.8 2299.44
     724 2309.62   754.4 2317.61   781.4 2321.81   801.4 2322.17     878  2315.2
   896.1 2310.64   932.4 2323.87   993.9 2335.73  1024.3 2343.44  1115.2 2372.22
#Mann= 5 ,-1 , 0
       0      .1       0     430     .04       0     530      .1       0
  567.37    .045       0  581.35      .1       0
#XS Ineff= 2 , 0
          541.55 2275.67
Permanent Ineff=
       F       F
Bank Sta=567.37,581.35
XS Rating Curve= 0 ,0
Exp/Cntr=0.5,0.3

Type RM Length L Ch R = 1 ,33813   ,32.4,31.7,33.9
XS GIS Cut Line= 4
2107821.21440155 184535.614675542107788.64650418184983.069265463
2107856.61428999185225.2045024162107937.32603564185628.763230669
#Sta/Elev= 30
       0 2373.22    37.9  2366.5    54.3 2361.59    80.6 2350.16   110.2 2335.37
   146.4 2322.15   185.9 2304.92   218.5 2295.12   258.3 2286.74   284.6  2278.9
   307.2 2275.31   347.8 2271.29   396.4 2262.98     426 2262.31   435.9 2259.77
     507 2260.04   534.4 2257.81   571.7 2258.35   578.6 2256.89   587.4 2258.32
   622.8 2258.13   646.7  2259.5   670.6 2263.39   707.9  2264.4     742  2272.2
   798.2 2280.24   863.3 2301.39   915.3 2315.48  1029.1  2340.2  1111.7 2356.32
#Mann= 7 ,-1 , 0
       0      .1       0     420     .04       0  518.64      .1       0
   571.7    .045       0   587.4      .1       0  710.13     .06       0
  720.13      .1       0
#XS Ineff= 2 , 0
          567.86 2264.73  591.88         2264.68
Permanent Ineff=
       F       F
Bank Sta=571.7,587.4
XS Rating Curve= 0 ,0
Exp/Cntr(USF)=0,0
Exp/Cntr=0.5,0.3

Type RM Length L Ch R = 1 ,33781   ,152.2,161.9,168.5
XS GIS Cut Line= 4
2107805.63845063184534.1986800022107761.74258896184985.901256539
2107828.29437924185256.356404246 2107901.9261472185630.179226207
#Sta/Elev= 30
       0 2371.34    36.1 2364.64    55.8 2359.11   105.3 2336.86   135.5 2326.92
   171.2 2311.62   200.9 2300.71   293.2 2276.76   339.3  2271.5   359.1 2268.68
   378.9 2264.63   411.8 2261.97   434.9 2258.69     448 2259.25   491.9  2257.5
     569 2257.21   576.3 2256.59     584 2257.24   637.2 2258.44   670.9 2262.88
   717.7 2264.47   748.4 2269.55   755.2 2269.62   761.9 2271.51     792 2276.77
   848.5 2293.89   882.2 2302.74   915.7 2310.17   999.3 2326.33  1113.4  2345.6
#Mann= 5 ,-1 , 0
       0      .1       0     420     .04       0  513.83      .1       0
     569    .045       0     584      .1       0
#XS Ineff= 2 , 0
          564.95 2261.91  589.38         2262.02
Permanent Ineff=
       F       F
Bank Sta=569,584
XS Rating Curve= 0 ,0
Exp/Cntr(USF)=0,0
Exp/Cntr=0.5,0.3

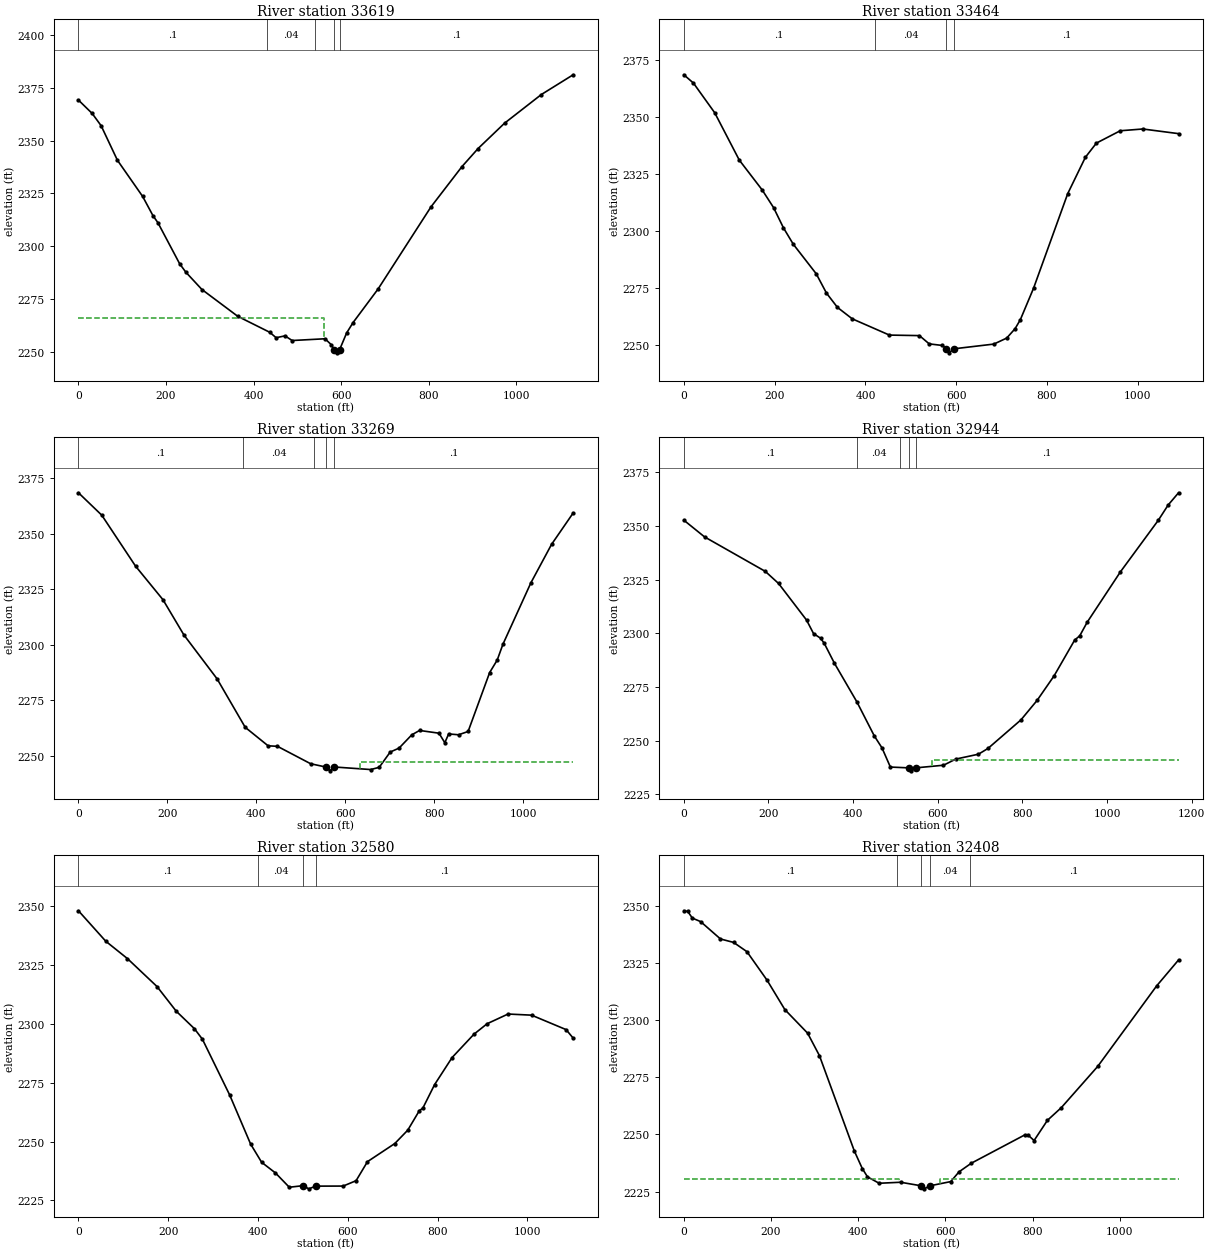
Type RM Length L Ch R = 1 ,33619   ,152.5,155.8,158.7
XS GIS Cut Line= 3
     2107781.135      184529.894     2107634.555      185102.417
     2107519.888      185628.619
#Sta/Elev= 30
       0 2369.09    31.3 2362.78    51.7    2357      89 2340.65   146.5 2323.59
   170.2 2314.46   181.2 2311.23   231.1 2291.74   245.2 2287.78   281.9  2279.6
   363.9 2266.91   436.7  2259.4   451.3 2256.83   471.6  2257.7   487.9  2255.5
     563 2256.33   576.9 2253.59  584.322251.085   590.4 2249.68   593.5 2249.97
  596.082251.084   612.4 2259.11   627.1 2264.01   684.2 2279.87     805 2318.67
   875.6 2337.66   912.5 2346.22   972.9 2358.18  1056.9 2371.72  1129.5 2381.05
#Mann= 5 ,-1 , 0
       0      .1       0     430     .04       0     540      .1       0
  584.32    .045       0  596.08      .1       0
#XS Ineff= 2 , 0
          560.46 2266.14
Permanent Ineff=
       F       F
Bank Sta=584.32,596.08
XS Rating Curve= 0 ,0
Exp/Cntr=0.3,0.1

Type RM Length L Ch R = 1 ,33464   ,190.7,194.2,202
XS GIS Cut Line= 4
2107736.25466928184511.5427513982107550.75925384184917.933470728
2107454.47155727185127.5008103122107263.31215968185492.827659047
#Sta/Elev= 30
       0 2368.39    21.1 2364.76      68 2351.76   122.1 2331.05   172.6 2317.97
   197.7 2310.23   219.4 2301.39   241.1 2294.21   291.6 2281.29   314.1 2272.85
   338.4 2266.57   370.9 2261.58   452.8 2254.46   518.9 2254.23   540.5 2250.61
   569.4 2249.92  578.522248.467   583.8 2246.69  595.352248.468   682.8 2250.52
   711.1 2253.14   729.6 2257.25   741.1 2261.14   770.3 2274.96   845.6 2316.37
   884.5 2332.28   908.8 2338.49   961.3 2343.89    1011 2344.66  1089.7 2342.63
#Mann= 4 ,-1 , 0
       0      .1       0     420     .04       0  578.52    .045       0
  595.35      .1       0
Bank Sta=578.52,595.35
XS Rating Curve= 0 ,0
Exp/Cntr(USF)=0,0
Exp/Cntr=0.3,0.1

Type RM Length L Ch R = 1 ,33269   ,332.2,325,310.1
XS GIS Cut Line= 3
     2107693.303      184482.482     2107340.016       184929.44
     2106932.019      185287.829
#Sta/Elev= 30
       0 2368.46    52.5 2358.35   128.4 2335.41   190.1 2320.28   237.1 2304.43
   311.8 2284.63   375.1 2262.78   426.6 2254.45   447.6 2254.22   522.3 2246.37
  557.832244.828   565.7 2243.17   575.1 2244.91   657.4 2243.75   676.5 2244.75
   701.3 2251.64   721.2 2253.41   749.8 2259.39   767.3 2261.37     811 2260.13
   824.1 2255.84   832.8  2259.8     855 2259.42   876.5  2260.9     925 2287.46
     942 2293.09   954.8 2300.18  1017.7 2327.87  1064.2  2345.2  1112.8 2359.34
#Mann= 5 ,-1 , 0
       0      .1       0     370     .04       0     530      .1       0
  557.83    .045       0   575.1      .1       0
#XS Ineff= 2 , 0
                          632.93         2247.28
Permanent Ineff=
       F       F
Bank Sta=557.83,575.1
XS Rating Curve= 0 ,0
Exp/Cntr=0.3,0.1

Type RM Length L Ch R = 1 ,32944   ,355.1,364.5,371
XS GIS Cut Line= 3
     2107205.495      184144.325       2107125.2       184840.94
     2106871.294      185233.735
#Sta/Elev= 30
       0 2352.72    48.8 2344.95   192.4 2328.88   223.8 2323.24   289.9  2306.2
   306.4 2299.91   322.9 2297.75   331.7 2295.37   355.9 2286.04   408.8  2268.1
   450.1 2252.19   468.2 2246.64     488 2237.72   531.2 2237.35   537.6 2235.96
   547.4 2237.34   613.5 2238.57   642.6 2241.44   696.1 2243.71   718.6 2246.39
   796.5 2259.69   834.6 2268.75   874.9 2280.23   923.4 2296.86   935.5 2298.88
   953.2 2305.24  1031.5 2328.64    1121 2352.66  1144.4  2359.8  1168.9 2365.49
#Mann= 5 ,-1 , 0
       0      .1       0     410     .04       0     510      .1       0
   531.2    .045       0   547.4      .1       0
#XS Ineff= 2 , 0
                          587.03         2241.08
Permanent Ineff=
       F       F
Bank Sta=531.2,547.4
XS Rating Curve= 0 ,0
Exp/Cntr=0.3,0.1

Type RM Length L Ch R = 1 ,32580   ,152.3,172,192.5
XS GIS Cut Line= 4
2107120.96560466184123.5400946322106885.96151873184495.230230534
2106790.04148366184655.8962892792106550.24139598185065.954439209
#Sta/Elev= 30
       0 2348.02    60.8 2335.09   109.1 2327.71     175 2315.84   217.8 2305.37
   258.2 2297.96     276  2293.5   336.7 2269.84   383.5 2248.94     408 2241.21
   438.8 2236.68   469.6 2230.61   500.2 2231.27   513.1 2229.93   528.4 2231.08
   589.7 2231.11   618.4 2233.39   643.8 2241.48   704.7 2249.18   733.5 2254.85
   759.3 2263.12   767.1 2264.21   793.3  2274.2   832.3  2285.7   880.9 2295.59
   910.3 2300.05   956.9 2304.17  1009.3 2303.69  1086.2 2297.55  1101.9 2293.95
#Mann= 4 ,-1 , 0
       0      .1       0     400     .04       0   500.2    .045       0
   528.4      .1       0
Bank Sta=500.2,528.4
XS Rating Curve= 0 ,0
Exp/Cntr(USF)=0,0
Exp/Cntr=0.5,0.3

Type RM Length L Ch R = 1 ,32408   ,60.6,61.5,54.7
XS GIS Cut Line= 4
     2106986.087      184031.531     2106720.245      184490.515
     2106674.672      184488.345     2106358.917      184949.499
#Sta/Elev= 30
       0 2347.79     8.9  2347.5    19.5 2344.59    38.5 2343.05      84 2335.46
   114.1 2333.96   144.7 2329.91   190.9 2317.43   231.7 2304.58   283.9 2294.28
     311 2284.47   391.1 2242.75   409.4 2235.05   421.3 2231.44     448 2228.64
   497.3 2229.08  544.382227.533   551.2  2226.2  564.772227.533   612.3 2229.37
   631.2 2233.62   659.5 2237.41   782.2 2249.79   790.4 2249.58   803.5 2247.33
   834.1 2256.16     866 2261.71   949.5 2279.74  1084.7 2314.95  1134.9 2326.28
#Mann= 5 ,-1 , 0
       0      .1       0     490     .04       0  544.38    .045       0
  564.77     .04       0  656.04      .1       0
#XS Ineff= 2 , 0
          494.19 2230.64  587.78         2230.64
Permanent Ineff=
       F       F
Bank Sta=544.38,564.77
XS Rating Curve= 0 ,0
Exp/Cntr=0.5,0.3