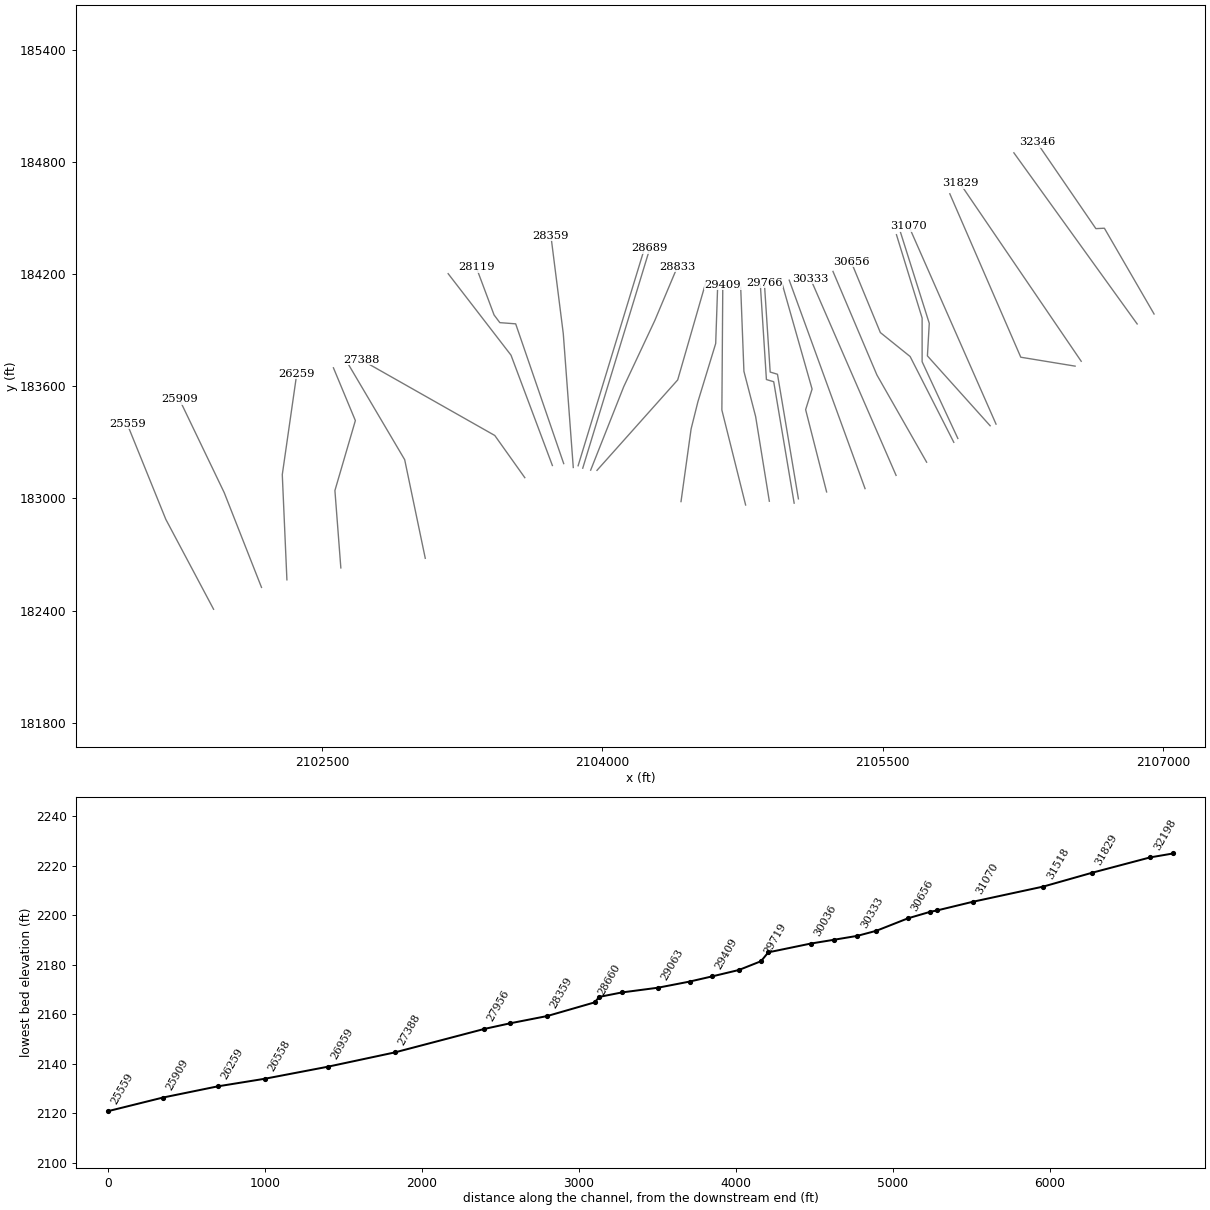
HEC-RAS study DRPLKCR.prj: DRPLKCR

--- DRPLKCR.g01 (geometry) --- (continued)

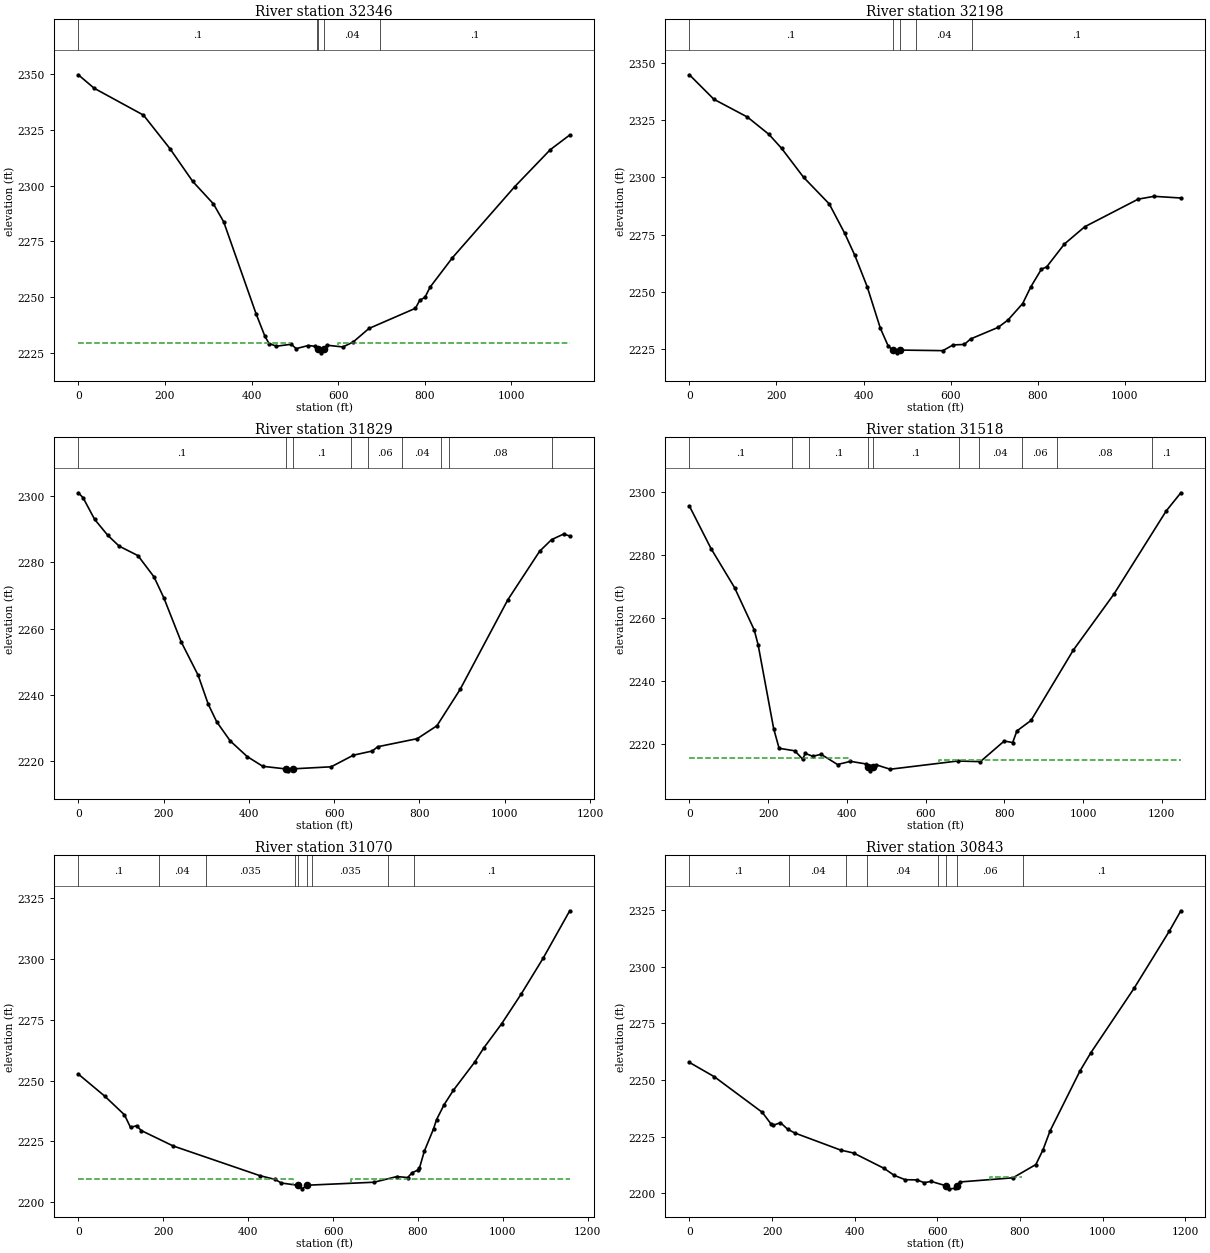
Type RM Length L Ch R = 1 ,32346   ,168.6,148.2,134.3
XS GIS Cut Line= 4
     2106953.058       183987.13     2106687.216      184446.114
     2106641.643      184443.944     2106325.887      184905.098
#Sta/Elev= 30
       0  2349.7    36.7 2343.65   150.5  2331.6   211.4 2316.62   264.2 2301.87
   312.1 2291.76   335.8  2283.7   410.5 2242.49     431 2232.36   440.5 2229.13
   457.6 2227.93   491.7  2228.8   503.1 2226.84   531.3 2228.24   547.6 2227.87
  553.172226.609   560.9 2224.95  567.252226.611     574 2228.38     611 2227.59
   634.6 2229.78   671.1 2235.87   778.6 2244.94   788.6 2248.56   800.5 2249.82
   812.4 2254.42   864.1 2267.64  1007.5 2299.43  1090.1 2316.12  1134.9 2322.68
#Mann= 5 ,-1 , 0
       0      .1       0  550.41     .04       0  553.17    .045       0
  567.25     .04       0  696.04      .1       0
#XS Ineff= 2 , 0
          489.74 2229.37   598.7         2229.28
Permanent Ineff=
       F       F
Bank Sta=553.17,567.25
XS Rating Curve= 0 ,0
Exp/Cntr=0.5,0.3

Type RM Length L Ch R = 1 ,32198   ,364.5,369.6,365.4
XS GIS Cut Line= 2
     2106862.613      183933.822     2106202.891       184849.62
#Sta/Elev= 30
       0 2344.85    56.3 2334.14   133.2 2326.38   182.5 2318.84   211.8 2312.69
   262.4 2300.01   321.2 2288.41   356.5 2275.64     380 2265.91   408.2  2252.3
   438.7 2234.01   456.7 2226.27  466.952224.578   476.3 2223.34  482.992224.553
   582.2  2224.3   605.6  2226.8   631.5    2227   645.6 2229.39     709 2234.46
   731.6 2237.66   765.4 2244.88   784.2 2252.19   808.4 2259.88   820.6 2260.91
     861 2270.84   907.8 2278.42  1030.8 2290.51  1067.2 2291.73  1128.7    2291
#Mann= 5 ,-1 , 0
       0      .1       0  466.95    .045       0  482.99      .1       0
     520     .04       0     650      .1       0
Bank Sta=466.95,482.99
XS Rating Curve= 0 ,0
Exp/Cntr=0.3,0.1

Type RM Length L Ch R = 1 ,31829   ,312.4,310.4,305.2
XS GIS Cut Line= 2
     2106563.134      183734.169     2105914.263       184686.86
#Sta/Elev= 30
       0 2301.01    11.1 2299.54    38.3 2292.99      69  2288.2    95.9 2284.91
   139.9 2282.06   177.7 2275.62   200.8 2269.27   241.4 2256.02     281    2246
   304.8 2237.23   324.7 2231.92   356.4 2226.16   396.1 2221.45   432.7 2218.51
  486.952217.711   492.2 2217.14   503.3 2217.74   593.2 2218.36   645.2 2221.86
   689.9 2223.13     702  2224.4   795.2 2226.85   841.2 2230.74   895.5 2241.68
  1007.4 2268.72    1082 2283.36    1110 2286.87  1138.4 2288.56  1152.7 2287.98
#Mann= 9 ,-1 , 0
       0      .1       0  486.95    .045       0   503.3      .1       0
     640    .035       0     680     .06       0     760     .04       0
     850    .035       0     870     .08       0    1110      .1       0
Bank Sta=486.95,503.3
XS Rating Curve= 0 ,0
Exp/Cntr=0.3,0.1

Type RM Length L Ch R = 1 ,31518   ,426,448.4,416.5
XS GIS Cut Line= 3
     2106530.582      183708.127     2106239.784       183755.87
     2105860.009      184630.436
#Sta/Elev= 30
       0 2295.63    54.9 2282.14   114.6 2269.75   164.7 2256.28   174.6 2251.53
     214 2224.96   227.8 2218.72   267.7 2217.92   287.7 2215.26   294.3 2217.09
   313.2 2216.19   334.7  2216.8   376.2 2213.57   409.1 2214.57   449.1 2213.74
  453.822212.778   459.9 2211.56   466.9 2212.89   474.2 2213.48   509.9 2212.07
   681.4 2214.68     739 2214.48   799.6 2221.03   821.1 2220.54   831.8 2224.24
   867.6 2227.55   974.9 2249.86  1077.9 2267.61    1211 2294.08  1248.2 2299.85
#Mann= 10 ,-1 , 0
       0      .1       0     260    .035       0  304.69      .1       0
  453.82    .045       0   466.9      .1       0  684.69    .035       0
  734.69     .04       0  844.69     .06       0  934.69     .08       0
 1174.69      .1       0
#XS Ineff= 2 , 0
             409 2215.61  634.39         2215.11
Permanent Ineff=
       F       F
Bank Sta=453.82,466.9
XS Rating Curve= 0 ,0
Exp/Cntr=0.3,0.1

Type RM Length L Ch R = 1 ,31070   ,211.8,226.4,197.3
XS GIS Cut Line= 2
     2106107.405      183397.798     2105640.825      184456.825
#Sta/Elev= 30
       0 2252.66    62.1  2243.6   108.7 2235.89     123 2230.69   137.4 2231.42
   148.1 2229.43   223.4 2223.07   427.9 2210.83   463.6 2209.29     478 2207.82
  516.242206.906   527.2 2205.42  538.222206.906   696.5 2208.14   750.4 2210.48
   775.5 2210.07   786.3 2212.06   800.6 2213.22   803.5 2214.01     815 2220.99
   836.5 2230.08   843.6 2233.89   861.6  2240.1   883.2 2245.97   933.3 2257.54
   954.8  2263.4   997.2 2273.43  1043.2 2285.67  1094.7 2300.37  1157.3 2319.88
#Mann= 9 ,-1 , 0
       0      .1       0     190     .04       0     300    .035       0
     510      .1       0  516.24    .045       0  538.22      .1       0
     550    .035       0     730     .06       0     790      .1       0
#XS Ineff= 2 ,-1
       0  506.52 2209.48  643.32  1157.2 2209.39
Permanent Ineff=
       F       F
Bank Sta=516.24,538.22
XS Rating Curve= 0 ,0
Exp/Cntr=0.5,0.3

Type RM Length L Ch R = 1 ,30843   ,40.3,45.1,48.6
XS GIS Cut Line= 4
2106075.77508504183389.114509762 2105740.1841426183762.937331727
2105750.09611136183937.1047828692105595.75259775184425.623243391
#Sta/Elev= 30
       0 2257.75    60.1 2251.45   176.2 2235.73   198.2 2230.41   202.6 2229.97
   220.3 2231.16   237.9 2228.23   254.9  2226.6   365.8 2219.06   397.3 2217.75
     471 2210.98   495.5  2207.9   522.1 2205.97   550.3 2205.89   568.2 2204.66
   584.7 2205.22   621.62203.257   627.3 2201.94   643.7 2202.16  648.32 2203.27
   653.6 2204.96   782.9 2206.81   838.3 2212.67   855.5 2219.13   872.7 2227.55
   944.9 2253.93   971.1 2261.95  1075.8 2290.43  1161.2  2315.7  1189.1 2324.69
#Mann= 8 ,-1 , 0
       0      .1       0     240     .04       0     380    .035       0
     430     .04       0  602.36     .06       0   621.6    .045       0
  648.32     .06       0  806.81      .1       0
#XS Ineff= 3 ,-1
       0  618.14  2203.3  652.45  720.17 2203.47   728.2  804.53 2207.11
Permanent Ineff=
       F       F       F
Bank Sta=621.6,648.32
XS Rating Curve= 0 ,0
Exp/Cntr(USF)=0,0
Exp/Cntr=0.5,0.3

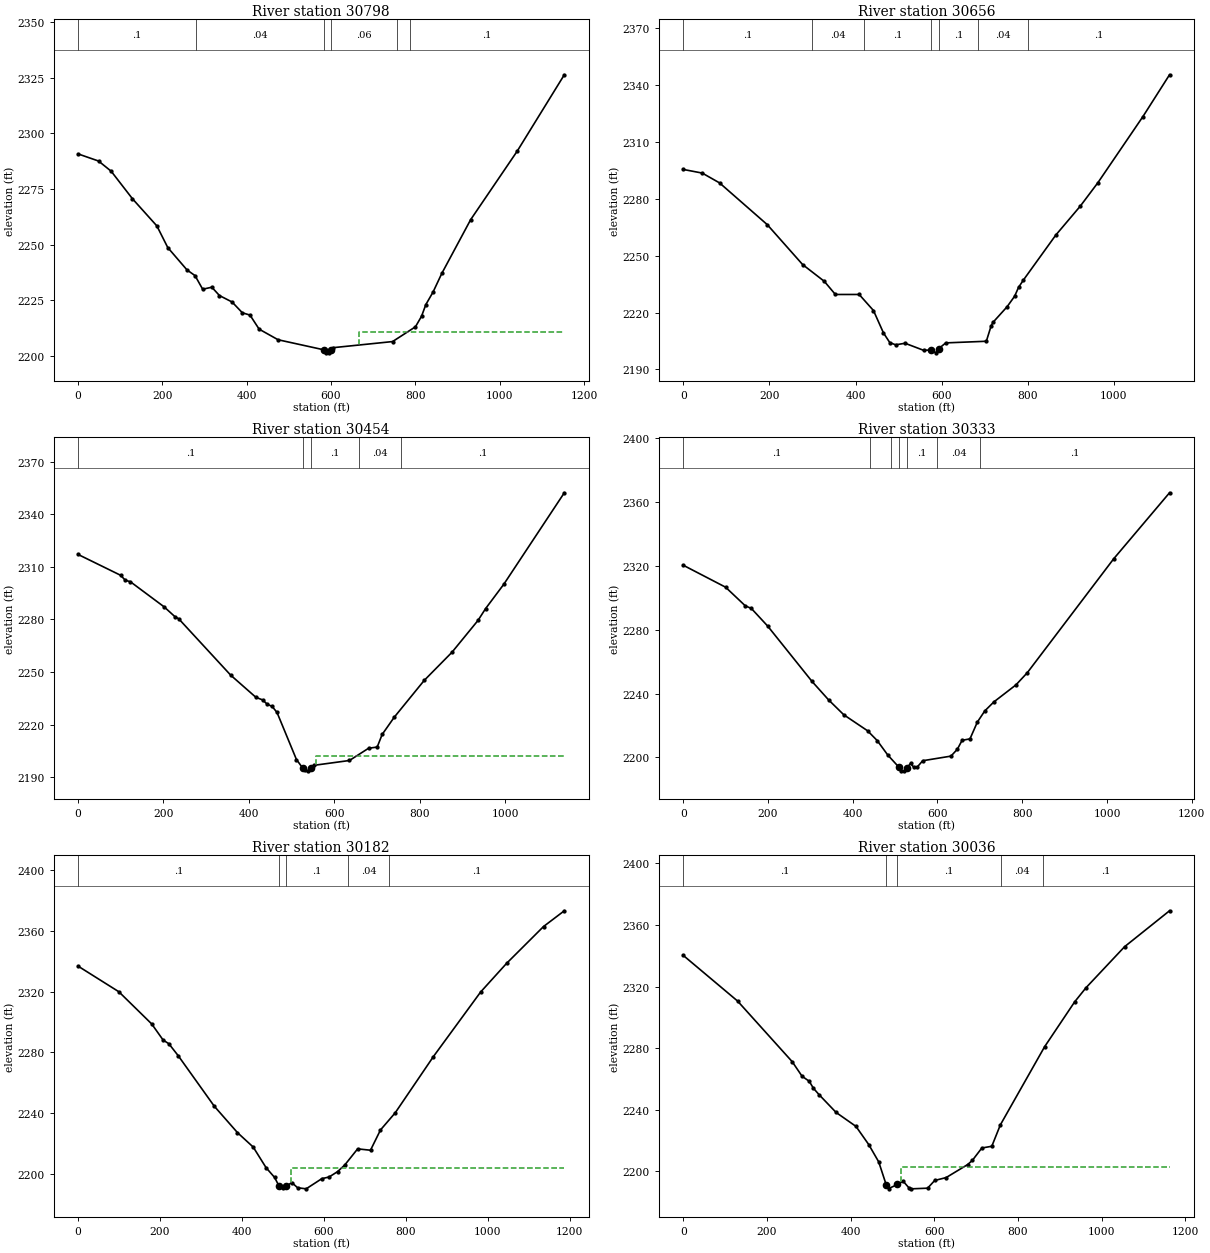
Type RM Length L Ch R = 1 ,30798   ,124.2,142.7,158.9
XS GIS Cut Line= 4
2105903.02362944183321.1467239512105711.86423184183731.785429897
2105711.86423184183965.4246936242105574.51266468184411.463288014
#Sta/Elev= 30
       0 2290.73    48.6 2287.53    78.5 2282.96   129.1 2270.57     187 2258.37
   212.8 2248.66   258.4 2238.62   277.5 2236.05   295.6 2229.94   317.3 2230.85
   335.4  2227.1   365.3 2224.21   389.7 2219.36   407.8 2218.33   429.5 2212.01
   474.4 2207.25   582.7 2202.74   589.2 2201.37   595.7 2201.48  600.42 2202.79
   605.5  2203.7     746 2206.43   800.2 2213.06   814.6 2217.76   824.9 2223.05
     842 2228.68   862.7 2237.03   931.2  2261.2  1041.7    2292  1153.3 2326.27
#Mann= 6 ,-1 , 0
       0      .1       0     280     .04       0   582.7    .045       0
  600.42     .06       0  756.59     .04       0  786.59      .1       0
#XS Ineff= 2 , 0
          579.39 2202.84  667.05         2210.51
Permanent Ineff=
       F       F
Bank Sta=582.7,600.42
XS Rating Curve= 0 ,0
Exp/Cntr(USF)=0,0
Exp/Cntr=0.5,0.3

Type RM Length L Ch R = 1 ,30656   ,207.8,201.7,190.8
XS GIS Cut Line= 4
2105881.40866594  183300.50647972105647.71501206183759.547585537
2105488.37842986183887.7755969192105332.07683019184266.389666031
#Sta/Elev= 30
       0 2295.49    44.1 2293.57    84.3 2288.39     195 2266.38   277.2  2245.3
   327.5 2236.46   353.3 2229.51   408.5 2229.52   441.7 2221.05     465  2209.2
   479.7  2204.1   493.2 2202.96   515.1 2203.77   558.2 2200.05   576.32200.238
   586.2 2198.72   592.82200.852   609.6 2203.97   703.8 2204.83   714.8 2212.84
     719 2214.74   751.9 2223.01   769.5 2228.58   778.6 2233.25   789.5 2237.01
     865 2260.83   921.8 2276.08   962.9 2288.51  1067.4 2323.38  1129.2 2345.44
#Mann= 7 ,-1 , 0
       0      .1       0     300     .04       0     420      .1       0
   576.3    .045       0   592.8      .1       0   685.1     .04       0
  799.63      .1       0
Bank Sta=576.3,592.8
XS Rating Curve= 0 ,0
Exp/Cntr(USF)=0,0
Exp/Cntr=0.3,0.1

Type RM Length L Ch R = 1 ,30454   ,123.4,121.4,121.7
XS GIS Cut Line= 3
     2105735.924      183194.184     2105469.921      183660.816
     2105234.854      184214.898
#Sta/Elev= 30
       0 2317.09    99.6 2305.21   110.9 2302.32   122.3 2301.57   201.6  2287.2
     228 2281.36   235.6 2280.44   357.6 2248.22   416.8 2235.56   432.2 2234.14
   443.3 2231.62   454.6 2230.42   466.1 2226.95   511.6 2200.11  526.182195.287
   530.8 2193.98   537.7 2193.67  546.742195.287   551.9 2196.79   635.7 2199.57
   680.7 2206.57   700.7 2207.22   712.3  2214.4   740.8  2224.3   810.8 2245.23
   875.9  2261.3   936.8 2279.44   954.6 2286.19   997.4 2300.12    1139 2352.25
#Mann= 5 ,-1 , 0
       0      .1       0  526.18    .045       0  546.74      .1       0
  657.12     .04       0  757.12      .1       0
#XS Ineff= 2 , 0
                           558.1         2202.21
Permanent Ineff=
       F       F
Bank Sta=526.18,546.74
XS Rating Curve= 0 ,0
Exp/Cntr=0.3,0.1

Type RM Length L Ch R = 1 ,30333   ,152.9,151,150
XS GIS Cut Line= 2
2105572.50344083183123.4866488872105114.54997448184175.738818169
#Sta/Elev= 30
       0 2320.39    99.9 2306.64   146.4 2294.97   160.7 2293.33   199.1 2282.33
   303.9 2247.62   343.2    2236     379  2226.7   434.9 2216.73   457.7 2210.59
   482.8 2201.48   508.32194.089   514.6  2191.8   522.1 2191.62   527.22193.333
   536.4 2196.25   543.6 2193.98     552 2193.94   565.1 2197.95   631.8 2200.84
   646.8 2205.13   658.1 2210.73   676.7 2211.65   694.1 2222.17   711.6 2229.14
   733.2 2234.82   785.2 2245.45     812 2253.09  1015.7 2324.38  1147.6 2365.77
#Mann= 7 ,-1 , 0
       0      .1       0     440     .06       0     490      .1       0
   508.3    .045       0   527.2      .1       0     600     .04       0
     700      .1       0
Bank Sta=508.3,527.2
XS Rating Curve= 0 ,0
Exp/Cntr(USF)=0,0
Exp/Cntr=0.3,0.1

Type RM Length L Ch R = 1 ,30182   ,156.9,146.1,133.4
XS GIS Cut Line= 2
      2105406.45      183052.745     2105000.634      184168.197
#Sta/Elev= 30
       0 2336.82    99.5 2319.94   179.8 2298.71   207.7 2288.08   221.6 2285.67
   244.2 2277.89   332.5  2244.5   389.2 2227.06   427.6 2217.55   459.2 2203.89
   479.7 2197.57  491.212191.585   500.1  2190.7   507.8 2191.79   521.9 2194.14
   535.9 2190.75   556.8 2190.02   595.2 2196.75   612.7  2197.8   633.6 2201.38
   651.1 2205.75   682.5 2216.36   713.9 2215.47   738.3 2228.84   774.1 2240.08
   867.5 2277.22   982.7 2319.74  1045.9 2338.58  1136.3 2362.91    1187 2373.29
#Mann= 5 ,-1 , 0
       0      .1       0  491.21    .045       0   507.8      .1       0
     660     .04       0     760      .1       0
#XS Ineff= 2 , 0
                           519.2         2203.53
Permanent Ineff=
       F       F
Bank Sta=491.21,507.8
XS Rating Curve= 0 ,0
Exp/Cntr=0.3,0.1

Type RM Length L Ch R = 1 ,30036   ,249.7,269.6,294.1
XS GIS Cut Line= 4
2105200.70977453183035.011669811 2105088.4833335183475.284630789
2105123.01454613183585.3528710332104961.14948694184155.117879358
#Sta/Elev= 30
       0 2340.22   129.7 2310.58   260.3 2271.16     284 2261.66     301 2258.43
   311.1 2253.85   324.7 2249.66   365.3 2238.14   412.7 2229.09   443.2 2217.29
   467.1 2206.01   484.8 2191.29   491.1 2188.71   511.8 2191.35   525.5 2193.45
   539.3 2189.15   545.2  2188.5   583.9 2188.93   600.9 2193.94   628.2 2195.82
   679.4 2204.24     691 2207.04   713.5 2215.04   737.3 2216.17   757.8  2230.1
   863.5 2280.86   935.3 2310.02   962.4  2319.2  1054.5 2345.84    1162 2369.22
#Mann= 5 ,-1 , 0
       0      .1       0   484.8    .045       0   511.8      .1       0
  759.71     .04       0  859.71      .1       0
#XS Ineff= 2 , 0
                          520.92         2202.43
Permanent Ineff=
       F       F
Bank Sta=484.8,511.8
XS Rating Curve= 0 ,0
Exp/Cntr(USF)=0,0
Exp/Cntr=0.5,0.3

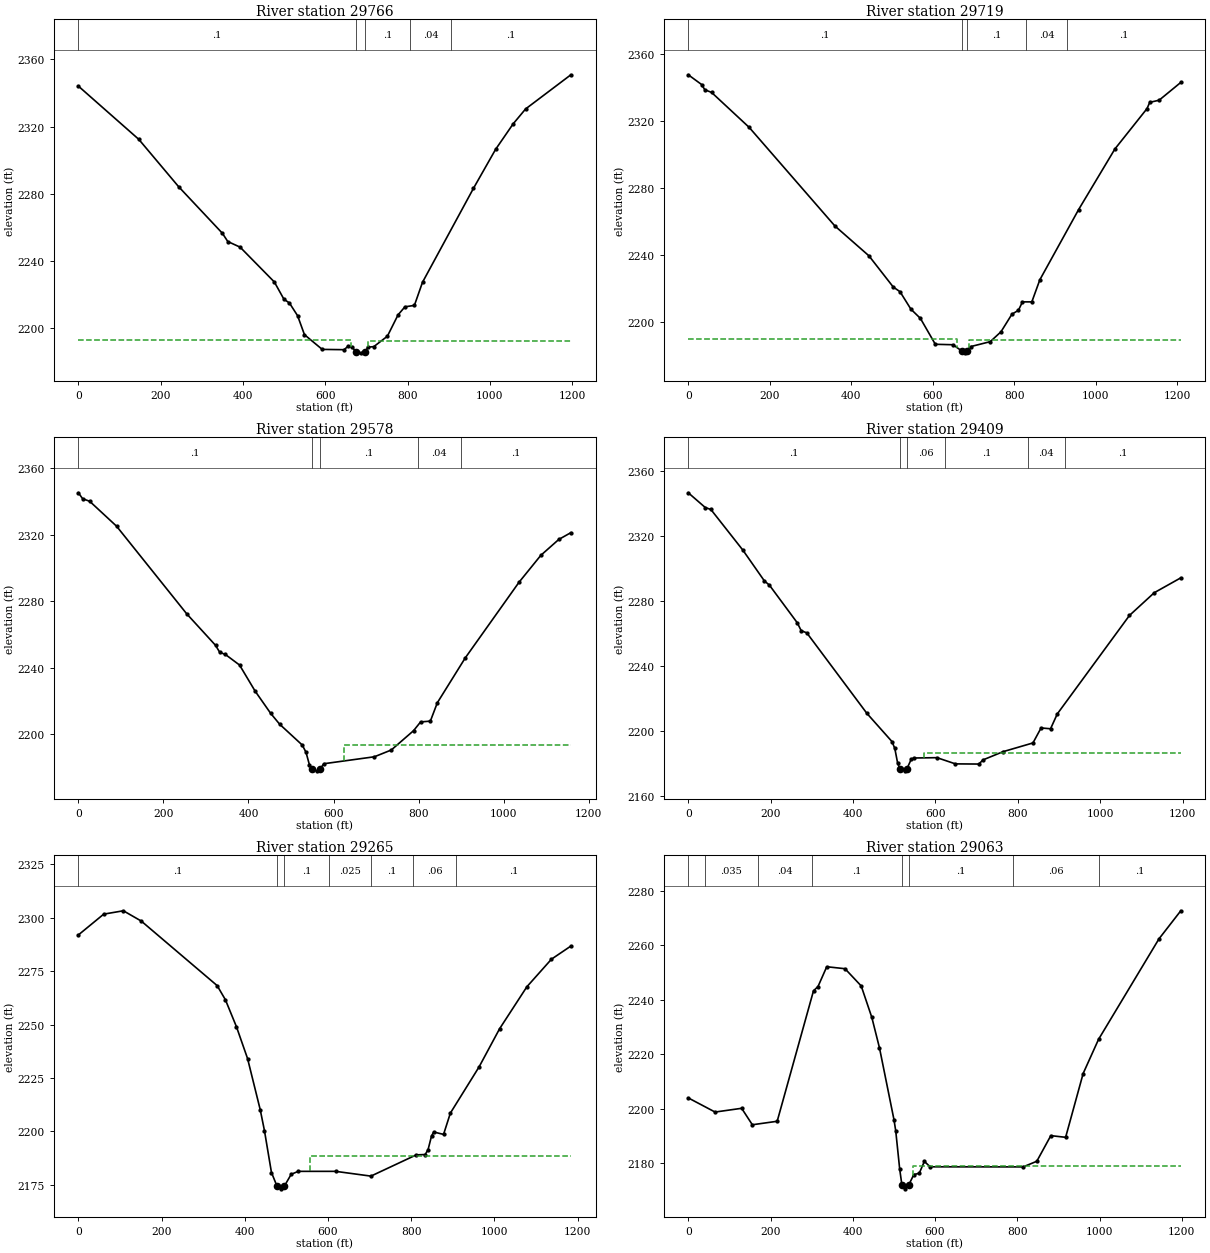
Type RM Length L Ch R = 1 ,29766   ,34.2,46.5,45.9
XS GIS Cut Line= 4
     2105049.813      182998.034     2104937.834      183664.701
     2104898.772       183676.42     2104867.522      184155.587
#Sta/Elev= 30
       0 2344.13   146.9 2312.35   243.4 2284.18   349.9 2256.35   363.2 2251.38
   393.1 2248.03   476.3 2227.25   499.7 2216.92   512.9 2214.73   532.8 2207.12
   549.5  2195.8   592.7 2187.01   645.9 2186.84   656.1 2189.03   665.9 2188.39
  673.832185.604     687 2184.96  697.322185.604   703.6 2188.34   718.1 2188.67
     751 2194.86   777.1 2207.67   793.7 2212.42   816.7 2213.27   836.4 2227.07
   960.3 2283.14    1014 2306.35  1056.7 2321.59  1086.9 2330.48    1197 2350.88
#Mann= 5 ,-1 , 0
       0      .1       0  673.83    .045       0  697.32      .1       0
  806.79     .04       0  906.79      .1       0
#XS Ineff= 2 , 0
          662.93 2192.33  704.73         2192.27
Permanent Ineff=
       F       F
Bank Sta=673.83,697.32
XS Rating Curve= 0 ,0
Exp/Cntr=0.5,0.3

Type RM Length L Ch R = 1 ,29719   ,160.1,141.3,122.8
XS GIS Cut Line= 4
      2105027.07      182974.944     2104917.695      183624.684
     2104878.633      183636.403     2104846.081      184144.215
#Sta/Elev= 30
       0 2347.85    32.6 2342.03    40.6 2338.91    57.2 2337.28   149.4 2316.37
   359.8 2257.33   443.2 2239.49     503 2220.78   519.6 2217.97   546.3 2207.52
   569.6    2202   606.2  2186.5   649.4 2186.23  670.78 2182.57   679.1 2181.38
  684.222182.571   692.8 2185.11     741 2188.08   767.3 2193.98   794.2 2204.52
   810.1 2206.85     820 2211.89     843 2211.89   862.7 2225.14   957.9 2267.19
  1046.8 2303.42  1125.7 2327.62  1132.3 2331.35  1155.3 2332.62  1208.5 2343.27
#Mann= 5 ,-1 , 0
       0      .1       0  670.78    .045       0  684.22      .1       0
  829.66     .04       0  929.66      .1       0
#XS Ineff= 2 , 0
          660.23 2189.44   687.9         2189.28
Permanent Ineff=
       F       F
Bank Sta=670.78,684.22
XS Rating Curve= 0 ,0
Exp/Cntr=0.5,0.3

Type RM Length L Ch R = 1 ,29578   ,169.2,169.6,165.6
XS GIS Cut Line= 4
2104894.24526248182985.3730516612104820.86643565183438.595217374
2104758.27861277183680.3137057542104741.01300645184129.219469888
#Sta/Elev= 30
       0 2345.17      10 2341.62    26.7 2340.03    89.8 2325.07   254.8 2272.32
   322.5 2253.38   332.4 2249.17   345.7 2247.86     379  2241.5   415.5 2225.86
   452.1 2212.45   473.3 2205.88   526.5 2193.34   535.3 2188.98   543.4 2181.37
  549.362179.065   560.4 2177.82  568.652179.065   577.3  2182.1     696 2186.28
   735.8 2190.36   788.3 2202.02   804.7 2207.25   827.7 2207.74   844.1  2218.8
   909.7 2245.77  1036.1  2291.3  1087.4 2307.51  1129.7 2317.09  1158.1 2321.17
#Mann= 5 ,-1 , 0
       0      .1       0  549.36    .045       0  568.65      .1       0
  798.81     .04       0  898.81      .1       0
#XS Ineff= 2 , 0
                          625.79         2193.11
Permanent Ineff=
       F       F
Bank Sta=549.36,568.65
XS Rating Curve= 0 ,0
Exp/Cntr(USF)=0,0
Exp/Cntr=0.3,0.1

Type RM Length L Ch R = 1 ,29409   ,152.3,143.3,138.3
XS GIS Cut Line= 3
     2104767.335      182964.988     2104640.285      183473.197
     2104645.197      184144.697
#Sta/Elev= 30
       0 2346.51    41.4  2337.4    54.9 2336.22   132.7 2311.13   184.8  2292.2
   196.9 2289.64   264.6 2266.42   274.1 2261.59   287.7 2260.23   433.5 2210.66
   494.5 2193.25   501.3 2189.03   508.1 2180.09  513.992176.348   524.9 2175.25
  530.322176.347   541.3 2182.44   547.9 2183.16   603.7 2183.36   648.4 2179.54
   705.4 2179.43   715.2 2181.97   764.1 2187.06   836.6 2192.43   856.3 2201.67
   879.3 2201.16   895.7 2210.32  1070.9 2270.98    1131 2284.96  1195.4 2294.12
#Mann= 6 ,-1 , 0
       0      .1       0  513.99    .045       0  530.32     .06       0
  623.85      .1       0  823.85     .04       0  913.85      .1       0
#XS Ineff= 2 , 0
                          572.98         2186.42
Permanent Ineff=
       F       F
Bank Sta=513.99,530.32
XS Rating Curve= 0 ,0
Exp/Cntr=0.3,0.1

Type RM Length L Ch R = 1 ,29265   ,211.6,202.6,193.9
XS GIS Cut Line= 5
2104421.59928967182983.2148508722104475.55430939183371.690992912
2104512.24372281183518.4486465712104607.20455753183829.229560202
2104617.99556148184144.326875412
#Sta/Elev= 30
       0 2291.88      61 2301.62   108.2 2303.19   151.2 2298.38   333.5 2268.21
   353.4 2261.58   379.9 2248.99   406.7 2234.06   437.1 2210.16   447.2 2200.42
   464.1 2180.79  477.342174.445   487.2 2173.15  495.172174.444   511.5 2179.94
   528.4 2181.33   618.3 2181.33   703.1  2179.1     812 2189.02   833.5  2189.2
   840.4 2191.43   848.8 2197.86   854.1 2199.73   877.7 2198.61   894.1 2208.58
     963 2230.15  1012.3 2247.99  1077.9 2267.64    1137 2280.55  1183.7 2286.69
#Mann= 7 ,-1 , 0
       0      .1       0  477.34    .045       0  495.17      .1       0
  603.48    .025       0  703.48      .1       0  803.48     .06       0
  908.44      .1       0
#XS Ineff= 2 , 0
                          557.02         2188.61
Permanent Ineff=
       F       F
Bank Sta=477.34,495.17
XS Rating Curve= 0 ,0
Exp/Cntr(USF)=0,0
Exp/Cntr=0.3,0.1

Type RM Length L Ch R = 1 ,29063   ,225.2,229.8,236.7
XS GIS Cut Line= 3
     2103971.988      183150.402     2104403.846      183634.343
     2104555.878      184161.728
#Sta/Elev= 30
       0 2204.01    65.2 2198.82   129.8  2200.2   155.8 2194.16   216.2 2195.44
   304.5  2243.3   315.4 2244.84   336.7 2252.12   381.1 2251.39   420.5 2245.07
   446.3 2233.53   464.9 2222.36   500.1 2196.06   504.4 2191.95   514.1 2177.84
  519.382172.124   526.4 2170.66  536.182172.123   548.4 2175.89   561.6 2176.37
   574.1 2180.73     588 2178.74   814.2 2178.71   847.4 2180.77   881.5 2190.17
   917.5 2189.56   960.1 2212.96   997.6  2225.5  1144.4 2262.33  1197.5 2272.64
#Mann= 8 ,-1 , 0
       0      .1       0      40    .035       0     170     .04       0
     300      .1       0  519.38    .045       0  536.18      .1       0
  788.61     .06       0  998.61      .1       0
#XS Ineff= 2 , 0
                          546.13         2179.05
Permanent Ineff=
       F       F
Bank Sta=519.38,536.18
XS Rating Curve= 0 ,0
Exp/Cntr=0.3,0.1

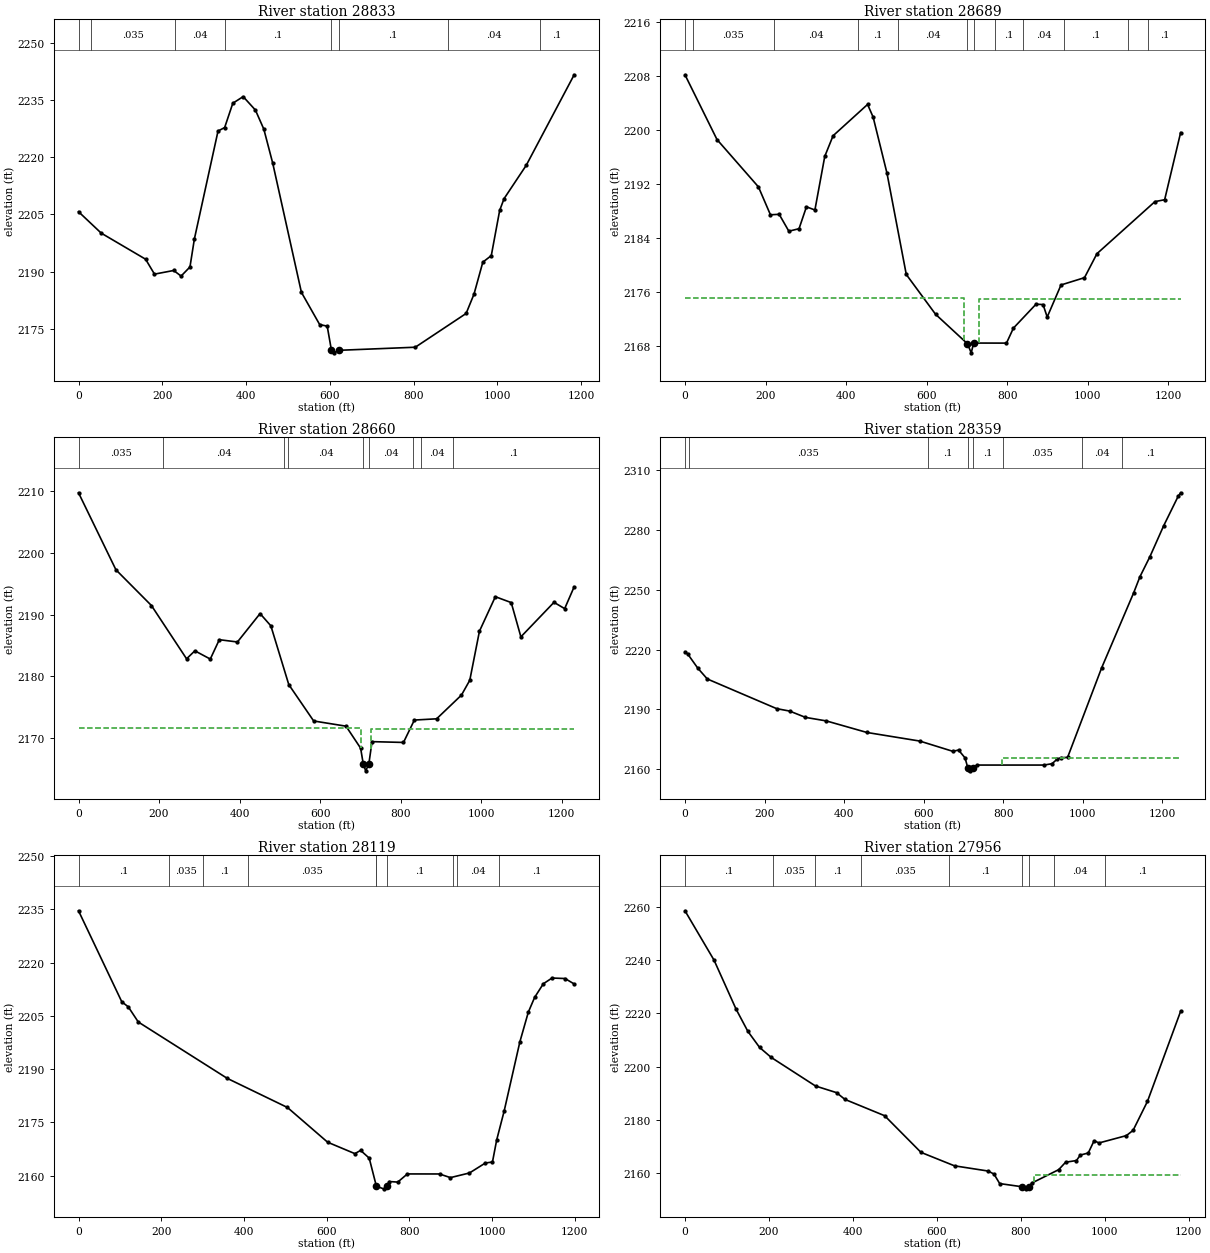
Type RM Length L Ch R = 1 ,28833   ,137.1,143.5,142.2
XS GIS Cut Line= 4
2103938.16231291183151.5545124232104115.13477761183598.302075768
2104281.31623837183952.2470051812104402.17548256184239.287710133
#Sta/Elev= 30
       0 2205.71    54.2  2200.1   160.1 2193.27   181.3 2189.36   227.2 2190.32
   244.8 2188.85     266 2191.24   276.6  2198.6     333 2226.84   348.8 2227.75
   368.3 2234.12     393 2235.85   422.2 2232.33   442.3 2227.33   463.6 2218.39
     532 2184.59   575.5 2176.17   593.6 2175.73   603.6 2169.47   609.5 2168.75
   620.6 2169.41   803.8 2170.22   925.1 2179.06   943.9 2184.11     965  2192.5
   985.2 2194.21  1005.2 2206.05  1015.7 2209.13  1068.5 2217.84    1183 2241.57
#Mann= 8 ,-1 , 0
       0      .1       0      30    .035       0     230     .04       0
     350      .1       0   603.6    .045       0   620.6      .1       0
  881.54     .04       0 1101.54      .1       0
Bank Sta=603.6,620.6
XS Rating Curve= 0 ,0
Exp/Cntr(USF)=0,0
Exp/Cntr=0.5,0.3

Type RM Length L Ch R = 1 ,28689   ,31.6,29.5,28.9
XS GIS Cut Line= 2
     2103895.733       183162.01     2104255.108      184339.093
#Sta/Elev= 30
       0 2208.13    79.5 2198.54   182.4 2191.53   212.2  2187.4   233.9 2187.47
   257.9 2184.97   283.2 2185.34   301.6 2188.58   322.6 2188.11   347.1 2196.05
   367.7  2199.1   453.4 2203.74   467.2 2201.86   501.5 2193.58   549.5 2178.56
   622.2 2172.67  701.392168.306   710.7 2166.96   716.8 2168.41   798.3  2168.4
   815.5 2170.62   871.6 2174.16   889.1 2174.11   899.4 2172.26   933.7 2177.01
     992 2178.09  1022.9 2181.64  1166.9 2189.35    1191 2189.63  1230.7 2199.57
#Mann= 12 ,-1 , 0
       0      .1       0      20    .035       0     220     .04       0
     430      .1       0     530     .04       0  701.39    .045       0
   716.8     .04       0     770      .1       0     840     .04       0
     940      .1       0    1100     .04       0    1150      .1       0
#XS Ineff= 2 , 0
          691.98 2175.01  730.09          2174.9
Permanent Ineff=
       F       F
Bank Sta=701.39,716.8
XS Rating Curve= 0 ,0
Exp/Cntr=0.5,0.3

Type RM Length L Ch R = 1 ,28660   ,294.1,301.3,307.2
XS GIS Cut Line= 2
     2103870.994      183175.031     2104230.369      184352.114
#Sta/Elev= 30
       0 2209.69    92.9 2197.24   181.1 2191.46   268.3 2182.85   288.9 2184.14
   327.2 2182.81   349.6 2185.94   394.6 2185.57   450.8 2190.16   477.6 2188.18
   522.1 2178.68   583.9  2172.8   664.2 2171.96   700.5  2168.4  707.092165.827
   713.1 2164.74  720.812165.828   728.8 2169.46   806.9 2169.33   833.9 2172.95
   889.2 2173.15   950.9 2176.99   971.5 2179.38   995.5 2187.31    1035 2192.89
  1074.4 2191.94  1098.4  2186.4  1180.6 2191.98  1207.1 2190.96  1230.7 2194.49
#Mann= 9 ,-1 , 0
       0    .035       0     210     .04       0     510      .1       0
     520     .04       0  707.09    .045       0  720.81     .04       0
     830     .06       0     850     .04       0     930      .1       0
#XS Ineff= 2 , 0
           700.5 2171.65  726.25         2171.55
Permanent Ineff=
       F       F
Bank Sta=707.09,720.81
XS Rating Curve= 0 ,0
Exp/Cntr=0.5,0.3

Type RM Length L Ch R = 1 ,28359   ,233.8,239.5,242.8
XS GIS Cut Line= 3
     2103845.088      183165.716      2103791.59      183882.293
     2103725.335      184405.816
#Sta/Elev= 30
       0 2218.89     6.8 2217.84    32.2 2210.72    56.1  2205.3   230.5 2190.42
   263.4 2189.19   302.9 2186.04   355.5 2184.26   457.5 2178.47   590.4 2174.16
   673.6 2169.01   687.8 2169.66   704.2 2165.73  711.062160.816   714.1 2159.44
   717.4 2159.23  725.192160.817   733.6 2162.13   902.6 2162.13   922.9  2162.8
   935.6 2165.06   945.5 2165.82   962.1 2165.99  1047.8 2210.93  1128.3 2248.55
    1144 2256.59    1169  2266.6  1203.5 2282.07  1239.9 2296.83  1246.3 2298.67
#Mann= 8 ,-1 , 0
       0      .1       0      10    .035       0     610      .1       0
  711.06    .045       0  725.19      .1       0  798.57    .035       0
  998.57     .04       0 1098.57      .1       0
#XS Ineff= 2 , 0
                          798.13          2165.8
Permanent Ineff=
       F       F
Bank Sta=711.06,725.19
XS Rating Curve= 0 ,0
Exp/Cntr=0.3,0.1

Type RM Length L Ch R = 1 ,28119   ,150.9,163.5,168.1
XS GIS Cut Line= 5
2103793.85771549183186.642444306 2103536.8692383183934.478912933
2103452.06304083183940.9036248632103421.22442357183982.021781214
  2103326.138687184236.440373633
#Sta/Elev= 30
       0  2234.6   104.7 2208.95   120.3 2207.54   144.6 2203.26   359.7 2187.38
   505.4 2179.17   602.5 2169.39   668.4 2166.17   682.3 2167.08   703.1  2164.9
   720.4    2157   737.8 2156.25   746.3 2156.91   751.7 2158.31   772.1 2158.15
   795.4 2160.45   873.1 2160.44   899.5 2159.41   945.6 2160.72   984.1 2163.53
  1001.2 2163.81  1011.4 2170.02  1029.3 2178.09  1067.5 2197.68  1087.9 2206.03
  1103.2  2210.2  1124.2 2214.03  1145.2 2215.65  1176.7 2215.51  1198.8 2213.98
#Mann= 10 ,-1 , 0
       0      .1       0     220    .035       0     300      .1       0
     410    .035       0     720      .1       0   720.4    .045       0
   746.3      .1       0  905.81     .06       0  915.81     .04       0
 1017.21      .1       0
Bank Sta=720.4,746.3
XS Rating Curve= 0 ,0
Exp/Cntr(USF)=0,0
Exp/Cntr=0.3,0.1

Type RM Length L Ch R = 1 ,27956   ,549.5,567.5,566.7
XS GIS Cut Line= 3
     2103733.273      183176.443     2103511.919      183766.721
     2103175.547      184202.919
#Sta/Elev= 30
       0 2258.63    69.3 2240.04   121.9 2221.56   149.9 2213.24   177.9 2207.18
   205.6 2203.43   311.1 2192.68   361.1 2190.19   381.2 2187.64   475.8  2181.5
   562.4 2167.71   642.3 2162.64   722.4 2160.68   736.4 2159.54     750 2155.96
   803.9 2154.75   812.2 2153.98   820.4 2154.71   826.2 2156.13   890.6  2161.2
   907.1    2164   932.9 2164.63   942.2  2166.7     961 2167.46     975 2172.09
   986.7 2171.25  1051.8 2174.01  1067.9 2175.99  1102.2 2186.92  1181.2  2220.8
#Mann= 9 ,-1 , 0
       0      .1       0     210    .035       0     310      .1       0
     420    .035       0     630      .1       0   803.9    .045       0
   820.4      .1       0  880.42     .04       0 1000.42      .1       0
#XS Ineff= 2 , 0
                          830.65          2159.1
Permanent Ineff=
       F       F
Bank Sta=803.9,820.4
XS Rating Curve= 0 ,0
Exp/Cntr=0.3,0.1

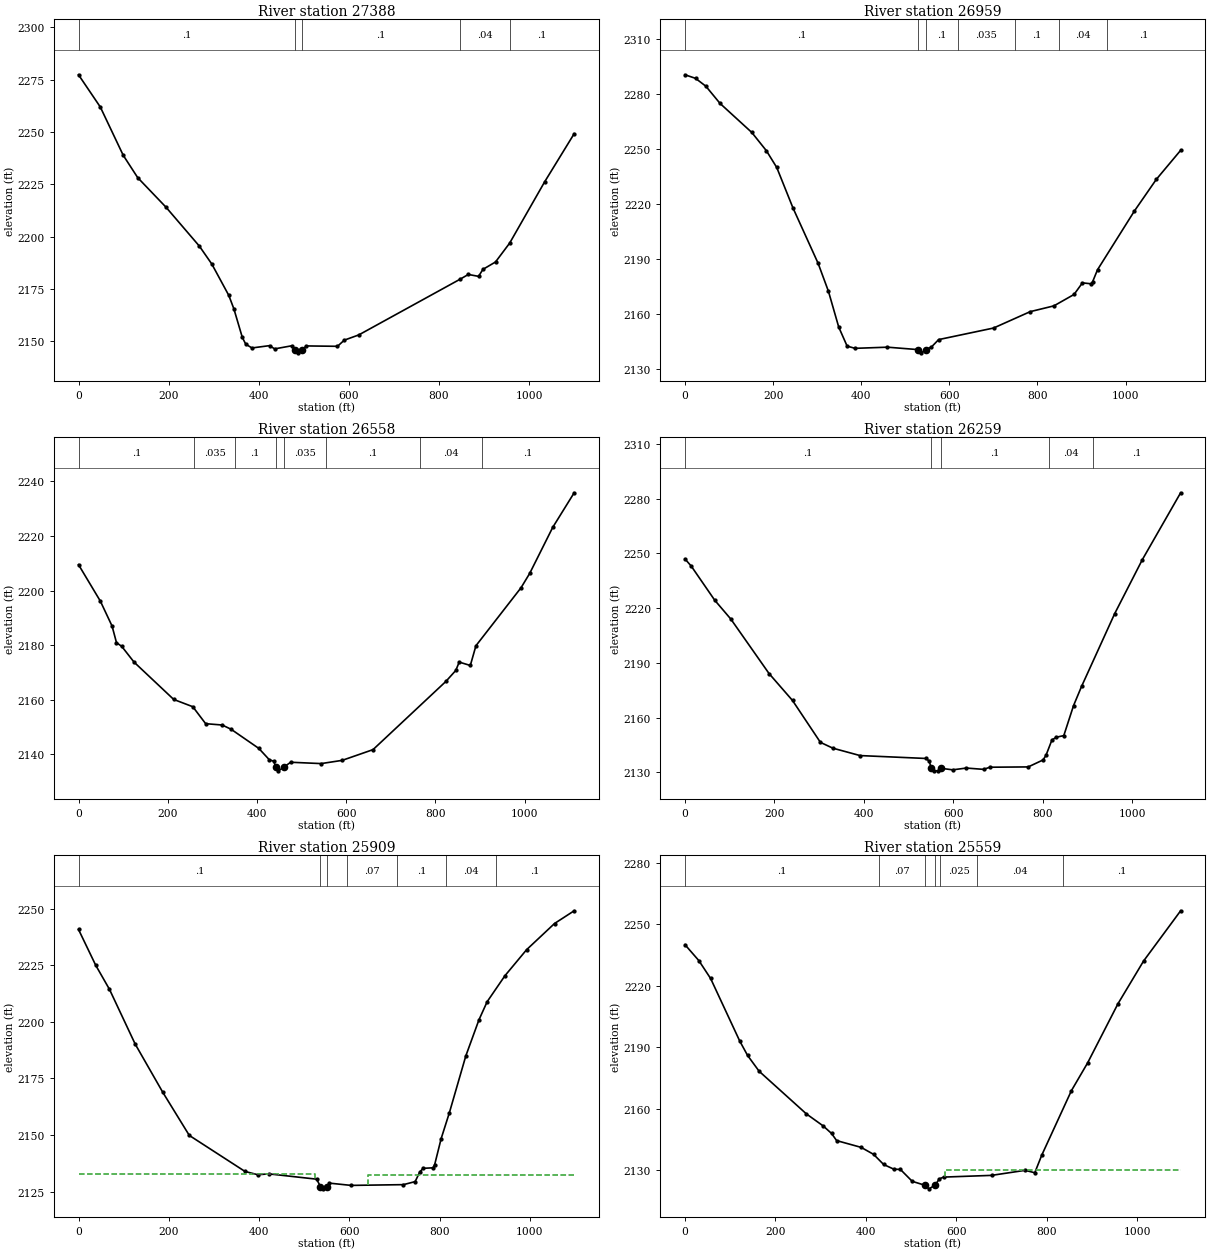
Type RM Length L Ch R = 1 ,27388   ,442.4,429.5,416.5
XS GIS Cut Line= 3
     2103585.704      183111.339     2103425.113      183337.034
     2102708.968       183742.85
#Sta/Elev= 30
       0 2277.31    48.4 2261.91    99.2 2238.88   131.4 2228.18   194.2 2214.07
   268.3 2195.47   295.9 2186.92   333.5 2171.98   344.8 2165.56   363.6 2151.87
   371.2 2148.67   384.9 2146.86     424 2147.97   435.3 2146.42     473 2147.89
  480.94 2145.75   488.1 2144.53  496.762145.749   505.2 2147.83   574.8 2147.65
   589.9 2150.59     622 2153.08     847  2179.7   865.2 2181.96   887.9 2181.05
   897.6 2184.39   925.5 2187.91     957 2196.95  1034.5 2226.16  1100.1 2249.17
#Mann= 5 ,-1 , 0
       0      .1       0  480.94    .045       0  496.76      .1       0
     847     .04       0     957      .1       0
Bank Sta=480.94,496.76
XS Rating Curve= 0 ,0
Exp/Cntr=0.3,0.1

Type RM Length L Ch R = 1 ,26959   ,406.7,400.4,381.6
XS GIS Cut Line= 3
     2103053.077      182679.886     2102942.914      183207.495
      2102645.05      183712.193
#Sta/Elev= 30
       0 2290.66    23.9 2288.72    47.4 2284.41    79.6    2275   151.7 2259.13
   184.8 2249.15   208.3    2240   245.1  2217.9   302.1 2187.68   325.6 2172.36
     349 2152.76     368  2142.4   385.9 2141.17   459.6  2141.8  529.322140.469
   536.7 2138.71  546.262140.467   559.3 2141.87   575.7 2145.94   700.3 2152.26
   783.6 2161.22   837.4 2164.38   883.1 2170.62   902.1 2176.95   921.2 2176.46
     925 2177.43   936.4 2184.14  1020.2 2216.26  1069.7 2233.47    1125 2249.37
#Mann= 7 ,-1 , 0
       0      .1       0  529.32    .045       0  546.26      .1       0
  618.99    .035       0  748.99      .1       0  848.99     .04       0
  958.99      .1       0
Bank Sta=529.32,546.26
XS Rating Curve= 0 ,0
Exp/Cntr=0.3,0.1

Type RM Length L Ch R = 1 ,26558   ,292.6,299.6,302.1
XS GIS Cut Line= 4
2102601.29039263182628.3371145222102569.56342014183042.374105552
2102679.02147524183416.7523809662102561.63167701183699.122436151
#Sta/Elev= 30
       0 2209.49    48.9 2196.13    75.2 2186.98    85.1  2180.9      97 2179.49
   124.5 2173.74   213.4 2160.05   256.2 2157.38     285 2151.16     322 2150.67
     342 2149.12   404.2 2142.09   427.7 2137.93     438 2137.35   441.92135.208
   448.2 2133.86   460.6 2135.27   475.6 2137.01   543.9 2136.52     591  2137.7
   660.2 2141.64   823.4 2166.64   845.7 2170.68   853.4 2173.75   878.3 2172.51
   890.9 2179.75     992 2201.03  1011.4 2206.28    1063 2223.16  1111.1 2235.86
#Mann= 8 ,-1 , 0
       0      .1       0     260    .035       0     350      .1       0
   441.9    .045       0   460.6    .035       0  555.25      .1       0
  765.25     .04       0   905.3      .1       0
Bank Sta=441.9,460.6
XS Rating Curve= 0 ,0
Exp/Cntr(USF)=0,0
Exp/Cntr=0.3,0.1

Type RM Length L Ch R = 1 ,26259   ,342,350,360.8
XS GIS Cut Line= 3
     2102312.684      182564.633     2102287.944      183127.601
     2102365.503      183667.464
#Sta/Elev= 30
       0 2246.97      14 2243.05    66.5 2224.36   102.7 2213.97   188.1 2184.13
   240.6 2169.36     303 2146.41   330.8 2143.22   391.7 2139.16   539.4 2137.57
     546 2136.19  551.312132.369   557.7 2130.79   565.7 2130.86   573.1 2132.17
   598.9 2131.34   629.5 2132.32   668.5 2131.59   681.7 2132.77   767.9 2132.94
   801.1 2136.76   807.7 2139.31     821 2147.74     831 2149.23   847.5 2150.11
   869.4 2166.61   887.2 2177.05   961.4    2217  1023.1 2246.53  1108.9 2283.25
#Mann= 5 ,-1 , 0
       0      .1       0  551.31    .045       0   573.1      .1       0
  813.51     .04       0  913.51      .1       0
Bank Sta=551.31,573.1
XS Rating Curve= 0 ,0
Exp/Cntr=0.3,0.1

Type RM Length L Ch R = 1 ,25909   ,345,350,347.3
XS GIS Cut Line= 3
      2102176.75      182524.053     2101977.159      183031.255
     2101737.603      183529.964
#Sta/Elev= 30
       0  2240.8    38.2 2224.97    68.6 2214.36   125.6 2190.18   186.9 2168.83
   245.5 2149.84   368.9 2133.93   397.1 2132.49   421.8 2132.86   527.6 2130.52
  536.152127.263   541.7 2126.25  550.21 2127.26   556.1 2128.77   603.9 2127.77
   719.9  2128.1   745.9 2129.44   756.3  2133.7   763.6 2135.31   785.4 2135.54
   789.1 2136.87   803.6 2148.46   821.8 2159.87   858.2 2184.95   887.3 2200.89
   905.5  2208.9     945  2220.4   992.9 2231.87  1054.8 2243.44  1098.3 2249.06
#Mann= 7 ,-1 , 0
       0      .1       0  536.15    .045       0  550.21      .1       0
  595.06     .07       0  705.06      .1       0  815.06     .04       0
  925.06      .1       0
#XS Ineff= 2 , 0
          524.81 2132.97  642.39         2132.33
Permanent Ineff=
       F       F
Bank Sta=536.15,550.21
XS Rating Curve= 0 ,0
Exp/Cntr=0.3,0.1

Type RM Length L Ch R = 1 ,25559   ,138.2,136.2,137.4
XS GIS Cut Line= 3
     2101920.306      182407.134     2101664.617      182888.374
     2101457.705      183399.362
#Sta/Elev= 30
       0 2240.09    30.7  2232.3    56.7 2223.56     121 2193.03   138.5 2185.93
     164 2178.22   268.5 2157.38   305.6  2151.5   324.1 2147.83   335.4 2144.32
   389.6 2141.01   417.1  2137.6   439.4 2132.64   461.7 2130.37   476.5 2130.21
   502.6 2124.41  529.812122.548   539.7 2120.74  553.212122.548   562.5  2125.6
   571.8 2126.48     678 2127.32   752.3 2129.79   773.6  2128.6   789.2 2137.27
   854.7 2168.75   890.4 2182.27   957.6 2211.22  1014.3 2232.12  1096.2 2256.66
#Mann= 7 ,-1 , 0
       0      .1       0     430     .07       0  529.81    .045       0
  553.21     .07       0  564.95    .025       0  644.95     .04       0
  834.95      .1       0
#XS Ineff= 2 , 0
                           576.1         2130.14
Permanent Ineff=
       F       F
Bank Sta=529.81,553.21
XS Rating Curve= 0 ,0
Exp/Cntr=0.3,0.1