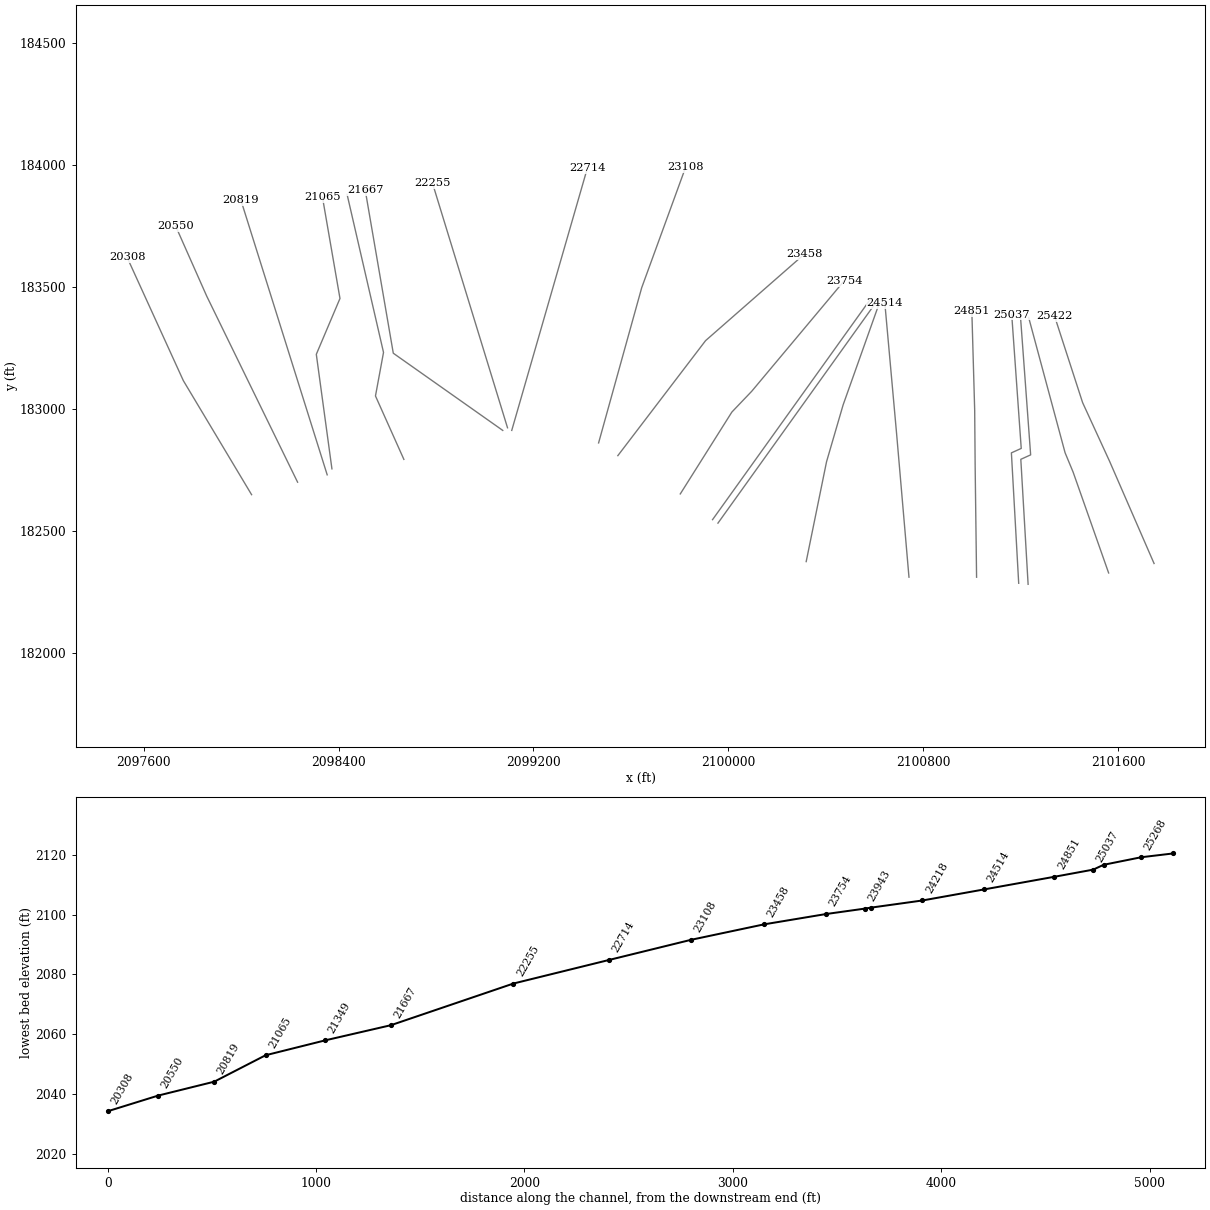
HEC-RAS study DRPLKCR.prj: DRPLKCR

--- DRPLKCR.g01 (geometry) --- (continued)

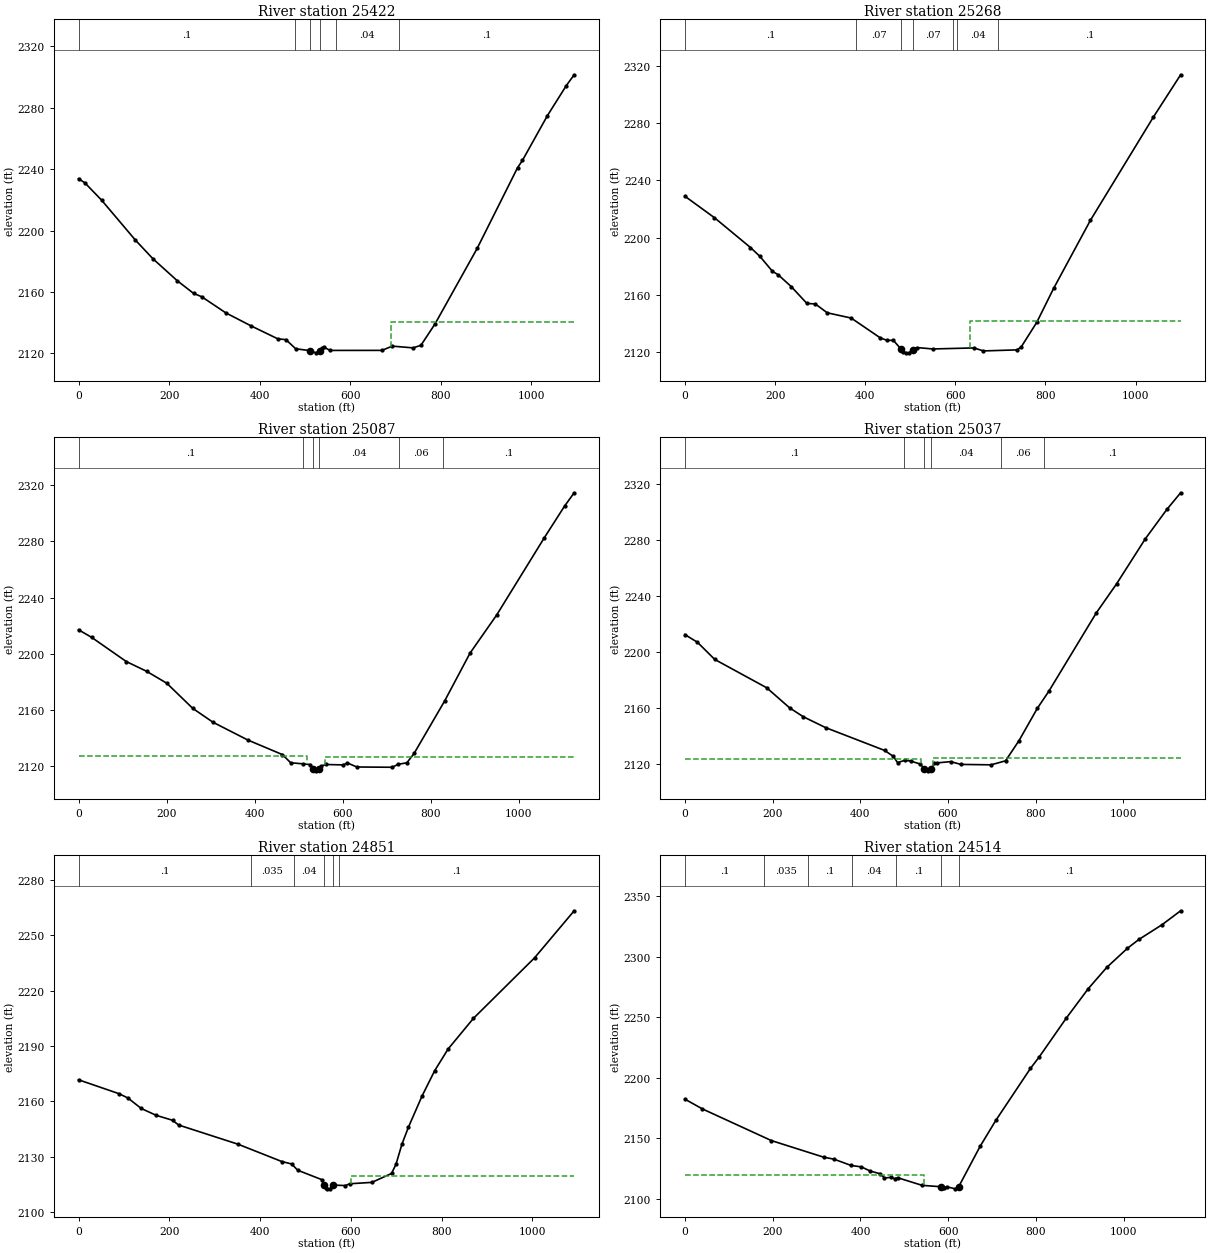
Type RM Length L Ch R = 1 ,25422   ,155.1,154.8,153.7
XS GIS Cut Line= 4
2101746.85060672182365.4819216442101564.26681996182785.036155047
2101453.55111948183025.8913631122101338.95065757183379.404652368
#Sta/Elev= 30
       0 2233.76    14.2 2230.99    50.9 2219.78   125.7 2193.72   164.5 2181.56
   218.1  2167.3   253.9  2159.1   271.8 2156.92   325.1 2146.42   381.8  2137.8
     440 2129.49   457.9 2128.98   479.5 2123.02  511.822121.787     524 2120.38
  533.452121.788   537.3 2123.65   541.4 2124.11   555.4 2121.96     670 2121.98
   692.6 2124.75   738.8 2123.61     756 2125.29   787.1  2139.2   880.2 2188.39
   969.3 2240.88   980.2 2245.68  1035.4 2274.85  1076.8 2294.26  1094.3 2301.37
#Mann= 6 ,-1 , 0
       0      .1       0  477.56     .07       0  511.82    .045       0
  533.45     .07       0  567.56     .04       0  707.56      .1       0
#XS Ineff= 2 , 0
                           689.4         2140.29
Permanent Ineff=
       F       F
Bank Sta=511.82,533.45
XS Rating Curve= 0 ,0
Exp/Cntr(USF)=0,0
Exp/Cntr=0.3,0.1

Type RM Length L Ch R = 1 ,25268   ,206.7,180.4,151.3
XS GIS Cut Line= 4
2101560.38205854 182326.634307442101414.70350527182740.361398713
 2101381.6830332182819.9990078312101232.11971851183375.519890948
#Sta/Elev= 30
       0 2228.91    65.3 2213.92   145.4 2192.97   166.3 2186.76   194.1 2176.31
   206.9 2173.86   235.9 2165.55   270.6 2153.75   289.2 2153.39   315.9 2147.17
   368.9  2143.5   433.2 2129.65   448.2 2127.87   462.4 2127.87   480.2 2121.55
   483.7 2119.91   490.8  2119.1   497.9 2119.19   505.1 2121.28   515.7 2122.79
   550.1 2121.82   641.5 2122.55   662.2 2120.44   736.9 2121.17   745.9 2123.07
   780.7 2140.43   818.1 2164.24     900 2212.14  1039.3 2284.33  1100.1 2314.15
#Mann= 7 ,-1 , 0
       0      .1       0     380     .07       0   480.2    .045       0
   505.1     .07       0  594.84     .06       0  604.84     .04       0
  694.84      .1       0
#XS Ineff= 2 , 0
                          632.66         2141.39
Permanent Ineff=
       F       F
Bank Sta=480.2,505.1
XS Rating Curve= 0 ,0
Exp/Cntr(USF)=0,0
Exp/Cntr=0.5,0.3

Type RM Length L Ch R = 1 ,25087   ,51.4,49.9,50.7
XS GIS Cut Line= 4
     2101229.935      182280.066     2101199.987      182793.087
     2101240.351      182811.316     2101198.685      183377.722
#Sta/Elev= 30
       0 2217.07    29.6 2211.71   108.5 2194.45   154.5 2187.52   200.5    2179
   259.6 2161.06   305.6 2151.18   384.7 2138.53   463.4 2128.13     482 2122.34
     510 2121.56   525.6 2121.09  533.742117.908     540 2116.58  545.452117.909
   550.8 2119.87   561.8  2121.1   601.2 2120.81   611.1  2122.2   632.1 2119.32
     713 2119.13   726.2 2121.26   745.9 2122.28   762.4 2128.96   831.7 2166.28
   889.5 2200.43   949.9 2227.53  1058.5 2282.74  1104.5 2305.27  1126.1 2314.66
#Mann= 6 ,-1 , 0
       0      .1       0     510     .04       0  533.74    .045       0
  545.45     .04       0  728.18     .06       0  828.18      .1       0
#XS Ineff= 2 , 0
          519.03  2126.8  560.88         2126.71
Permanent Ineff=
       F       F
Bank Sta=533.74,545.45
XS Rating Curve= 0 ,0
Exp/Cntr=0.5,0.3

Type RM Length L Ch R = 1 ,25037   ,160.5,186,203
XS GIS Cut Line= 4
     2101191.306      182284.406     2101161.358      182819.562
     2101201.723      182837.791      2101162.66      183387.271
#Sta/Elev= 30
       0 2212.41    28.5 2206.94    67.9 2194.68   186.5  2174.4   238.8 2160.03
     270 2153.67     321 2145.89   455.7 2129.56   475.5  2125.3   485.3 2120.82
   501.7 2122.51   514.8    2122   537.4 2119.79  546.582116.148   554.1 2114.97
  561.792116.151   568.5 2120.26   574.6 2120.65   606.6 2121.55   629.6 2119.57
   698.7 2119.27   731.6 2122.14   762.4 2136.61     804 2159.62   830.3 2171.86
   938.8 2228.02   984.9  2248.7  1050.6 2280.98  1100.1 2302.12  1131.2 2313.91
#Mann= 6 ,-1 , 0
       0      .1       0     500     .04       0  546.58    .045       0
  561.79     .04       0  720.28     .06       0  820.28      .1       0
#XS Ineff= 2 , 0
           537.7 2123.73  565.43         2123.88
Permanent Ineff=
       F       F
Bank Sta=546.58,561.79
XS Rating Curve= 0 ,0
Exp/Cntr=0.5,0.3

Type RM Length L Ch R = 1 ,24851   ,335.7,337.6,342.4
XS GIS Cut Line= 4
2101018.45784039182309.1528810492101012.63069826182763.669967235
2101010.68831755182994.8132717492100999.03403329 183400.77084018
#Sta/Elev= 30
       0 2171.74      89 2164.21   108.7 2161.88   138.2 2156.17   171.1 2152.46
   207.2 2149.77   220.3 2147.22   351.7 2136.77   447.7 2127.41   469.6 2126.07
   482.8 2122.69   535.3 2117.63   541.12114.712   545.1 2112.91   548.4 2112.59
   554.9 2112.77   561.5 2114.62   587.8 2114.37   597.6 2115.34   646.3  2116.1
   689.5 2120.93   699.3 2125.89   712.4 2136.79   726.5 2145.89   756.5 2162.82
   784.6 2176.69   814.2 2188.46     870 2205.07  1004.6 2237.89  1091.8  2263.4
#Mann= 6 ,-1 , 0
       0      .1       0     380    .035       0  474.55     .04       0
   541.1    .045       0   561.5     .04       0  574.55      .1       0
#XS Ineff= 2 , 0
                          600.35         2119.61
Permanent Ineff=
       F       F
Bank Sta=541.1,561.5
XS Rating Curve= 0 ,0
Exp/Cntr(USF)=0,0
Exp/Cntr=0.3,0.1

Type RM Length L Ch R = 1 ,24514   ,301.4,296.1,294.9
XS GIS Cut Line= 3
     2100741.031      182309.294     2100690.236      182898.172
      2100641.93      183434.511
#Sta/Elev= 30
       0 2182.44    39.8 2174.39   196.9 2148.25   316.4  2134.5   339.5 2132.89
   378.8 2127.67   402.1 2126.51   421.8 2123.12   444.9 2120.82   454.7 2117.34
   469.3 2117.87   477.8 2116.78   484.4 2117.59   540.4 2111.26   584.6 2110.07
   589.8 2109.18   596.3 2110.12   616.1 2108.37  623.862110.189   672.6 2143.48
   708.3 2164.88   787.4 2207.91   807.2 2217.28     869 2249.44   919.2 2273.82
   961.1 2291.29  1008.1 2307.07  1034.5 2314.45  1087.2 2326.61  1129.6 2338.14
#Mann= 7 ,-1 , 0
       0      .1       0     180    .035       0     280      .1       0
     380     .04       0     480      .1       0   584.6    .045       0
  623.86      .1       0
#XS Ineff= 2 , 0
          545.11 2120.13
Permanent Ineff=
       F       F
Bank Sta=584.6,623.86
XS Rating Curve= 0 ,0
Exp/Cntr=0.3,0.1

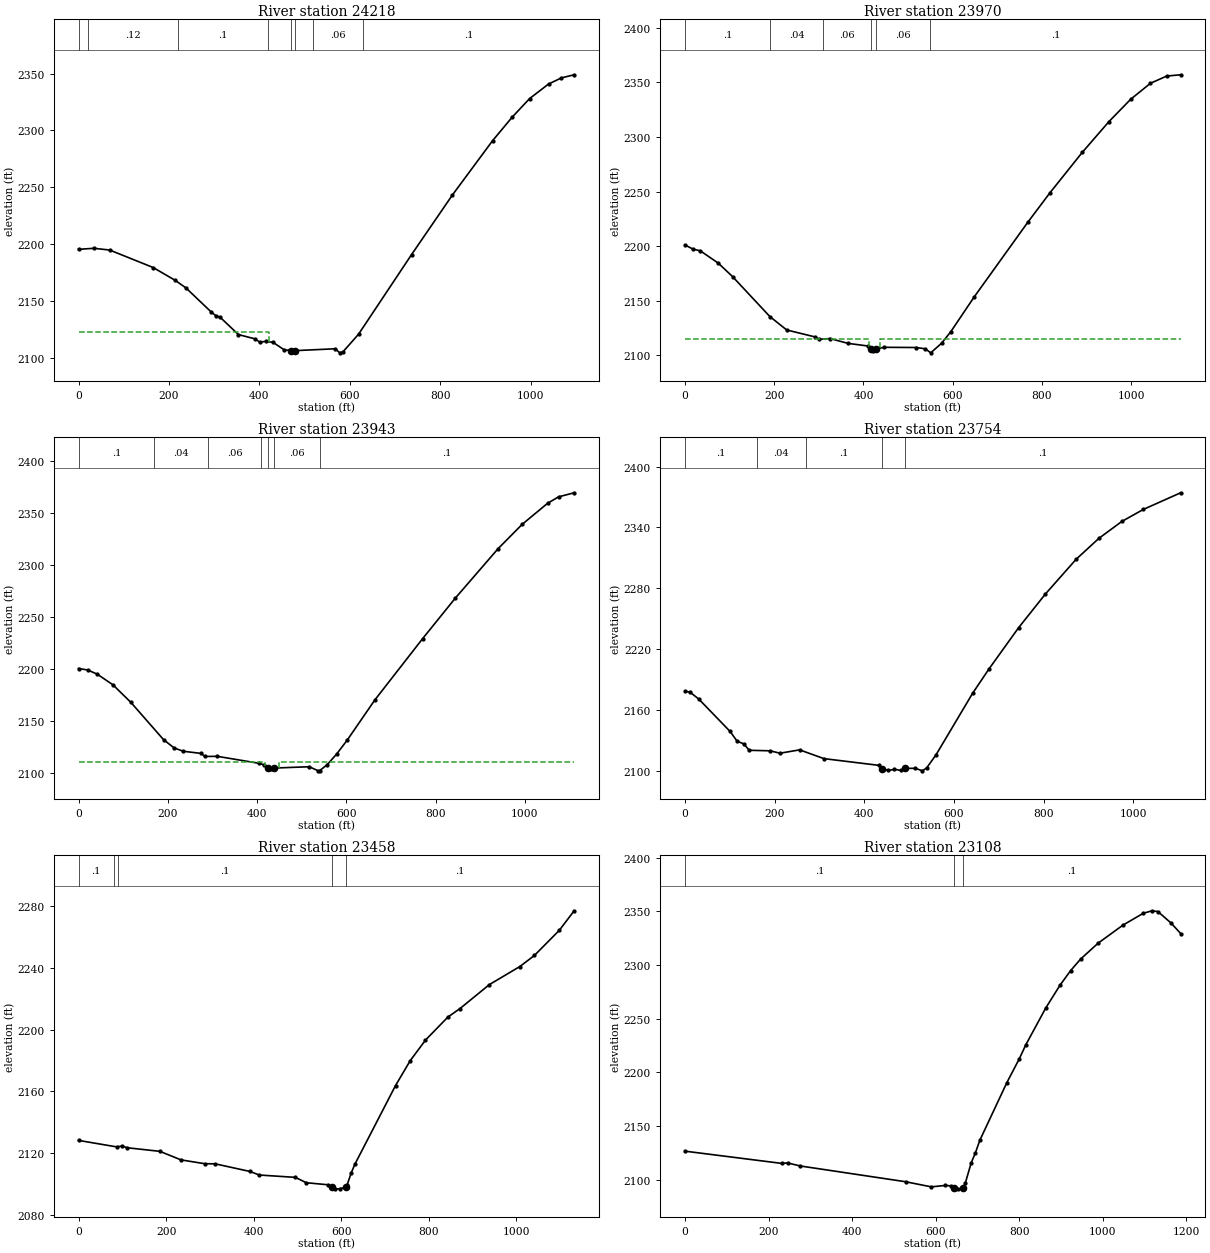
Type RM Length L Ch R = 1 ,24218   ,248,247.4,241.3
XS GIS Cut Line= 4
2100319.20078472182373.2514444852100402.72315526182783.093774337
2100470.70648012183016.1794595612100616.38503338183426.021789413
#Sta/Elev= 30
       0 2195.59    34.2 2196.49      69 2194.95     165 2179.62   212.9 2168.56
   237.3 2161.79   292.9 2140.76   303.3 2137.41   313.4 2135.83   353.6 2120.73
   390.4 2116.93   400.4 2114.16   413.8 2114.71     430 2113.93   454.8 2107.32
  469.462106.696   475.3    2106   479.8 2106.63   567.5 2108.25   577.8 2104.68
   584.8 2105.58   619.2 2121.01   736.4 2190.94   826.9 2243.37   915.5 2290.95
   959.2 2311.79   997.5 2327.99  1039.3 2340.74  1067.9 2346.17    1096 2348.88
#Mann= 8 ,-1 , 0
       0      .1       0      20     .12       0     220      .1       0
  418.27     .04       0  469.46    .045       0   479.8     .04       0
  518.27     .06       0  628.27      .1       0
#XS Ineff= 2 , 0
          420.19  2122.8
Permanent Ineff=
       F       F
Bank Sta=469.46,479.8
XS Rating Curve= 0 ,0
Exp/Cntr(USF)=0,0
Exp/Cntr=0.5,0.3

Type RM Length L Ch R = 1 ,23970   ,26.4,26.9,28.3
XS GIS Cut Line= 2
     2099957.102      182531.139     2100603.629      183434.177
#Sta/Elev= 30
       0 2201.09    18.1 2197.25    34.2 2195.73    74.5 2184.47   106.8 2172.03
   190.3 2135.47   227.9 2123.24   292.4 2116.77   300.5 2114.66   324.7 2115.41
   365.1 2110.98   409.4 2108.58  416.59 2105.83   421.6 2103.65  427.58 2105.83
     446 2107.35   518.4 2107.17   538.6 2105.96   550.7 2102.29   574.9 2111.09
   595.1 2121.34   647.9 2153.41   767.9 2221.73   817.6 2248.76   890.1  2285.8
   950.1 2314.11   998.6 2334.46  1042.9 2349.11  1079.3 2355.74  1110.6 2356.92
#Mann= 6 ,-1 , 0
       0      .1       0     190     .04       0     310     .06       0
  416.59    .045       0  427.58     .06       0     550      .1       0
#XS Ineff= 2 , 0
          412.12 2114.59   436.1         2114.65
Permanent Ineff=
       F       F
Bank Sta=416.59,427.58
XS Rating Curve= 0 ,0
Exp/Cntr=0.5,0.3

Type RM Length L Ch R = 1 ,23943   ,191.4,189.3,192.2
XS GIS Cut Line= 2
     2099934.966      182545.461     2100581.494        183448.5
#Sta/Elev= 30
       0 2200.53    20.6  2199.1    42.2 2195.02    77.1 2184.83   117.4 2167.88
   190.6 2131.97   214.3 2124.05   234.5 2120.85   274.8 2118.76   282.9 2115.84
   311.1 2115.95   404.8 2109.22   416.1 2107.73  424.822104.805   432.2 2103.39
     4392104.685   517.2 2105.94   537.1 2101.99     540 2102.08     557 2107.83
   578.3 2118.12   601.7 2131.34     664 2170.26   771.1 2229.32     844 2268.15
   940.4 2316.04   994.5 2339.48  1050.9 2359.57  1075.5 2365.81  1110.6 2369.74
#Mann= 7 ,-1 , 0
       0      .1       0     170     .04       0     290     .06       0
     410      .1       0  424.82    .045       0     439     .06       0
     540      .1       0
#XS Ineff= 2 , 0
          418.24 2110.71     449         2110.76
Permanent Ineff=
       F       F
Bank Sta=424.82,439
XS Rating Curve= 0 ,0
Exp/Cntr=0.5,0.3

Type RM Length L Ch R = 1 ,23754   ,294.9,296.2,283.8
XS GIS Cut Line= 4
2099802.52751581182651.0118860442100014.24701322182987.043748908
2100095.82700305183072.5085001572100474.59124154183525.083205633
#Sta/Elev= 30
       0 2178.67    11.4 2177.63    30.8 2170.88   100.6 2138.97   116.1 2129.47
   131.6 2126.58   143.2  2120.4   189.8 2119.89     212 2117.53   255.7 2120.82
     310 2112.18   433.6  2105.5   440.3  2102.4   453.3  2100.5   467.2 2101.66
   481.1 2100.61   490.4 2102.57   513.6 2102.65   529.6 2100.15   539.2 2103.11
   560.2 2116.12   641.4 2176.48   677.8 2200.41     744 2241.15   803.9 2274.43
   872.4 2308.63   923.2 2329.28   974.3 2345.91  1022.1 2357.73  1105.5 2374.18
#Mann= 5 ,-1 , 0
       0      .1       0     160     .04       0     270      .1       0
   440.3    .045       0   490.4      .1       0
Bank Sta=440.3,490.4
XS Rating Curve= 0 ,0
Exp/Cntr(USF)=0,0
Exp/Cntr=0.3,0.1

Type RM Length L Ch R = 1 ,23458   ,338.8,350,359.2
XS GIS Cut Line= 3
     2099546.328      182808.171     2099906.273      183280.112
     2100311.175      183634.749
#Sta/Elev= 30
       0 2128.13    86.8 2123.94    99.2 2124.46   111.5 2123.36   185.8 2121.03
   234.1 2115.49   288.2 2113.02   312.1 2112.93   391.7 2107.98   412.7 2105.68
   495.3 2104.16     520 2100.69   569.6 2099.36  579.682097.721   585.8 2096.73
     596 2096.72  609.92 2097.72   613.5 2099.34   622.2 2106.68   630.9 2112.59
   723.9  2163.7   757.4 2179.82   792.3 2193.18   843.4  2208.1   870.8 2213.56
   938.1 2229.16  1007.8 2240.88  1040.9 2248.04  1097.6 2264.28  1131.8 2277.04
#Mann= 5 ,-1 , 0
       0      .1       0      80     .04       0      90      .1       0
  579.68    .045       0  609.92      .1       0
Bank Sta=579.68,609.92
XS Rating Curve= 0 ,0
Exp/Cntr=0.3,0.1

Type RM Length L Ch R = 1 ,23108   ,389.2,394.4,392.9
XS GIS Cut Line= 3
     2099467.289      182860.355     2099644.146      183497.263
     2099824.215      183991.166
#Sta/Elev= 30
       0 2126.67     232 2115.25   245.6 2115.69   276.2 2112.86   528.2 2098.19
   589.5 2093.42   623.5 2094.72   637.2 2094.33  643.282092.801   654.2 2091.57
   664.5 2091.62  666.632092.797   671.5 2097.37   685.4 2115.91   695.5 2125.24
   705.7 2136.63   770.8 2190.63   800.7 2212.94   815.7 2225.51   863.5 2259.86
   897.6  2281.1   923.2 2294.83   947.4 2305.69   989.3 2320.49  1048.6 2337.25
  1097.5 2348.33  1118.5 2350.61  1132.4 2349.85  1163.9 2339.15  1186.7 2329.43
#Mann= 3 ,-1 , 0
       0      .1       0  643.28    .045       0  666.63      .1       0
Bank Sta=643.28,666.63
XS Rating Curve= 0 ,0
Exp/Cntr=0.3,0.1

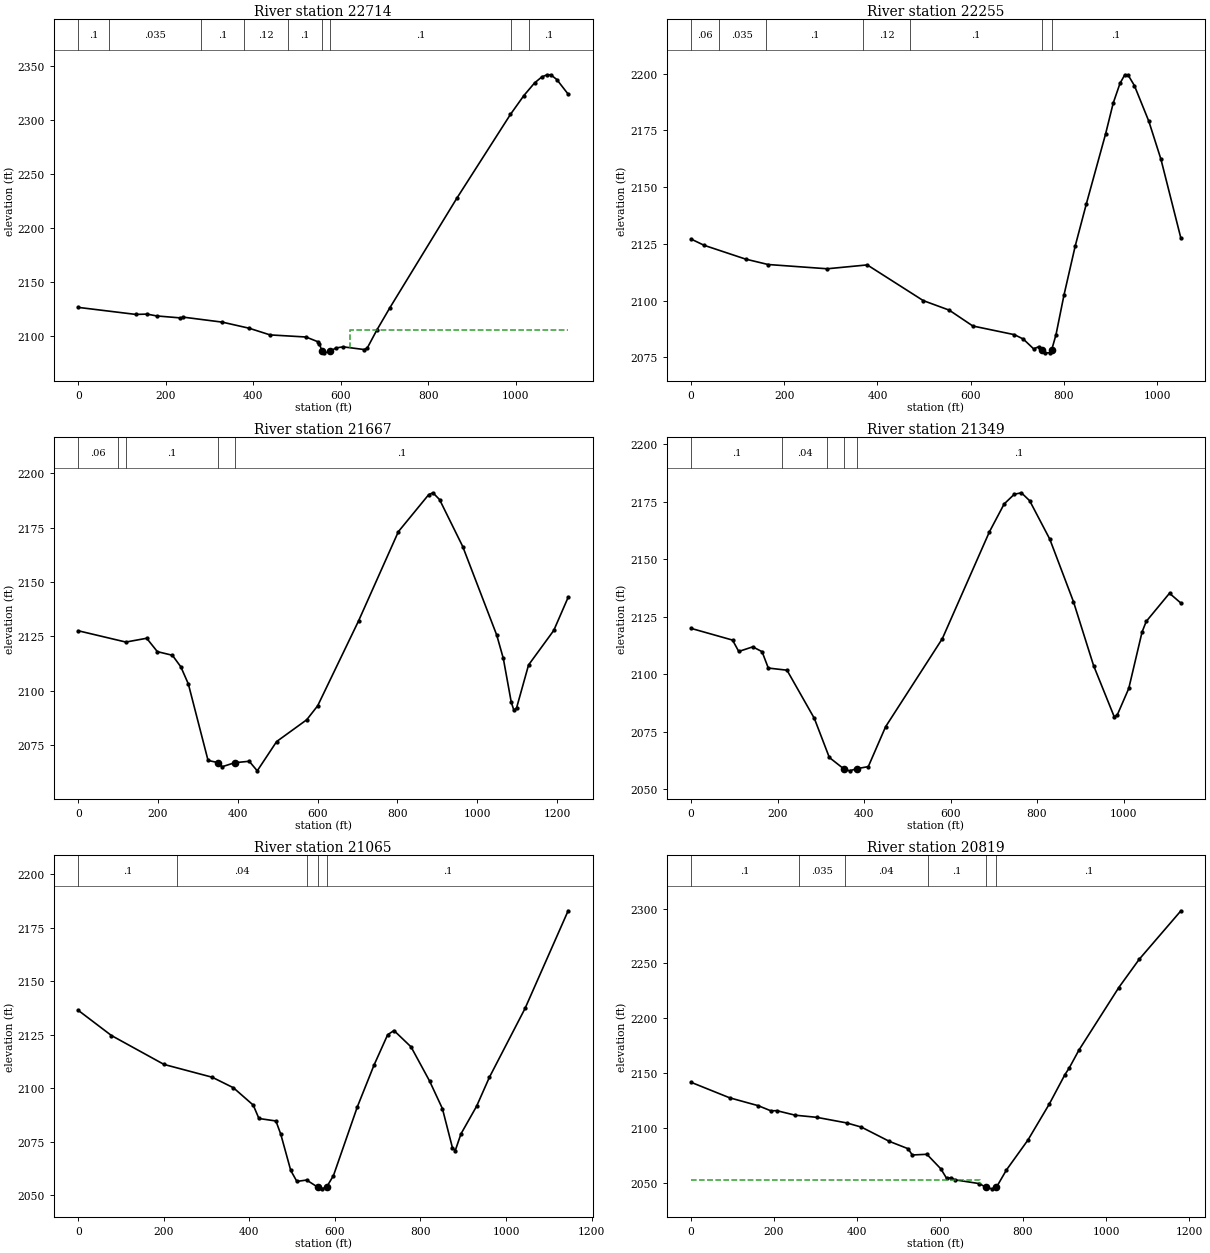
Type RM Length L Ch R = 1 ,22714   ,445.1,458.7,467.8
XS GIS Cut Line= 2
     2099110.877      182911.686     2099421.207      183988.075
#Sta/Elev= 30
       0  2126.8   131.4 2120.31   157.7 2120.58   179.2 2118.91   233.8 2117.08
   240.7 2117.76   329.4 2113.18   390.9 2107.55   438.6  2101.4   520.8 2099.45
     548 2095.09   551.4  2093.2   557.62086.196   561.6 2084.84  576.442086.198
   588.9 2089.35     606 2090.36   653.8 2087.89   660.6 2089.06   682.4 2105.58
   712.3 2126.26   865.5 2227.42   988.4 2304.99    1019 2322.33  1043.4 2333.95
  1060.1 2339.55    1072  2341.5  1080.6 2341.48  1094.3  2337.1  1120.2 2323.65
#Mann= 9 ,-1 , 0
       0      .1       0      70    .035       0     280      .1       0
     380     .12       0     480      .1       0   557.6    .045       0
  576.44      .1       0     990     .12       0    1030      .1       0
#XS Ineff= 2 , 0
                          622.35         2105.63
Permanent Ineff=
       F       F
Bank Sta=557.6,576.44
XS Rating Curve= 0 ,0
Exp/Cntr=0.3,0.1

Type RM Length L Ch R = 1 ,22255   ,562,588.2,555
XS GIS Cut Line= 2
     2099093.516      182922.537     2098785.357      183927.311
#Sta/Elev= 30
       0 2127.11    28.1 2124.35   117.3 2118.26   165.3 2115.89   292.3 2114.01
   378.1 2115.71   498.2 2099.99   553.8  2095.8   604.6  2088.8   693.8 2084.98
   712.8 2083.06     735 2078.74   746.4 2079.71  752.722078.145     759 2076.98
   769.2 2077.01  773.552078.145     783 2084.96   800.2 2102.49   824.3 2124.09
   848.2 2142.67   889.4  2173.4   905.7 2186.95   920.3 2195.67   930.6 2199.46
   937.4 2199.43   951.2  2194.7   982.1 2179.01  1008.1 2162.28    1051 2127.43
#Mann= 7 ,-1 , 0
       0     .06       0      60    .035       0     160      .1       0
     370     .12       0     470      .1       0  752.72    .045       0
  773.55      .1       0
Bank Sta=752.72,773.55
XS Rating Curve= 0 ,0
Exp/Cntr=0.3,0.1

Type RM Length L Ch R = 1 ,21667   ,338.8,317.4,199.9
XS GIS Cut Line= 3
     2099073.985      182911.686     2098624.766      183228.527
     2098509.749      183896.929
#Sta/Elev= 30
       0 2127.54   119.4 2122.34   171.6 2124.09   198.3 2117.94     236 2116.26
   257.2 2110.94     276 2103.06   325.4 2067.87   351.3 2066.82   360.3 2064.95
   392.4 2066.83   428.6 2067.48   448.7 2063.08   497.3 2076.56   572.7 2086.58
   600.1    2093   702.5 2132.03   802.4 2173.15   878.4 2190.18     889 2191.04
   905.6 2187.92   963.7 2166.31  1048.9 2125.56  1065.4 2114.84  1085.4 2094.62
    1092 2090.92  1098.7 2092.06  1128.7  2111.8  1191.9  2127.7  1227.9 2142.91
#Mann= 5 ,-1 , 0
       0     .06       0     100     .04       0     120      .1       0
   351.3    .045       0   392.4      .1       0
Bank Sta=351.3,392.4
XS Rating Curve= 0 ,0
Exp/Cntr=0.3,0.1

Type RM Length L Ch R = 1 ,21349   ,290.2,283.8,276.6
XS GIS Cut Line= 4
2098668.17718105182792.8056778882098551.63433844183053.084693055
2098584.65481051183231.7837183932098435.09149583183880.538875599
#Sta/Elev= 30
       0 2119.94      96 2114.84   110.4  2109.9   142.8  2111.9   164.3  2109.8
   178.7 2102.68   221.9 2101.75   285.2 2080.77   319.8  2063.8  352.84 2058.91
   366.5 2057.99     383 2058.91   409.9 2059.83   449.9 2077.16   581.1 2115.47
   689.9  2161.9     724 2174.03   747.4 2178.24   763.8 2178.89     783 2175.43
   829.5 2158.73   884.2 2131.57   930.7 2103.79   978.4 2081.54   985.1 2082.09
  1012.1 2093.81  1042.9 2118.38  1052.5 2122.96  1106.3  2135.2  1132.7 2130.92
#Mann= 5 ,-1 , 0
       0      .1       0     210     .04       0  315.18      .1       0
  352.84    .045       0     383      .1       0
Bank Sta=352.84,383
XS Rating Curve= 0 ,0
Exp/Cntr(USF)=0,0
Exp/Cntr=0.3,0.1

Type RM Length L Ch R = 1 ,21065   ,227.1,246.7,259.1
XS GIS Cut Line= 4
 2098372.9353131182753.9580636842098308.83674967183224.014195552
2098405.95578517183453.215119356 2098334.0876989183868.884591338
#Sta/Elev= 30
       0  2136.5    77.6 2124.73   200.5 2111.21   313.1 2105.23   362.8  2100.3
   409.1  2092.2   422.4 2085.94   462.1 2084.78   473.5 2078.58   496.8 2061.64
   511.1 2056.53   533.9 2057.17  559.962053.831   568.9 2053.06  580.442053.832
   596.6 2059.24   652.6 2091.46   691.5 2110.92   723.3 2125.08   738.1 2127.05
     778 2119.41   821.3 2103.46   851.3 2090.55   874.6 2072.38   881.2 2070.85
   894.6 2078.72   931.2 2091.66   961.1 2105.19  1044.4 2137.36  1145.2 2183.03
#Mann= 5 ,-1 , 0
       0      .1       0     230     .04       0  534.41      .1       0
  559.96    .045       0  580.44      .1       0
Bank Sta=559.96,580.44
XS Rating Curve= 0 ,0
Exp/Cntr(USF)=0,0
Exp/Cntr=0.3,0.1

Type RM Length L Ch R = 1 ,20819   ,258.3,268.3,268.9
XS GIS Cut Line= 2
     2098353.499      182729.395     2097999.766      183855.697
#Sta/Elev= 30
       0 2141.52      93 2127.36   161.8 2120.17   192.7 2115.44   206.5 2115.62
   251.2 2111.46   302.8 2109.53     375 2104.43   410.6 2100.59   478.2 2087.53
   522.9  2080.9   533.2 2075.15   568.4 2075.78     602 2062.49   615.7 2053.96
     626 2054.41   636.3 2052.45   694.8 2049.01  710.432045.667   725.4 2044.24
  735.892045.667   760.1 2061.48   811.9  2088.8   863.3 2121.64   901.1 2148.56
   911.2 2154.46   934.7 2170.87  1030.8 2228.01  1079.9 2253.76  1180.5 2298.09
#Mann= 6 ,-1 , 0
       0      .1       0     260    .035       0     370     .04       0
     570      .1       0  710.43    .045       0  735.89      .1       0
#XS Ineff= 2 , 0
          695.25 2052.63
Permanent Ineff=
       F       F
Bank Sta=710.43,735.89
XS Rating Curve= 0 ,0
Exp/Cntr=0.3,0.1

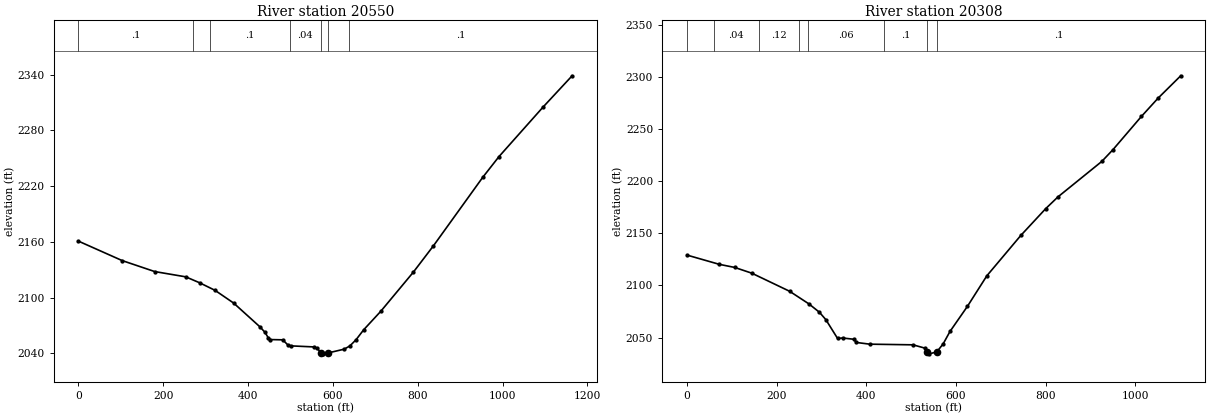
Type RM Length L Ch R = 1 ,20550   ,240.4,242.4,241.5
XS GIS Cut Line= 4
2098232.02315664182699.2188088552098039.59098752183092.964631834
2097859.00079803183463.0264955362097731.69951692183750.194501769
#Sta/Elev= 30
       0 2160.92   103.1 2139.99   179.8 2128.17   252.9  2122.5   285.7 2116.11
   322.3 2107.91   366.1 2094.22   428.1 2068.63     440 2062.72   447.3 2057.11
   452.2 2054.98   481.7  2054.7   493.8 2049.22   501.1 2048.19   555.3 2047.06
   563.2 2045.55  571.612040.662   577.3 2039.62   589.32040.661   626.4 2044.62
   639.9 2048.08   654.5 2054.75   672.7 2065.57   712.9  2085.4   789.6 2127.48
     837 2155.84   953.2 2229.51   991.5 2251.83  1095.8 2305.32  1164.1 2338.86
#Mann= 7 ,-1 , 0
       0      .1       0     270     .12       0     310      .1       0
  498.25     .04       0  571.61    .045       0   589.3     .04       0
  638.25      .1       0
Bank Sta=571.61,589.3
XS Rating Curve= 0 ,0
Exp/Cntr(USF)=0,0
Exp/Cntr=0.3,0.1

Type RM Length L Ch R = 1 ,20308   ,356.9,352.7,350.2
XS GIS Cut Line= 3
     2098043.254      182647.938     2097763.197      183115.903
     2097532.524      183621.706
#Sta/Elev= 30
       0 2129.06    72.2 2120.19   106.3 2117.23   144.3 2111.76   228.9 2094.37
   272.1 2082.23   295.3 2074.28   309.7 2067.18   335.9 2049.12   347.5 2049.57
   371.8 2048.38     378 2045.29   407.7 2043.66   504.2 2043.03     531 2039.81
  536.112036.243   540.4 2034.39  557.172036.241   571.5 2044.02   586.6 2055.83
   625.6 2079.98   668.8 2109.19   744.5 2147.85   800.1 2173.58   827.5 2184.88
   925.4 2218.92   950.4 2230.27  1013.6    2262    1051 2279.62  1101.3 2300.98
#Mann= 8 ,-1 , 0
       0     .12       0      60     .04       0     160     .12       0
     250     .04       0     270     .06       0     440      .1       0
  536.11    .045       0  557.17      .1       0
Bank Sta=536.11,557.17
XS Rating Curve= 0 ,0
Exp/Cntr=0.3,0.1