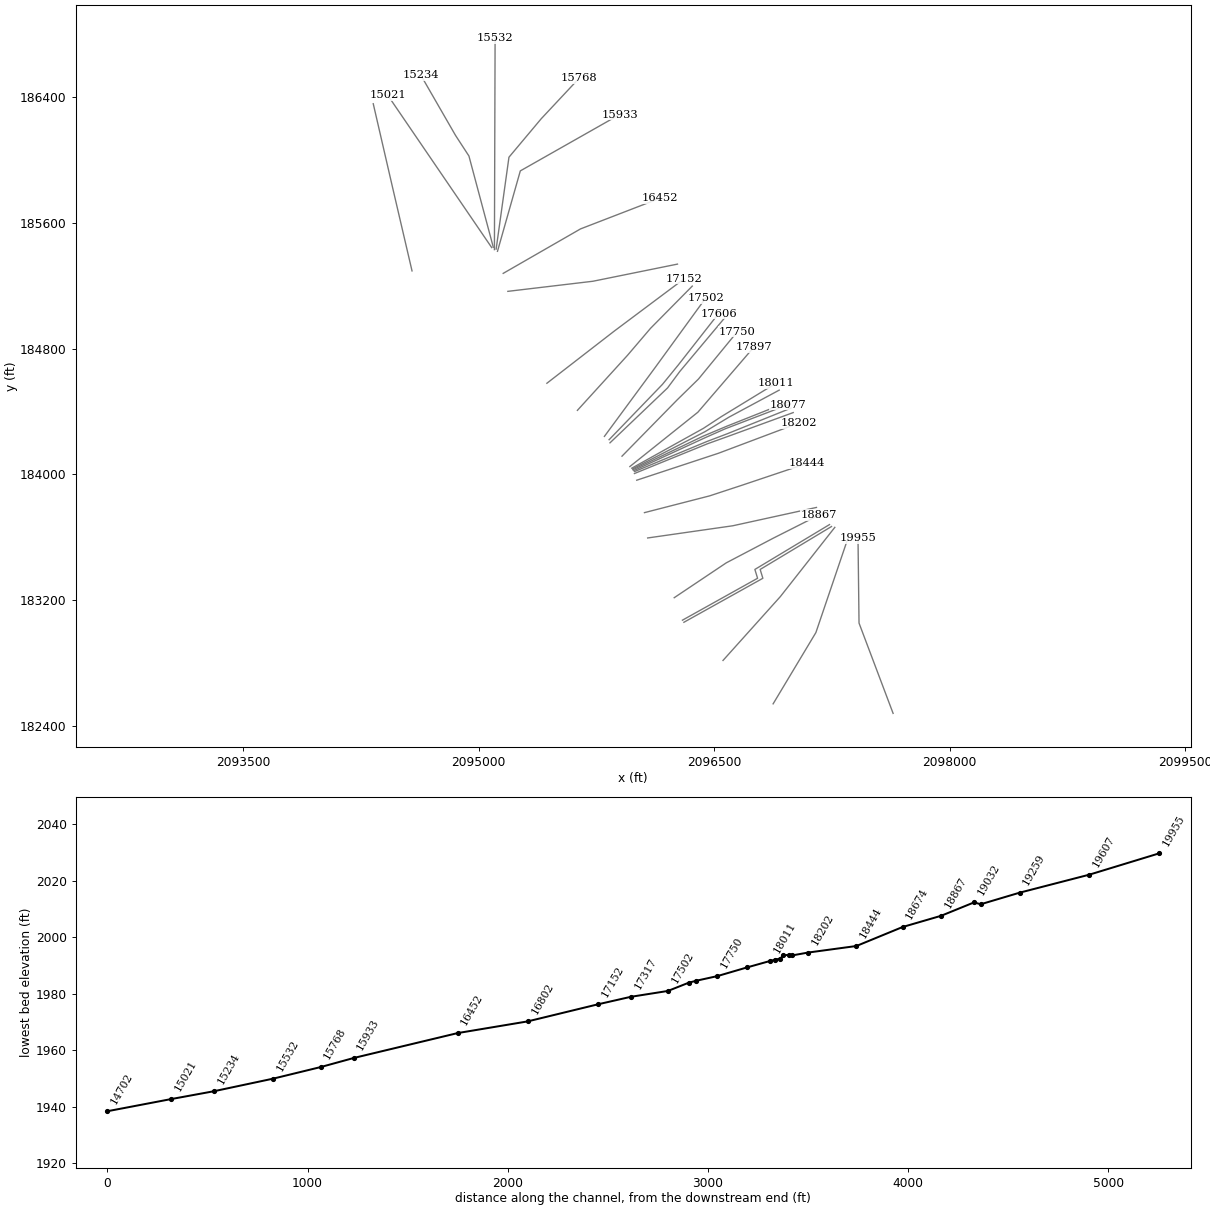
HEC-RAS study DRPLKCR.prj: DRPLKCR

--- DRPLKCR.g01 (geometry) --- (continued)

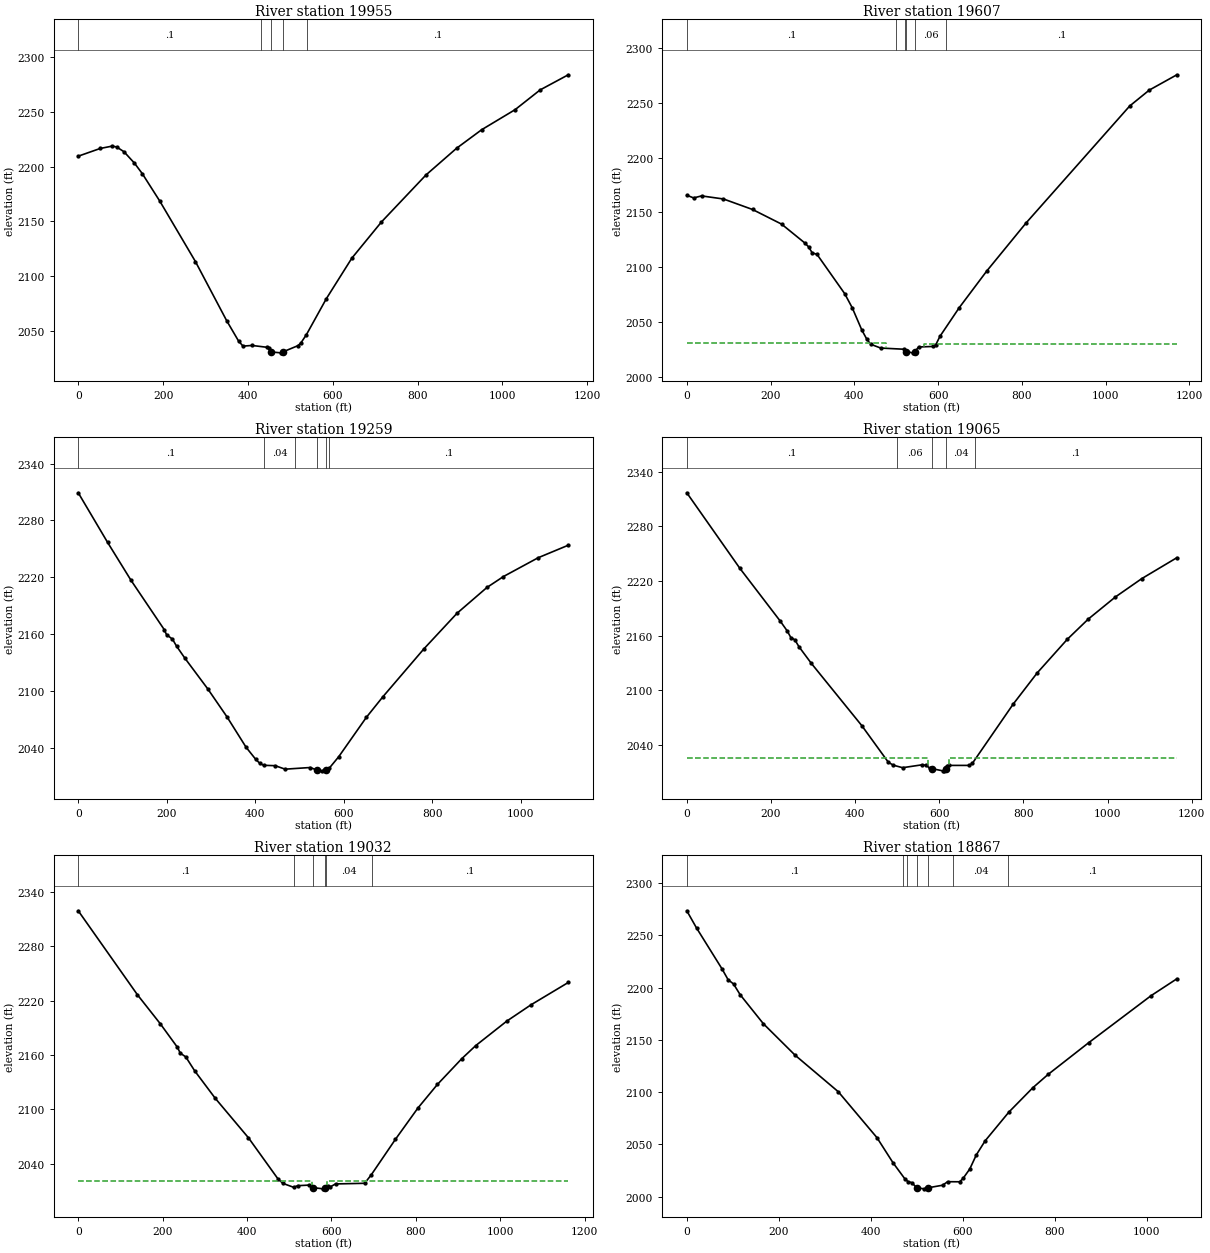
Type RM Length L Ch R = 1 ,19955   ,366.6,348.3,331.2
XS GIS Cut Line= 3
     2097639.523      182477.659     2097422.509      183052.745
     2097415.999       183593.11
#Sta/Elev= 30
       0 2209.47    51.8 2216.53    79.7 2218.66    90.4 2217.94   107.9 2213.53
   132.5 2203.12     151 2193.51   192.1 2168.48   276.2 2113.15   349.9 2059.03
   377.9 2040.46   388.4 2035.78   409.5 2036.41   444.6 2034.74   448.8 2034.02
   454.42030.502   476.9 2029.65  482.35  2030.5   518.2 2036.26   525.3 2038.97
     538 2046.38   584.8 2079.16   644.9 2116.22   714.7 2149.32   819.7 2192.31
   891.9 2216.75   950.9 2233.66  1029.7    2252  1088.7 2270.05  1155.1 2283.91
#Mann= 5 ,-1 , 0
       0      .1       0     430     .04       0   454.4    .045       0
  482.35     .04       0     540      .1       0
Bank Sta=454.4,482.35
XS Rating Curve= 0 ,0
Exp/Cntr=0.3,0.1

Type RM Length L Ch R = 1 ,19607   ,351.8,348.4,339.2
XS GIS Cut Line= 3
     2096875.429      182538.409     2097147.731      182992.248
     2097353.927      183599.017
#Sta/Elev= 30
       0  2165.7    16.3 2163.24    35.4 2165.07    87.6 2162.27   156.9 2152.71
   226.3 2139.38   281.3 2122.35   290.9 2118.66   299.4 2113.21   310.9 2111.83
   376.9 2076.11   395.1 2063.11     418 2042.83   429.6 2034.69   439.1 2029.95
     463 2026.48   517.5 2025.43  524.352023.242   539.4 2022.12  544.792023.242
   553.3 2027.45   586.9 2027.93   594.7 2029.65   604.4 2037.12   650.3 2063.15
   716.2 2096.64   809.7 2140.25  1057.6    2247  1104.2 2261.43  1170.1 2275.41
#Mann= 6 ,-1 , 0
       0      .1       0     500     .04       0     520     .06       0
  524.35    .045       0  544.79     .06       0  619.26      .1       0
#XS Ineff= 2 , 0
          476.09 2031.38  567.35         2030.41
Permanent Ineff=
       F       F
Bank Sta=524.35,544.79
XS Rating Curve= 0 ,0
Exp/Cntr=0.3,0.1

Type RM Length L Ch R = 1 ,19259   ,167.4,194,211.3
XS GIS Cut Line= 3
     2096556.267      182814.702      2096921.32      183221.246
     2097268.285      183662.383
#Sta/Elev= 30
       0 2309.24    66.3 2256.91   119.2 2216.92   194.2 2164.92   199.6 2159.47
     213 2154.73   222.3  2147.3   240.9 2134.74   292.9 2102.16   336.2 2072.73
   379.4 2040.61   401.4 2027.74   410.5 2023.61   419.1 2021.58   445.2 2021.17
   467.6  2017.5   524.3 2019.25  539.682016.515   551.1 2015.74   559.92016.514
   567.8  2018.8   588.7 2030.62   651.3 2072.25   688.8 2094.06   781.2 2144.45
   856.2 2182.09   923.7 2209.28   961.1 2220.84  1039.5 2240.67  1107.6 2253.89
#Mann= 6 ,-1 , 0
       0      .1       0     420     .04       0     490     .06       0
  539.68    .045       0   559.9     .06       0  566.39      .1       0
Bank Sta=539.68,559.9
XS Rating Curve= 0 ,0
Exp/Cntr=0.5,0.3

Type RM Length L Ch R = 1 ,19065   ,31.1,33.1,34.4
XS GIS Cut Line= 4
     2096307.192      183057.843     2096810.056      183338.052
     2096792.869      183394.302     2097247.209      183667.705
#Sta/Elev= 30
       0    2317   126.1 2234.05     222 2176.15   238.8 2165.22   247.2 2158.07
   256.9 2155.48   266.5 2148.02   296.1  2129.6   416.1 2061.19   479.1 2021.02
   490.8 2017.87   512.9  2015.1   558.4 2018.22   569.3 2017.85   577.5 2014.29
  582.822014.048   608.3 2011.65   611.8 2011.72  616.282014.054   618.6  2016.7
   622.1 2017.62     671 2017.61   678.7 2019.86   775.3 2084.64   832.7 2119.14
   904.4 2156.13   954.3 2178.35  1018.7  2202.6  1081.3 2222.72  1164.7  2245.7
#Mann= 5 ,-1 , 0
       0      .1       0     500     .06       0  582.82    .045       0
  616.28     .04       0  684.48      .1       0
#XS Ineff= 2 , 0
          573.08  2025.7  623.35         2025.46
Permanent Ineff=
       F       F
Bank Sta=582.82,616.28
XS Rating Curve= 0 ,0
Exp/Cntr=0.5,0.3

Type RM Length L Ch R = 1 ,19032   ,196.8,164.9,136.2
XS GIS Cut Line= 4
     2096298.063      183071.278     2096776.419      183338.052
     2096759.232      183394.302     2097234.478      183680.002
#Sta/Elev= 30
       0  2319.1   140.3  2226.4   194.3  2194.5   234.7 2168.66   241.7 2162.11
   254.9  2157.8   276.1 2142.36   324.4 2112.32   403.3 2068.61   473.1 2023.35
   485.2 2018.27   510.8 2013.92   519.7 2015.79   547.7 2016.45   555.72013.668
   580.4 2012.31  584.962013.669   590.7 2015.32   597.5 2014.59   609.5 2017.72
   678.5 2018.43   693.8 2027.49   751.2 2066.76   804.8 2101.51   850.9 2127.47
   908.2  2155.7   941.6  2170.3  1015.3 2197.37  1072.7 2215.36    1161    2240
#Mann= 6 ,-1 , 0
       0      .1       0     510     .06       0   555.7    .045       0
  584.96     .06       0  587.72     .04       0  696.53      .1       0
#XS Ineff= 2 , 0
          552.86 2020.63  588.45         2020.57
Permanent Ineff=
       F       F
Bank Sta=555.7,584.96
XS Rating Curve= 0 ,0
Exp/Cntr=0.5,0.3

Type RM Length L Ch R = 1 ,18867   ,200.8,192.3,186.7
XS GIS Cut Line= 4
2096245.53107229183214.3449231282096577.10650217183436.382041349
2096876.11648804183593.2882715592097169.20548409 183741.31301704
#Sta/Elev= 30
       0 2273.49    21.2 2257.02    76.5 2217.97    89.8 2207.56   101.6  2203.5
   115.9 2193.27   166.5 2165.45   235.5 2135.33   329.2 2100.46   413.3 2056.53
   448.3 2032.44     474  2017.1   480.6 2014.52   489.1 2013.45  499.632008.576
   515.9 2007.56   524.42008.575   555.8    2011   566.9 2014.38   593.1 2014.31
   600.4 2017.49     615 2026.52   629.5  2040.2   648.4 2053.45     700 2080.94
     752 2104.22   785.1 2116.92   873.2 2147.22  1009.3 2192.36  1065.1 2208.42
#Mann= 7 ,-1 , 0
       0      .1       0  469.05     .04       0  479.05      .1       0
  499.63    .045       0   524.4      .1       0  579.05     .04       0
  699.05      .1       0
Bank Sta=499.63,524.4
XS Rating Curve= 0 ,0
Exp/Cntr(USF)=0,0
Exp/Cntr=0.3,0.1

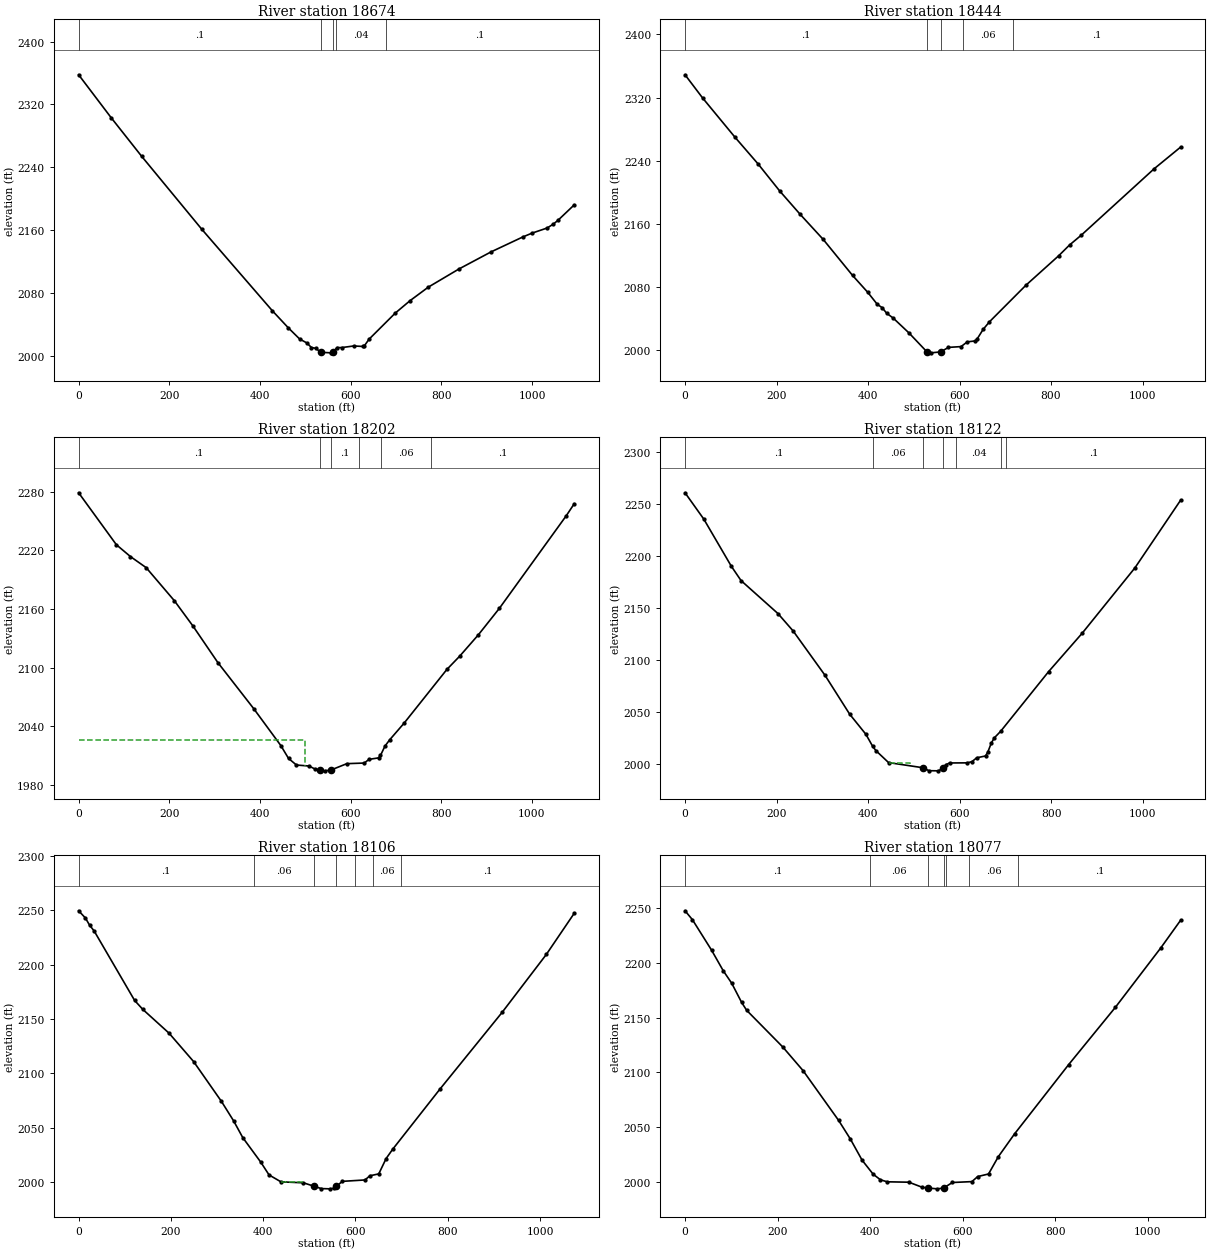
Type RM Length L Ch R = 1 ,18674   ,225.9,230.6,233
XS GIS Cut Line= 3
     2096076.461      183594.752     2096618.241      183672.383
      2097151.42      183789.178
#Sta/Elev= 30
       0 2357.63      72 2302.78   138.9  2253.9   271.4  2161.1   427.2 2057.22
   462.7 2035.27   487.5 2021.19   503.4 2016.19   513.4 2010.36   523.3 2009.35
   533.6 2004.29   556.6 2003.59  560.692004.291     570 2010.32   580.1 2010.28
     607 2012.35   627.1  2011.7   630.5 2012.79   640.6 2020.98   698.4 2054.21
   731.2 2070.11   771.5 2087.34   838.7 2110.32   909.5 2132.08   979.8 2151.16
   999.9 2155.99  1033.5 2162.56  1046.8 2167.45    1057  2172.2  1093.1 2191.98
#Mann= 5 ,-1 , 0
       0      .1       0   533.6    .045       0  560.69      .1       0
  567.31     .04       0  677.31      .1       0
Bank Sta=533.6,560.69
XS Rating Curve= 0 ,0
Exp/Cntr=0.3,0.1

Type RM Length L Ch R = 1 ,18444   ,241.4,241.6,241.8
XS GIS Cut Line= 4
2096056.05939807183756.1154915882096470.52868542183862.693308334
2096677.76332909183930.7846912552097092.23261644184069.927952007
#Sta/Elev= 30
       0 2348.98    38.3 2319.68   108.8 2270.16   159.6 2236.11     207 2201.77
   251.6 2172.29   301.9 2140.57   366.2 2094.87   399.4 2073.49   420.4 2058.16
   430.7 2054.15     441 2046.86     455  2040.9   489.4 2022.12  528.851998.052
   537.7 1996.87  558.661998.052   575.7 2003.76   603.3 2004.78   617.1 2010.81
   634.6 2011.95   637.9 2013.89   651.7 2026.64   665.5 2036.23   745.1 2082.48
   816.8 2119.84   840.5 2133.44   866.3 2145.96  1025.1 2229.81  1083.3 2257.42
#Mann= 5 ,-1 , 0
       0      .1       0  528.85    .045       0  558.66      .1       0
  607.95     .06       0  716.09      .1       0
Bank Sta=528.85,558.66
XS Rating Curve= 0 ,0
Exp/Cntr(USF)=0,0
Exp/Cntr=0.3,0.1

Type RM Length L Ch R = 1 ,18202   ,80.7,80.6,80.8
XS GIS Cut Line= 3
     2096006.834      183962.629     2096527.388      184134.278
     2097037.796      184326.382
#Sta/Elev= 30
       0 2278.92    83.3 2225.78   114.4 2213.66     149 2202.36   211.2 2168.55
   252.4 2142.54   307.3 2105.19   386.4 2058.09   446.1 2020.42   463.1 2007.26
   480.6 2000.49   508.2 1999.49   522.1 1996.27  531.861995.416   542.8 1994.55
  556.781995.415   591.8 2001.89   630.3 2002.52   640.6 2006.28   661.9 2007.81
     666 2010.28   675.9 2019.86   686.4 2026.33     718 2043.26   812.6  2098.3
   840.7 2111.78   881.9 2133.62   928.4 2160.77  1076.1 2255.55  1093.5 2267.71
#Mann= 6 ,-1 , 0
       0      .1       0  531.86    .045       0  556.78      .1       0
  618.12     .04       0  668.12     .06       0  778.12      .1       0
#XS Ineff= 2 , 0
          498.57 2025.72
Permanent Ineff=
       F       F
Bank Sta=531.86,556.78
XS Rating Curve= 0 ,0
Exp/Cntr=0.5,0.3

Type RM Length L Ch R = 1 ,18122   ,15.4,15.5,16.1
XS GIS Cut Line= 4
2095992.25041816184005.2429211532096458.11295008184194.986323209
2096588.38453955184241.7141759552097003.27123211184393.225698492
#Sta/Elev= 30
       0 2260.64      41 2235.35   101.2 2190.04   122.4 2176.29   203.2 2144.55
   236.3 2127.85   305.9 2085.31   359.8 2047.95   395.2 2028.65   410.2 2016.97
   417.2 2012.91   444.8 2001.45   520.6 1996.46   532.9 1993.66   553.8 1993.52
   564.5 1996.31   569.5 1999.31   578.2 2001.08   616.5 2001.19     627 2002.32
   637.5 2006.07   656.7 2007.79   661.8 2011.63   669.4 2020.27   675.9  2025.2
   689.7 2031.47   794.6 2088.85     868 2125.75   983.2 2188.51  1083.1 2253.54
#Mann= 7 ,-1 , 0
       0      .1       0     410     .06       0   520.6    .045       0
   564.5     .06       0  593.02     .04       0  691.42     .06       0
  701.42      .1       0
#XS Ineff= 3 ,-1
  445.39   491.5 2000.96  497.62  518.111996.481  566.49   585.71996.065
Permanent Ineff=
       F       F       F
Bank Sta=520.6,564.5
XS Rating Curve= 0 ,0
Exp/Cntr(USF)=0,0
Exp/Cntr=0.5,0.3

Type RM Length L Ch R = 1 ,18106   ,27.6,28.9,30.7
XS GIS Cut Line= 4
 2095993.6664137184017.9868809922096453.86496347184209.146278587
2096584.13655294184258.7061224072096989.11127673184421.545609247
#Sta/Elev= 30
       0 2249.57    14.7 2242.92    23.6 2236.42    33.7 2230.94   121.3 2167.11
   139.2  2158.8   195.9    2137   249.2 2110.85   309.6 2074.16     336 2056.24
   355.7 2040.92   394.8  2018.3   412.7 2006.56   438.6 2000.19   487.2 1999.32
   510.7  1996.1   525.9 1993.99   544.6 1993.76     554  1994.3   558.9 1996.17
   571.6 2000.65   620.7 2001.93   631.2 2005.77   650.5 2007.51   666.5 2021.65
   680.7 2030.18   783.2 2085.55   917.8 2156.05  1013.7 2209.39  1074.2 2247.27
#Mann= 7 ,-1 , 0
       0      .1       0     380     .06       0   510.7    .045       0
   558.9     .06       0  598.32     .04       0   637.7     .06       0
   697.7      .1       0
#XS Ineff= 3 ,-1
  437.57  486.39  2000.2  492.22  509.191996.103  559.75  593.691996.192
Permanent Ineff=
       F       F       F
Bank Sta=510.7,558.9
XS Rating Curve= 0 ,0
Exp/Cntr(USF)=0,0
Exp/Cntr=0.5,0.3

Type RM Length L Ch R = 1 ,18077   ,13.9,13.2,12.7
XS GIS Cut Line= 4
2095988.00243155184023.6508631432096445.36899024184234.634198266
2096569.97659756184289.8580242382096972.11933028184444.201537851
#Sta/Elev= 30
       0 2247.86    15.9 2239.74    57.3 2211.85    82.6 2192.95   100.7 2181.69
   122.3 2164.01   133.2 2156.79   211.2 2123.25     255 2101.64   331.9 2056.05
   357.1 2039.14   382.5 2019.75   406.5 2006.87   422.2  2001.8   436.7 1999.96
   483.6 1999.59   512.9 1994.86  525.861994.225   544.8 1993.52  558.451994.225
   577.5 1999.32   619.8 2000.13   632.2 2004.74   655.7 2007.12   676.8  2022.9
   711.9 2043.79   828.5 2107.01   929.8  2159.6  1028.2 2214.13  1070.7 2239.21
#Mann= 7 ,-1 , 0
       0      .1       0     400     .06       0  525.86    .045       0
  558.45     .06       0  563.68     .04       0  613.68     .06       0
  719.98      .1       0
#XS Ineff= 2 , 0
          511.97 1994.34  571.02         1994.48
Permanent Ineff=
       F       F
Bank Sta=525.86,558.45
XS Rating Curve= 0 ,0
Exp/Cntr(USF)=0,0
Exp/Cntr=0.5,0.3

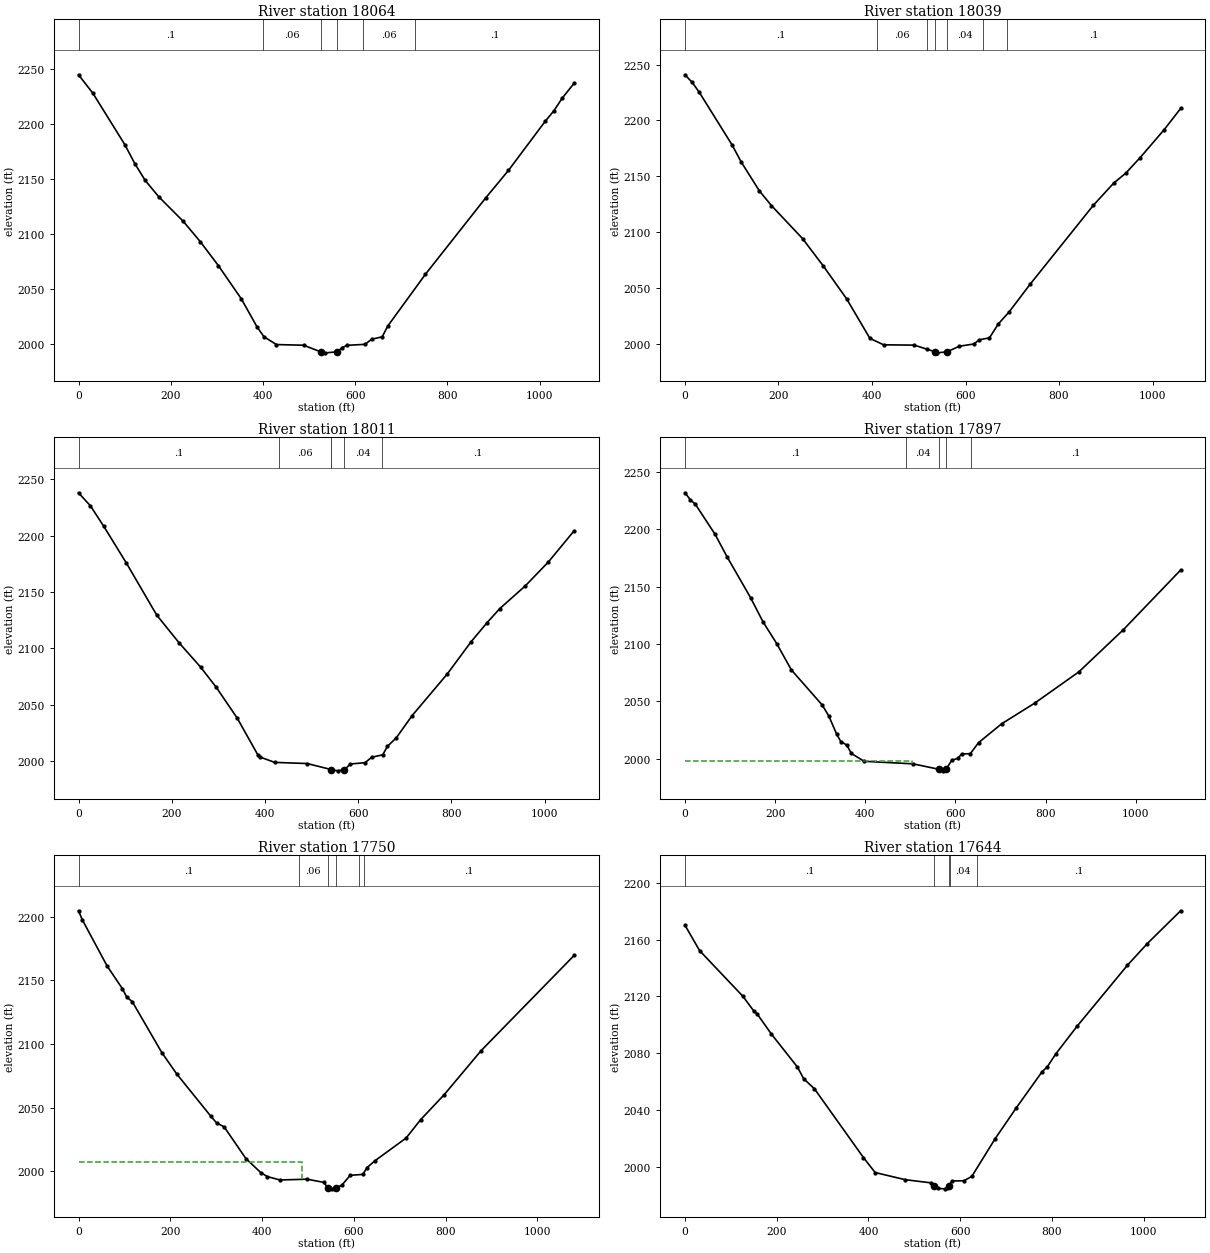
Type RM Length L Ch R = 1 ,18064   ,23.9,25.2,29.5
XS GIS Cut Line= 4
 2095982.3384494184029.3148452942096429.79303932184243.130171492
2096581.30456186 184306.849970692096966.45534813184459.777488766
#Sta/Elev= 30
       0 2244.91    31.2 2228.12   100.3 2181.57   122.1 2164.25   144.5 2149.03
   173.7 2134.27   227.4 2111.69   264.3 2093.23   303.1 2071.71   352.9 2041.51
   387.3 2015.83   402.2    2007   429.1 1999.94   488.2 1999.32  525.15 1993.33
   535.3 1992.42  561.061993.331   571.4 1997.06   582.1 1999.25   621.2 2000.13
   635.4 2004.73   658.4 2006.96     671 2017.02   752.1 2063.72   882.7 2133.02
   932.2 2158.05  1012.1 2202.79    1031 2212.35  1048.7 2223.65  1074.7 2237.28
#Mann= 6 ,-1 , 0
       0      .1       0     400     .06       0  525.15    .045       0
  561.06     .04       0  615.92     .06       0  730.28      .1       0
#XS Ineff= 2 , 0
          519.78 1993.39  564.67         1993.61
Permanent Ineff=
       F       F
Bank Sta=525.15,561.06
XS Rating Curve= 0 ,0
Exp/Cntr(USF)=0,0
Exp/Cntr=0.5,0.3

Type RM Length L Ch R = 1 ,18039   ,25.1,27.5,27.3
XS GIS Cut Line= 4
2095980.44840669184034.8129627922096441.12100363184271.450082247
2096595.46451724184364.9057877382096914.06351323184536.241247804
#Sta/Elev= 30
       0 2240.86    15.4 2234.04    30.1 2225.52   100.7 2178.11   120.2 2162.86
   159.2 2136.93     185 2123.79   251.4 2094.32   295.7 2069.85   345.8 2040.34
   395.5 2005.01   424.8 1999.25   490.5 1998.95   517.9 1995.27   535.31992.973
   539.9 1992.06  560.281992.973   586.6 1997.93   617.7 1999.99   629.6 2003.75
   651.2 2005.47   670.2 2017.93   693.4 2028.72   738.2 2053.45   873.3 2124.03
   916.9  2143.9   943.1 2152.98   973.7 2166.84    1025 2191.79  1060.1 2210.71
#Mann= 7 ,-1 , 0
       0      .1       0     410     .06       0   517.9     .04       0
   535.3    .045       0  560.28     .04       0   637.9     .06       0
   687.9      .1       0
#XS Ineff= 2 , 0
          518.18 1995.23  577.93         1996.13
Permanent Ineff=
       F       F
Bank Sta=535.3,560.28
XS Rating Curve= 0 ,0
Exp/Cntr(USF)=0,0
Exp/Cntr=0.5,0.3

Type RM Length L Ch R = 1 ,18011   ,109.4,114.2,116.6
XS GIS Cut Line= 4
2095975.25847171184039.2268140592096431.20903486184292.690015313
2096545.90467342184367.7377788132096891.40758463184578.721113936
#Sta/Elev= 30
       0 2238.01    25.7 2226.36    54.4 2208.15   102.7 2175.74   167.8 2129.63
     216 2104.92   261.8 2083.59   295.7 2065.53   340.6 2038.25   384.9 2005.64
   390.3 2003.67   421.1 1999.03   490.8 1998.02  542.841992.616     556 1991.55
  570.581992.615   583.5 1997.62   614.9 1998.78   629.1 2003.59   652.8 2005.75
     663 2013.33   681.9  2020.8   715.7 2040.41   791.2 2077.36   842.5    2106
     877 2123.01     904 2135.35   958.9 2155.56  1008.4 2176.75  1063.6 2204.36
#Mann= 6 ,-1 , 0
       0      .1       0     430     .06       0  541.67     .04       0
  542.84    .045       0  570.58     .04       0  651.67      .1       0
#XS Ineff= 2 , 0
          532.11 1993.73  577.54         1993.87
Permanent Ineff=
       F       F
Bank Sta=542.84,570.58
XS Rating Curve= 0 ,0
Exp/Cntr(USF)=0,0
Exp/Cntr=0.5,0.3

Type RM Length L Ch R = 1 ,17897   ,148.8,147.5,145.9
XS GIS Cut Line= 3
     2095963.078      184049.555     2096396.146       184395.61
     2096751.716      184808.891
#Sta/Elev= 30
       0 2231.94    11.9 2225.82    22.9 2222.01    66.5 2195.88    93.6 2175.88
   145.4 2140.47     173 2119.37   203.4 2100.37     236 2077.37   304.3 2046.77
   318.8 2037.36   336.4 2021.37   345.7 2014.75   358.9 2011.79   369.1 2004.44
   397.6 1997.59   505.9 1995.39  563.571990.613   572.1 1989.28  579.061990.614
   591.9  1998.5   604.7 2000.14     614 2004.01     633 2004.25   651.2 2013.86
   702.5 2030.34   775.9 2048.39   873.6 2075.61   972.3 2112.38  1099.5  2164.5
#Mann= 5 ,-1 , 0
       0      .1       0     490     .04       0  563.57    .045       0
  579.06     .04       0  634.35      .1       0
#XS Ineff= 2 , 0
          502.87  1998.3
Permanent Ineff=
       F       F
Bank Sta=563.57,579.06
XS Rating Curve= 0 ,0
Exp/Cntr=0.3,0.1

Type RM Length L Ch R = 1 ,17750   ,101.9,106,111.6
XS GIS Cut Line= 4
2095912.95466805184115.6905730962096264.12156141184473.937444143
2096400.05713303 184607.04102469 2096646.4403566 184907.23207869
#Sta/Elev= 30
       0  2204.5     8.1 2197.53      62 2161.36    95.7  2143.3   104.9 2136.82
   117.2 2133.16   181.5 2093.23   213.6 2076.62   288.2 2043.28   300.9    2038
   317.5 2034.84   364.8 2009.99   397.1 1999.04   411.2 1995.89     439 1993.17
   498.5 1993.79   534.1 1991.32  543.381987.209   552.7 1986.22  560.611987.208
   573.6 1988.96   592.1  1996.8   619.7 1997.57   628.8 2002.82   645.5  2008.1
     714 2026.11   745.5 2040.44   796.7    2060   877.5 2094.71  1080.3 2169.47
#Mann= 6 ,-1 , 0
       0      .1       0     480     .06       0  543.38    .045       0
  560.61     .06       0  611.66     .04       0  621.66      .1       0
#XS Ineff= 2 , 0
          486.53 2006.95
Permanent Ineff=
       F       F
Bank Sta=543.38,560.61
XS Rating Curve= 0 ,0
Exp/Cntr(USF)=0,0
Exp/Cntr=0.5,0.3

Type RM Length L Ch R = 1 ,17644   ,38.5,37.3,36.1
XS GIS Cut Line= 4
2095836.49090901 184200.650305362096203.23375329184550.401203181
2096281.11350786184655.1848729732096565.72861095 184995.02380203
#Sta/Elev= 30
       0 2170.16    31.9 2152.27   126.5 2120.06   149.8 2109.87     157 2107.89
   188.3 2093.59   245.2  2070.3   258.6 2062.17   282.3 2054.99     389 2006.63
   414.6 1996.05   480.7 1990.98   535.7 1988.82   543.6 1986.83   551.9 1984.83
     566 1984.57   570.7 1984.93  574.59 1986.88   582.4 1990.07   608.2 1990.28
   625.3 1993.32   676.1 2019.82   721.7 2041.32   778.4 2066.95   790.1 2070.59
   808.6 2079.66   854.6 2098.95   964.7 2142.01  1007.9 2157.25  1080.6 2180.34
#Mann= 5 ,-1 , 0
       0      .1       0   543.6    .045       0  574.59      .1       0
  576.78     .04       0  636.78      .1       0
#XS Ineff= 2 , 0
          527.67 1987.45  584.55         1987.45
Permanent Ineff=
       F       F
Bank Sta=543.6,574.59
XS Rating Curve= 0 ,0
Exp/Cntr(USF)=0,0
Exp/Cntr=0.5,0.3

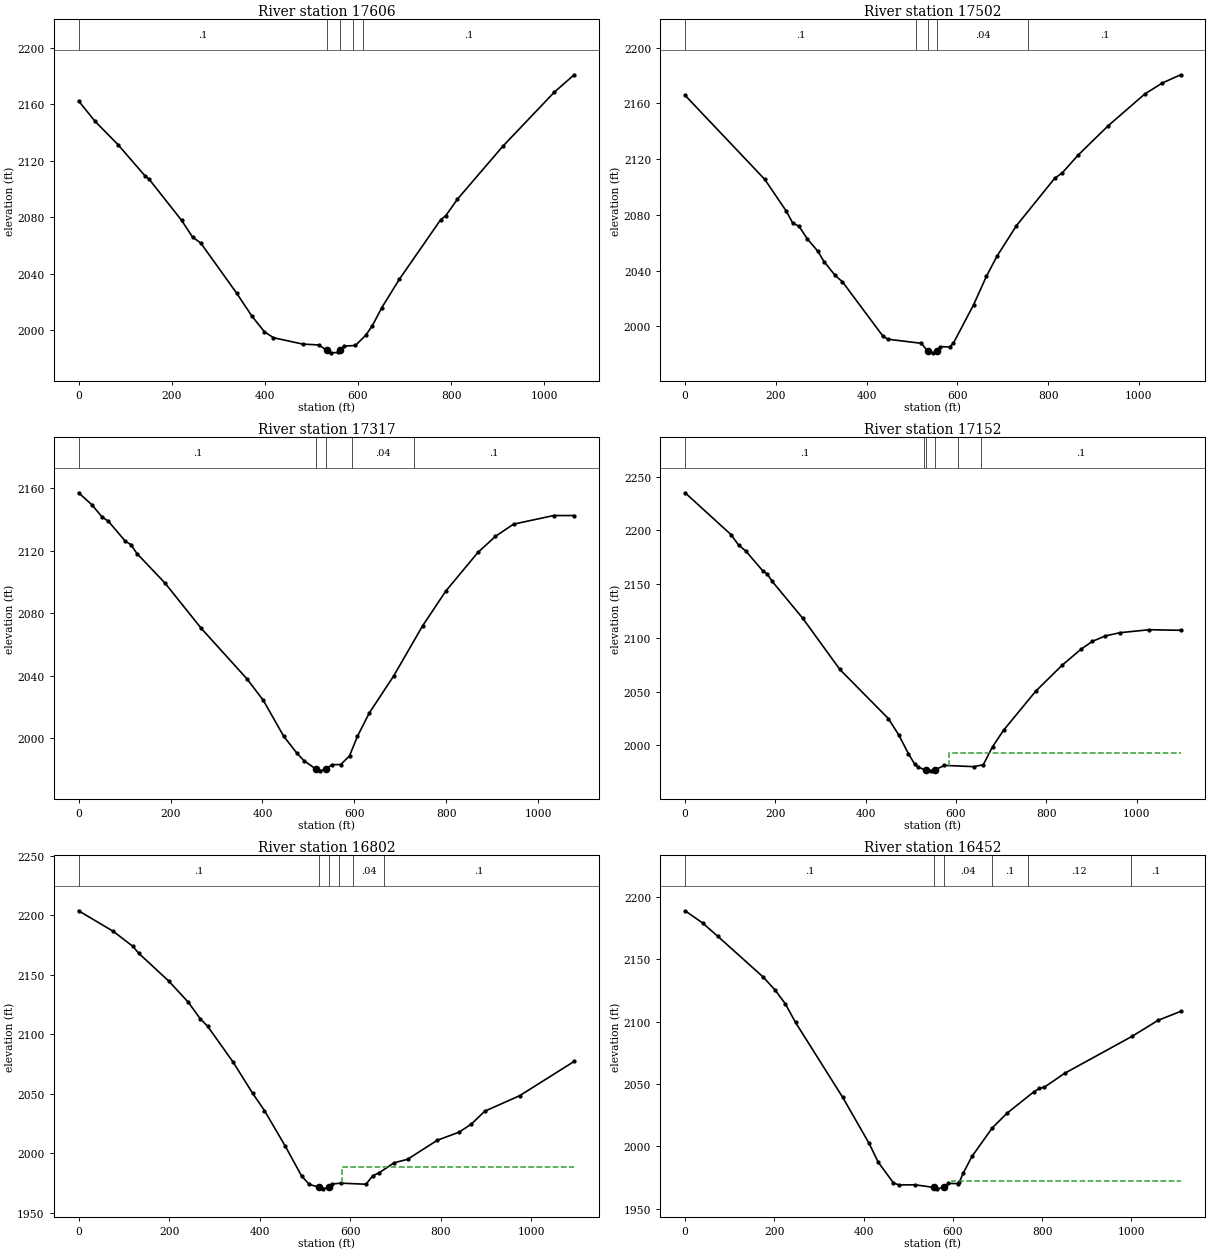
Type RM Length L Ch R = 1 ,17606   ,102.9,104,105.4
XS GIS Cut Line= 4
2095830.82692686184220.4742428892096170.66585592184573.057131785
 2096271.2015391184696.2487435682096527.49673143185023.343712785
#Sta/Elev= 30
       0 2162.41    34.5 2148.25    84.6 2131.41   142.3 2109.43   151.6 2106.87
   221.3  2077.7   244.7  2065.9   262.3  2061.7   339.5 2026.13     372 2009.95
     399 1998.83   418.4 1994.62     481  1990.1     516 1989.45   532.5 1985.76
   542.5 1983.88   556.8 1984.16   562.1 1985.66   569.6 1988.64   594.4  1989.1
   616.3 1996.21   630.3 2002.81   651.2 2015.92   688.6 2035.91   777.4 2078.18
   788.5 2081.08   813.5 2092.75   910.6 2130.12  1021.9 2168.72  1064.3 2180.95
#Mann= 5 ,-1 , 0
       0      .1       0   532.5    .045       0   562.1      .1       0
   589.7     .04       0   609.7      .1       0
#XS Ineff= 2 , 0
          527.92 1986.03  564.83         1986.11
Permanent Ineff=
       F       F
Bank Sta=532.5,562.1
XS Rating Curve= 0 ,0
Exp/Cntr(USF)=0,0
Exp/Cntr=0.5,0.3

Type RM Length L Ch R = 1 ,17502   ,186.4,184.9,183.5
XS GIS Cut Line= 3
     2095800.892      184241.614     2096124.973      184681.383
     2096446.087      185122.912
#Sta/Elev= 30
       0 2165.81   175.7 2105.45   222.9 2082.74     237 2074.28   251.1 2071.77
   269.5 2062.72   292.5 2053.94   306.1 2046.52   330.6 2036.56   346.9 2031.93
   436.4 1992.78   447.3 1990.72   520.9  1987.8  534.781982.113   546.6 1980.96
  554.281982.113   562.8  1985.4   583.1 1985.18   591.2 1987.82     636 2015.55
     664 2035.81   687.6 2050.45   729.9 2072.07   814.6 2106.26   831.4 2110.19
   866.1 2122.86   932.5 2143.98  1013.1 2166.76  1051.5 2174.63  1092.2 2180.58
#Mann= 5 ,-1 , 0
       0      .1       0     510     .04       0  534.78    .045       0
  554.28     .04       0  756.28      .1       0
Bank Sta=534.78,554.28
XS Rating Curve= 0 ,0
Exp/Cntr=0.3,0.1

Type RM Length L Ch R = 1 ,17317   ,169.3,165.1,160.6
XS GIS Cut Line= 4
2095628.91767081184407.4198906672095948.30333099184758.272118351
2096094.62286989184929.7649112542096360.51536531185198.804063424
#Sta/Elev= 30
       0 2157.18    29.2  2149.4    50.8 2141.71    64.7 2138.92   101.9 2126.02
   113.6 2123.98   126.8 2118.24   187.9  2099.3   266.8 2070.24   366.7  2037.7
   401.9 2024.03   446.2 2001.03   474.5 1990.38   489.8 1985.51  516.851979.892
   524.7 1978.89  538.611979.892   550.3 1982.81   570.3 1982.95   589.4 1988.52
   606.6 2001.04   632.5 2016.08   685.3 2039.67   748.2  2071.8     799 2094.23
   868.6 2118.89   906.9 2129.25   946.1 2137.05  1033.7  2142.6  1078.1 2142.56
#Mann= 5 ,-1 , 0
       0      .1       0  516.85    .045       0  538.61      .1       0
  594.45     .04       0  729.88      .1       0
Bank Sta=516.85,538.61
XS Rating Curve= 0 ,0
Exp/Cntr(USF)=0,0
Exp/Cntr=0.3,0.1

Type RM Length L Ch R = 1 ,17152   ,362.3,350,341.9
XS GIS Cut Line= 3
     2095434.697      184580.102     2095865.522      184913.644
     2096307.943      185244.622
#Sta/Elev= 30
       0 2234.97   101.6 2196.07   118.3 2186.42   134.4 2180.78   172.2 2162.25
   181.1 2159.84     193 2152.47   260.7 2118.11   342.7 2070.57   450.1 2024.87
   473.5  2009.4   494.5 1992.17   508.3 1982.59   516.6 1979.44  532.671977.106
   545.6 1976.22  553.621977.105   574.3  1981.3   639.9  1980.1   660.4 1981.94
   680.8 1998.62   705.3 2014.03   776.4 2050.29   834.3 2074.26   877.5 2089.65
   902.2 2096.77   930.8 2101.78   963.2 2104.77  1028.4 2107.55  1097.4    2107
#Mann= 6 ,-1 , 0
       0      .1       0     530     .04       0  532.67    .045       0
  553.62     .04       0  604.85     .06       0  654.85      .1       0
#XS Ineff= 2 , 0
                          584.53         1993.05
Permanent Ineff=
       F       F
Bank Sta=532.67,553.62
XS Rating Curve= 0 ,0
Exp/Cntr=0.3,0.1

Type RM Length L Ch R = 1 ,16802   ,340.4,350,353.1
XS GIS Cut Line= 3
     2095186.036      185165.385     2095727.595      185229.638
     2096266.273      185338.859
#Sta/Elev= 30
       0 2203.63      77 2186.24   119.9 2173.75   133.1 2167.84   199.2  2144.6
   242.2 2126.91   268.3 2113.19   285.1 2106.63   341.3 2076.61   384.2 2050.57
   410.7 2035.87   456.9 2005.85   492.8 1980.86   509.8 1973.85  531.491971.601
   539.5 1970.19  552.831971.603   559.5 1974.24   579.6 1974.95     635 1974.06
   649.9 1981.23   663.3 1983.48   696.8 1992.02   726.9 1995.01   792.5 2010.96
   840.7 2017.79   867.5 2024.46   897.6  2035.4   974.8 2048.44    1095 2077.19
#Mann= 6 ,-1 , 0
       0      .1       0  531.49    .045       0  552.83      .1       0
  575.36     .06       0  605.36     .04       0  675.36      .1       0
#XS Ineff= 2 , 0
                          581.09         1988.41
Permanent Ineff=
       F       F
Bank Sta=531.49,552.83
XS Rating Curve= 0 ,0
Exp/Cntr=0.3,0.1

Type RM Length L Ch R = 1 ,16452   ,518.7,519.3,522.1
XS GIS Cut Line= 3
     2095156.447      185279.904     2095648.835      185563.052
     2096154.589      185758.258
#Sta/Elev= 30
       0 2188.84      39 2179.13    73.1 2168.45   175.3 2135.63   201.8 2125.23
   224.5 2114.32   247.4 2099.36   353.1 2039.33   412.3 2002.39   432.6 1987.41
   466.1 1971.12   478.1 1969.17   515.9 1969.28  557.051967.151   563.7 1966.05
  580.74 1967.15   589.8 1970.37     611 1970.29   614.5 1971.57   622.8 1978.48
   642.7 1992.09   688.4    2015   721.7 2026.81   780.7 2043.64   793.9 2046.64
   804.5 2047.43   850.2 2058.59  1001.4 2088.27  1059.9 2101.13  1110.1 2108.22
#Mann= 6 ,-1 , 0
       0      .1       0  557.05    .045       0  580.74     .04       0
     688      .1       0     768     .12       0     998      .1       0
#XS Ineff= 2 , 0
                          598.14         1972.47
Permanent Ineff=
       F       F
Bank Sta=557.05,580.74
XS Rating Curve= 0 ,0
Exp/Cntr=0.3,0.1

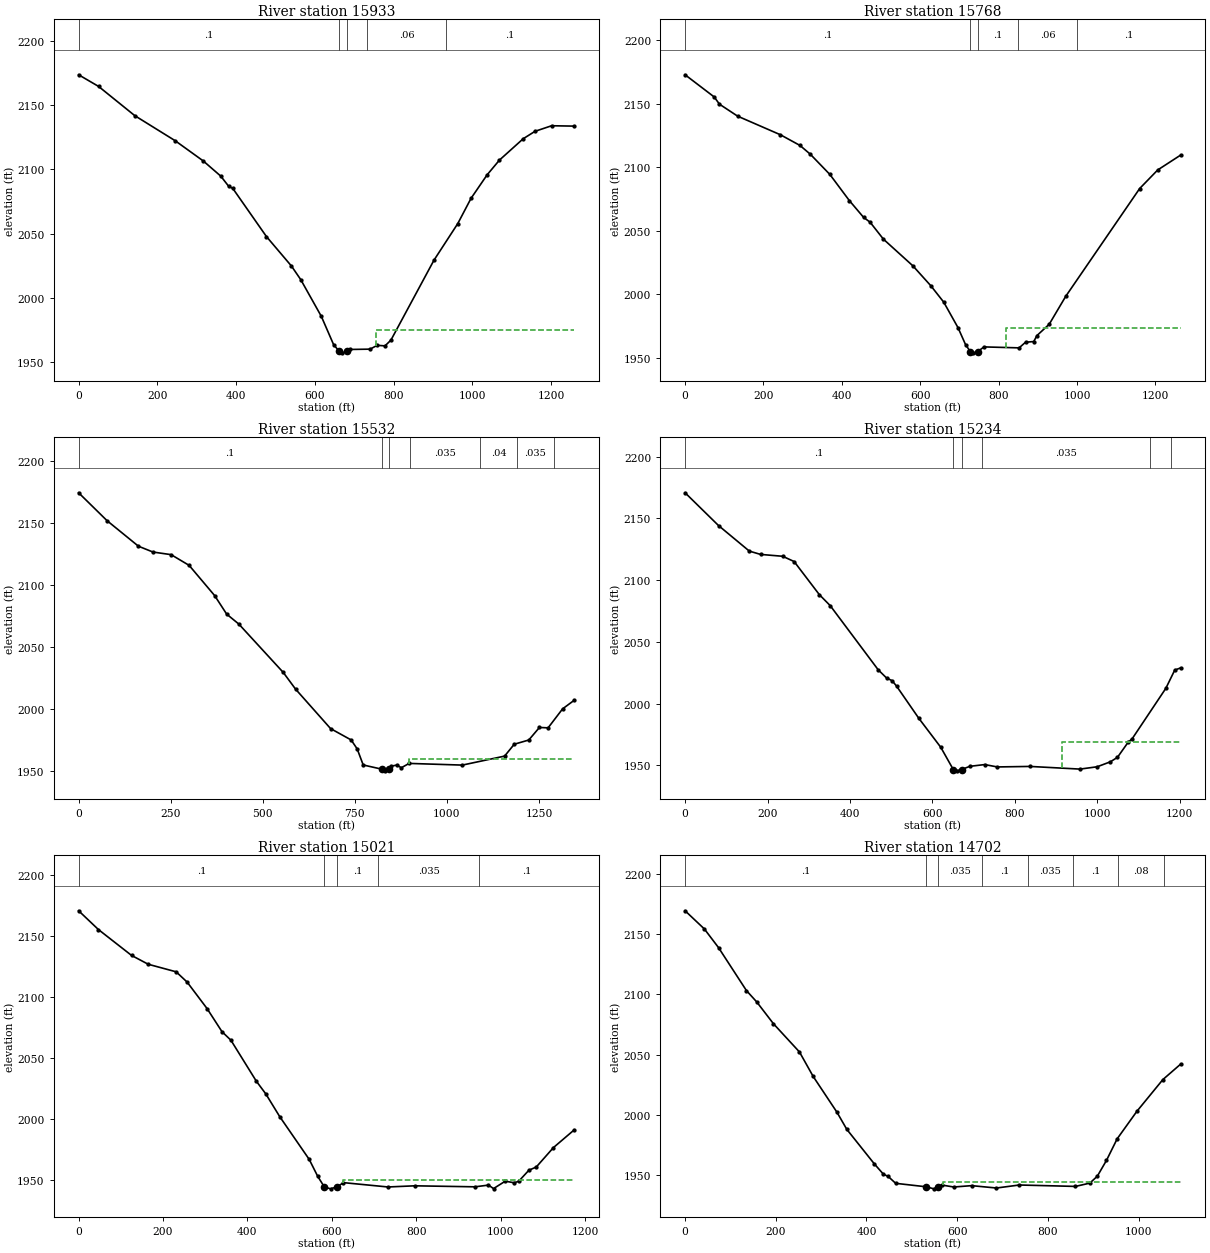
Type RM Length L Ch R = 1 ,15933   ,157.9,164.9,171.9
XS GIS Cut Line= 3
     2095119.992      185420.367     2095265.391       185932.52
     2095896.902      186290.593
#Sta/Elev= 30
       0 2173.44    50.6  2164.4   142.7 2141.64     245  2122.2   316.6 2106.41
   360.9 2094.65   381.4 2086.59   391.2  2085.2   476.9 2047.66   540.4 2024.74
   563.9 2014.24   616.3 1985.61   647.5  1963.6  661.991958.359   668.6 1957.23
  681.621958.358   688.5 1959.85   740.2 1960.11   758.3 1963.08     778 1962.64
     793 1967.09   902.4 2029.29   962.8 2057.72   996.5 2077.37  1037.4 2095.67
  1068.7 2107.12  1128.9 2123.69  1158.9 2129.47  1201.1 2133.81  1258.4 2133.52
#Mann= 5 ,-1 , 0
       0      .1       0  661.99    .045       0  681.62      .1       0
  732.39     .06       0  932.39      .1       0
#XS Ineff= 2 , 0
                          754.15         1974.83
Permanent Ineff=
       F       F
Bank Sta=661.99,681.62
XS Rating Curve= 0 ,0
Exp/Cntr=0.3,0.1

Type RM Length L Ch R = 1 ,15768   ,221.9,236.1,248.5
XS GIS Cut Line= 4
2095111.48198097185434.6835281132095193.04332394186019.631284752
2095398.22107736186264.3153136722095640.35631431186523.017698417
#Sta/Elev= 30
       0 2172.68    74.4  2155.2    87.7 2149.55   134.1 2140.13   243.4 2125.48
   293.1 2117.11   319.6 2110.17   369.3 2094.32   418.9 2073.81   455.4 2060.55
   471.9 2056.78     506 2043.41   581.3 2022.39   627.2 2006.68   659.9 1993.87
   696.2 1973.87   715.5 1960.52  727.65 1955.03   735.8 1954.02  746.711955.031
   762.6 1958.69   852.2 1957.93   868.5 1962.34   889.5 1962.91   897.8 1967.64
     929  1976.5     971  1998.4  1159.8 2083.24  1205.8 2097.83  1264.3 2109.52
#Mann= 5 ,-1 , 0
       0      .1       0  727.65    .045       0  746.71      .1       0
  850.61     .06       0  999.93      .1       0
#XS Ineff= 2 , 0
                          818.34         1973.18
Permanent Ineff=
       F       F
Bank Sta=727.65,746.71
XS Rating Curve= 0 ,0
Exp/Cntr(USF)=0,0
Exp/Cntr=0.3,0.1

Type RM Length L Ch R = 1 ,15532   ,285.8,298.1,307.4
XS GIS Cut Line= 2
     2095100.461      185431.218     2095104.801      186776.704
#Sta/Elev= 30
       0 2174.11    77.2 2151.61   162.5 2131.01   201.9 2126.33   251.1 2124.23
     300  2115.6   369.3 2091.23     402 2076.28     435 2068.26   555.7 2029.24
     589 2015.83   684.1    1984   739.9 1974.85   756.3 1967.64   772.7 1954.66
  823.551951.265   831.8 1949.94     8421951.267   848.2 1953.71   864.6  1954.6
     876 1952.41   897.4 1955.93  1041.8 1954.57  1156.6 1961.82  1182.8  1971.4
  1222.2 1974.78  1251.2 1984.91  1274.7  1984.6  1314.1 1999.92  1345.5 2006.81
#Mann= 7 ,-1 , 0
       0      .1       0  823.55    .045       0     842      .1       0
     900    .035       0    1090     .04       0    1190    .035       0
    1290      .1       0
#XS Ineff= 2 , 0
                          896.17         1959.87
Permanent Ineff=
       F       F
Bank Sta=823.55,842
XS Rating Curve= 0 ,0
Exp/Cntr=0.3,0.1

Type RM Length L Ch R = 1 ,15234   ,212.6,213.3,213.1
XS GIS Cut Line= 4
2095093.35723809185446.4362910762094938.16412715186027.277660655
2094852.77959622186158.5404470032094631.03469502 186543.40803416
#Sta/Elev= 30
       0 2170.74    81.1 2144.18   155.8 2123.48     183 2120.81   236.7 2119.29
   264.5 2115.03   325.6 2088.22     352  2079.3   468.3 2027.35   488.7 2020.67
   502.1  2018.5   512.8 2014.16   566.7 1988.11   620.2 1964.52  650.51 1946.52
   659.3 1945.45  670.751946.521   690.6  1949.1   726.9 1950.53   757.2 1948.61
   836.7 1949.02   957.9 1946.86   999.5 1948.74  1031.6 1952.77  1048.8 1956.41
  1074.8 1968.68  1084.4 1971.42  1166.1  2012.3  1187.7 2027.08    1202 2028.86
#Mann= 6 ,-1 , 0
       0      .1       0  650.51    .045       0  670.75      .1       0
  721.22    .035       0 1127.81      .1       0 1177.81     .06       0
#XS Ineff= 2 , 0
                          914.61         1968.87
Permanent Ineff=
       F       F
Bank Sta=650.51,670.75
XS Rating Curve= 0 ,0
Exp/Cntr(USF)=0,0
Exp/Cntr=0.3,0.1

Type RM Length L Ch R = 1 ,15021   ,326.6,318.3,308.4
XS GIS Cut Line= 2
       2095083.1      185444.239     2094421.207      186414.291
#Sta/Elev= 30
       0 2170.83    46.9 2155.43   125.3 2134.23     165 2126.94   231.1 2120.75
   257.1 2112.33   304.3 2090.63   339.8 2071.61   360.9 2064.62     421 2031.08
   443.6 2020.57   476.6 2001.91   546.4 1966.87   566.5 1953.02   582.1 1944.34
     597 1942.68   613.1 1944.43   627.7 1947.77     733 1944.21   796.6 1945.16
   939.4 1944.34   971.3 1945.75   983.3 1942.89  1011.1 1948.97  1032.2 1947.66
  1042.8 1948.85  1067.1 1957.95  1084.6 1960.59  1125.3 1976.54  1174.4 1991.04
#Mann= 5 ,-1 , 0
       0      .1       0   582.1    .045       0   613.1      .1       0
     710    .035       0     950      .1       0
#XS Ineff= 2 , 0
                          627.59         1950.28
Permanent Ineff=
       F       F
Bank Sta=582.1,613.1
XS Rating Curve= 0 ,0
Exp/Cntr=0.3,0.1

Type RM Length L Ch R = 1 ,14702   ,343.9,350,347.5
XS GIS Cut Line= 3
     2094575.726      185295.593     2094451.872      185826.773
     2094328.768      186360.113
#Sta/Elev= 30
       0 2169.52    42.5  2154.4    73.7 2138.91   135.3 2103.17   157.9 2093.78
   194.9  2075.6   252.2 2052.16   282.5 2031.78   334.8 2002.11   356.6 1987.83
   417.3 1959.13   437.5 1950.47   447.6 1948.76   464.4 1942.96  532.291940.054
   548.7 1938.38  556.86 1940.06   565.5 1941.57   592.4 1939.91   631.9 1941.03
   686.7 1939.07   737.2 1941.57   860.8 1940.39   892.6 1943.15     909 1948.86
   929.2 1961.99   952.8 1979.95   996.5 2002.92  1053.7 2029.24  1092.8 2042.04
#Mann= 8 ,-1 , 0
       0      .1       0  532.29    .045       0  556.86    .035       0
  655.43      .1       0  755.43    .035       0  855.43      .1       0
  955.43     .08       0 1055.43      .1       0
#XS Ineff= 2 , 0
                          567.71         1944.41
Permanent Ineff=
       F       F
Bank Sta=532.29,556.86
XS Rating Curve= 0 ,0
Exp/Cntr=0.3,0.1