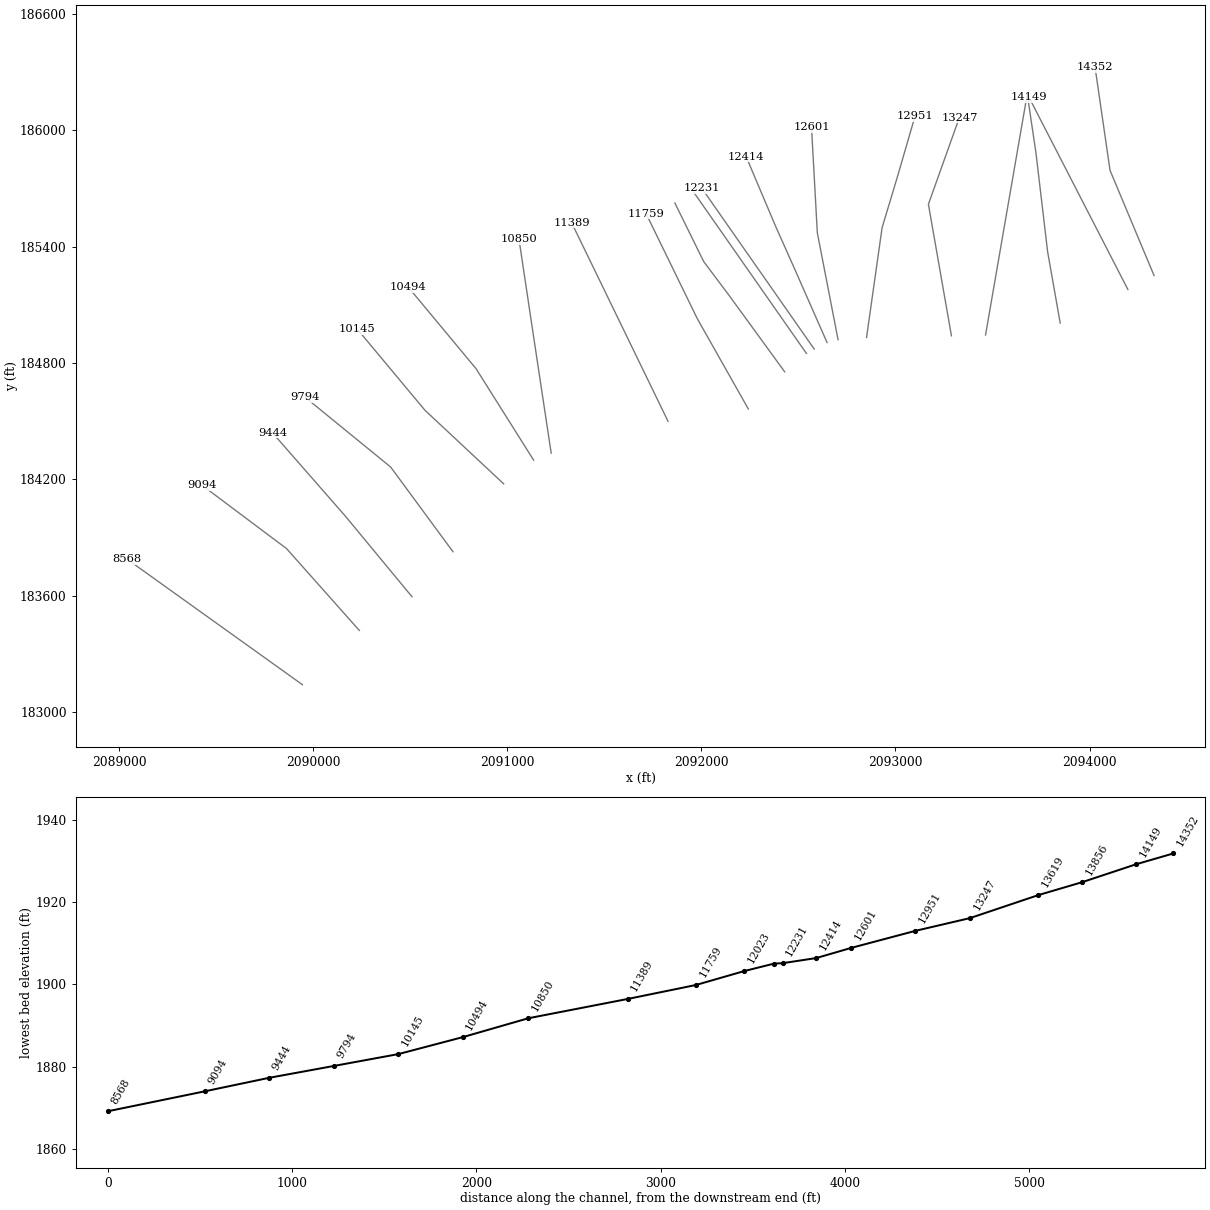
HEC-RAS study DRPLKCR.prj: DRPLKCR

--- DRPLKCR.g01 (geometry) --- (continued)

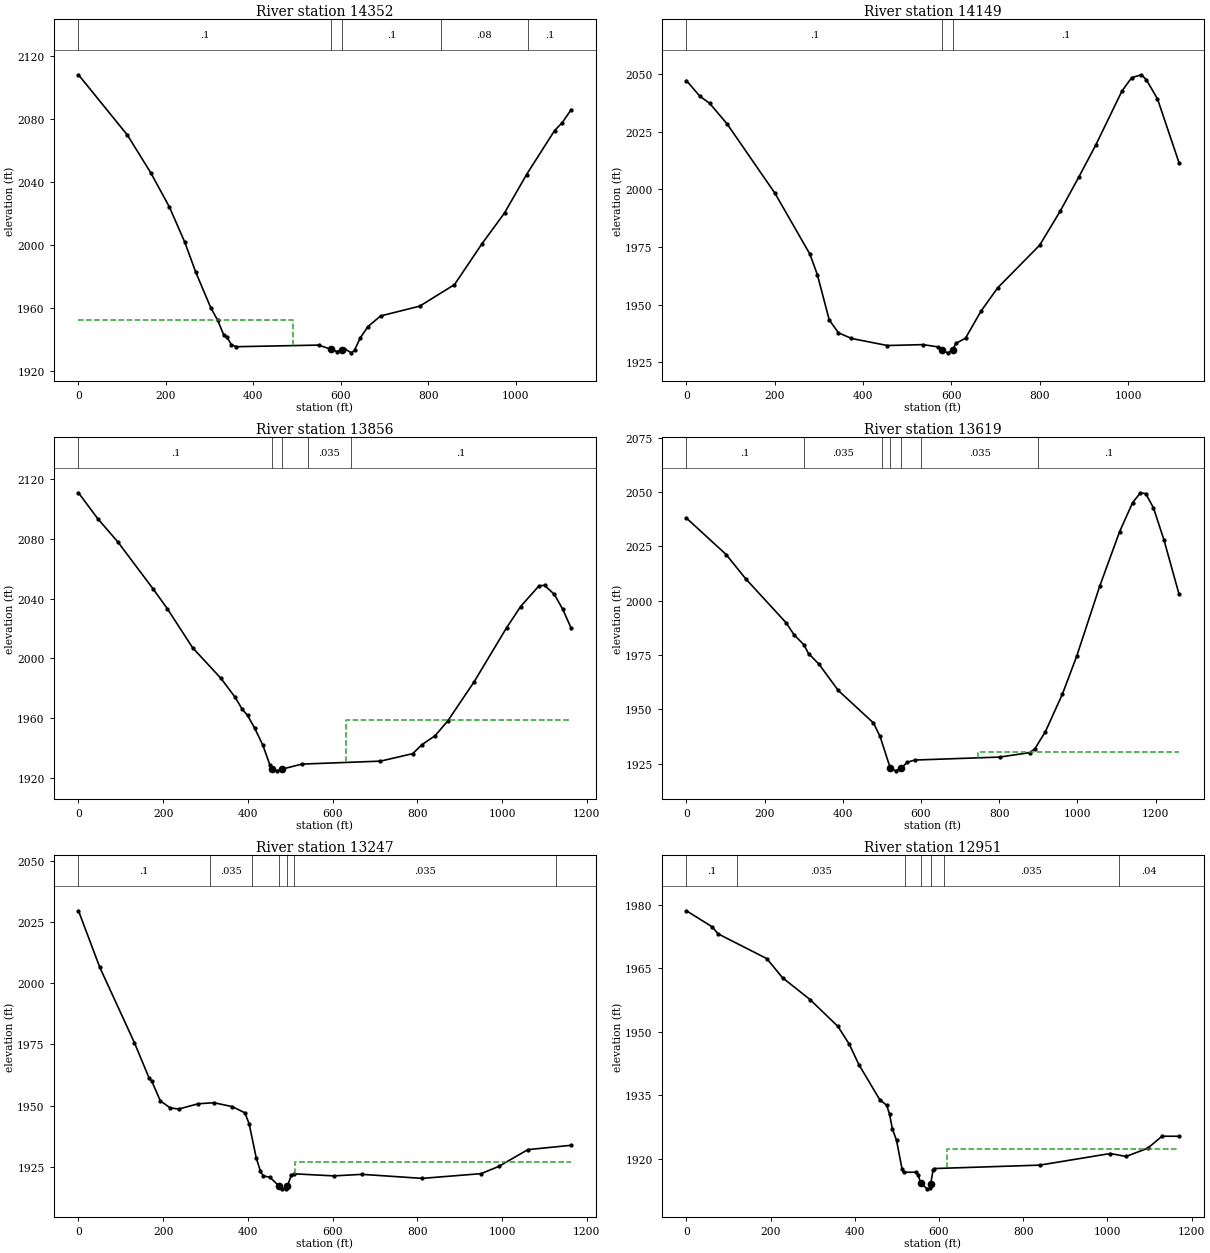
Type RM Length L Ch R = 1 ,14352   ,197.8,203.6,212.3
XS GIS Cut Line= 3
     2094332.604      185251.212     2094105.668      185793.821
     2094028.303      186326.796
#Sta/Elev= 30
       0  2107.8   111.6 2069.73     165 2045.93   207.7 2024.23     243 2001.91
   268.2 1982.87   302.5 1960.35   318.4 1952.44   332.1 1943.24   339.2  1941.8
   349.9 1936.97     361 1935.68   549.1  1936.7   577.5 1934.06   591.5 1932.59
   603.8 1933.88   608.1 1934.42   624.1  1931.8   631.3 1933.51   644.5 1941.25
   661.7  1948.3   690.9 1955.15   780.5 1961.35     860    1975     923 2000.91
   974.4 2020.32  1024.8 2044.65  1088.8 2072.45  1106.3 2077.47  1126.7 2085.67
#Mann= 5 ,-1 , 0
       0      .1       0   577.5    .045       0   603.8      .1       0
  828.15     .08       0 1028.15      .1       0
#XS Ineff= 2 , 0
          491.69 1952.43
Permanent Ineff=
       F       F
Bank Sta=577.5,603.8
XS Rating Curve= 0 ,0
Exp/Cntr=0.3,0.1

Type RM Length L Ch R = 1 ,14149   ,299.3,292.1,285.4
XS GIS Cut Line= 2
     2094197.683      185179.482       2093687.7      186171.235
#Sta/Elev= 30
       0 2047.17    30.5 2040.34    52.6 2037.29    91.9 2028.41   200.2 1998.38
   279.5 1971.95   296.5 1962.97   323.3 1943.44     344 1937.85   373.6 1935.39
   454.9 1932.32   535.9 1932.71   569.1 1931.74  579.471930.298   591.2 1929.15
  602.811930.297   609.7  1933.2   631.8 1935.51   666.8 1947.19   704.8 1957.36
   799.6 1975.78   845.8 1990.42   888.6 2005.44   926.9 2019.28     986 2042.61
  1007.9 2048.39  1030.2 2049.65  1041.3 2047.45  1066.4 2039.22  1115.2 2011.54
#Mann= 3 ,-1 , 0
       0      .1       0  579.47    .045       0  602.81      .1       0
Bank Sta=579.47,602.81
XS Rating Curve= 0 ,0
Exp/Cntr=0.3,0.1

Type RM Length L Ch R = 1 ,13856   ,240.6,237.8,228
XS GIS Cut Line= 4
2093848.88421168 185006.75128634  2093784.138188185373.645420489
2093724.18816608185882.0216063692093683.42215118  186157.7917072
#Sta/Elev= 30
       0 2110.83    45.4 2093.53      93 2077.93   176.3 2046.49   209.6 2033.36
   269.5 2007.16   336.2 1986.74   369.5 1974.18     386 1966.32   399.2 1961.85
   415.8  1953.5   435.6 1941.83   452.1 1928.58  457.631926.028   468.5 1924.81
  481.671926.028   527.6 1929.32   713.1  1931.3   789.1  1936.3   811.3 1942.39
   841.9 1948.29   871.7 1958.08   934.6 1984.56  1010.9 2020.57    1044 2034.72
  1087.4  2048.6  1100.4 2048.93  1123.7 2042.85  1143.6  2032.8  1163.2 2020.37
#Mann= 5 ,-1 , 0
       0      .1       0  457.63    .045       0  481.67      .1       0
  542.56    .035       0  642.56      .1       0
#XS Ineff= 2 , 0
                          630.95          1958.5
Permanent Ineff=
       F       F
Bank Sta=457.63,481.67
XS Rating Curve= 0 ,0
Exp/Cntr(USF)=0,0
Exp/Cntr=0.3,0.1

Type RM Length L Ch R = 1 ,13619   ,363.7,371.6,379.7
XS GIS Cut Line= 2
     2093464.176      184945.107      2093679.02      186186.426
#Sta/Elev= 30
       0 2038.04   101.7 2021.24   152.1 2009.99   255.4 1989.75   275.3 1984.28
   300.3 1979.75   312.3 1975.64   338.6 1970.87   388.3 1958.69   478.4  1943.7
   495.1 1937.56  521.421922.863   535.1 1921.67  549.091922.862     565 1925.66
   584.2 1926.64   801.4 1928.01     878 1930.06   891.3 1931.89     918 1939.68
   961.7 1957.08   997.9 1974.35  1057.2 2006.79  1107.7 2031.72    1141  2045.1
    1161 2049.68  1174.6 2049.29  1194.3 2042.79    1221 2028.13  1259.8 2002.99
#Mann= 7 ,-1 , 0
       0      .1       0     300    .035       0     500      .1       0
  521.42    .045       0  549.09      .1       0     600    .035       0
     900      .1       0
#XS Ineff= 2 , 0
                           745.6         1930.33
Permanent Ineff=
       F       F
Bank Sta=521.42,549.09
XS Rating Curve= 0 ,0
Exp/Cntr=0.3,0.1

Type RM Length L Ch R = 1 ,13247   ,300.9,295.9,287.1
XS GIS Cut Line= 3
     2093288.395      184940.7662093169.74231116 185619.01777017
2093329.29894279186066.145866133
#Sta/Elev= 30
       0  2029.5  50.0192006.541 132.0831975.682 166.5921961.345 173.2541959.893
 193.2381951.984 216.5521949.089 236.5361948.631 283.1651950.787 319.8031951.198
 363.101 1949.62 393.0771947.056 403.0691942.568 419.7221928.689 429.7141923.259
 436.3761921.355 451.6221920.827  473.881917.225 479.6741916.076 489.6661916.074
  493.461917.277 502.6481921.629  509.651922.199 602.9081921.357 669.5221921.984
 811.4711920.342 950.8091922.268 992.6111925.2311061.2071932.0631163.296 1933.84
#Mann= 7 ,-1 , 0
       0      .1       0     310    .035       0     410      .1       0
  473.88    .045       0  493.46      .1       0     510    .035       0
 1128.55      .1       0
#XS Ineff= 2 , 0
                           510.6         1926.89
Permanent Ineff=
       F       F
Bank Sta=473.88,493.46
XS Rating Curve= 0 ,0
Exp/Cntr=0.3,0.1

Type RM Length L Ch R = 1 ,12951   ,340.9,350,355.8
XS GIS Cut Line= 4
     2092850.995      184932.264      2092931.07      185498.166
 2093007.6894885185752.7506820692093100.54129863186072.092493135
#Sta/Elev= 30
       01978.549  61.6621974.733  74.9161973.126 190.8891967.272 228.2461962.765
 293.6081957.616 359.8781951.276 386.3871947.153 409.5811942.279 459.2841933.988
 475.8511932.661 482.4781930.541 489.105 1927.15 499.0461924.407   512.31917.556
 515.6141916.887 545.4351916.907 550.4541916.236  556.741914.267 571.9571912.982
 578.8091913.198   580.31914.222 585.6621917.351 589.0881917.767 839.1951918.573
1006.6141921.3081044.198 1920.621095.4481922.5481129.615 1925.39 1169.97 1925.38
#Mann= 7 ,-1 , 0
       0      .1       0     120    .035       0     520      .1       0
  556.74    .045       0   580.3      .1       0  611.54    .035       0
  1027.4     .04       0
#XS Ineff= 2 , 0
                          618.91         1922.36
Permanent Ineff=
       F       F
Bank Sta=556.74,580.3
XS Rating Curve= 0 ,0
Exp/Cntr=0.3,0.1

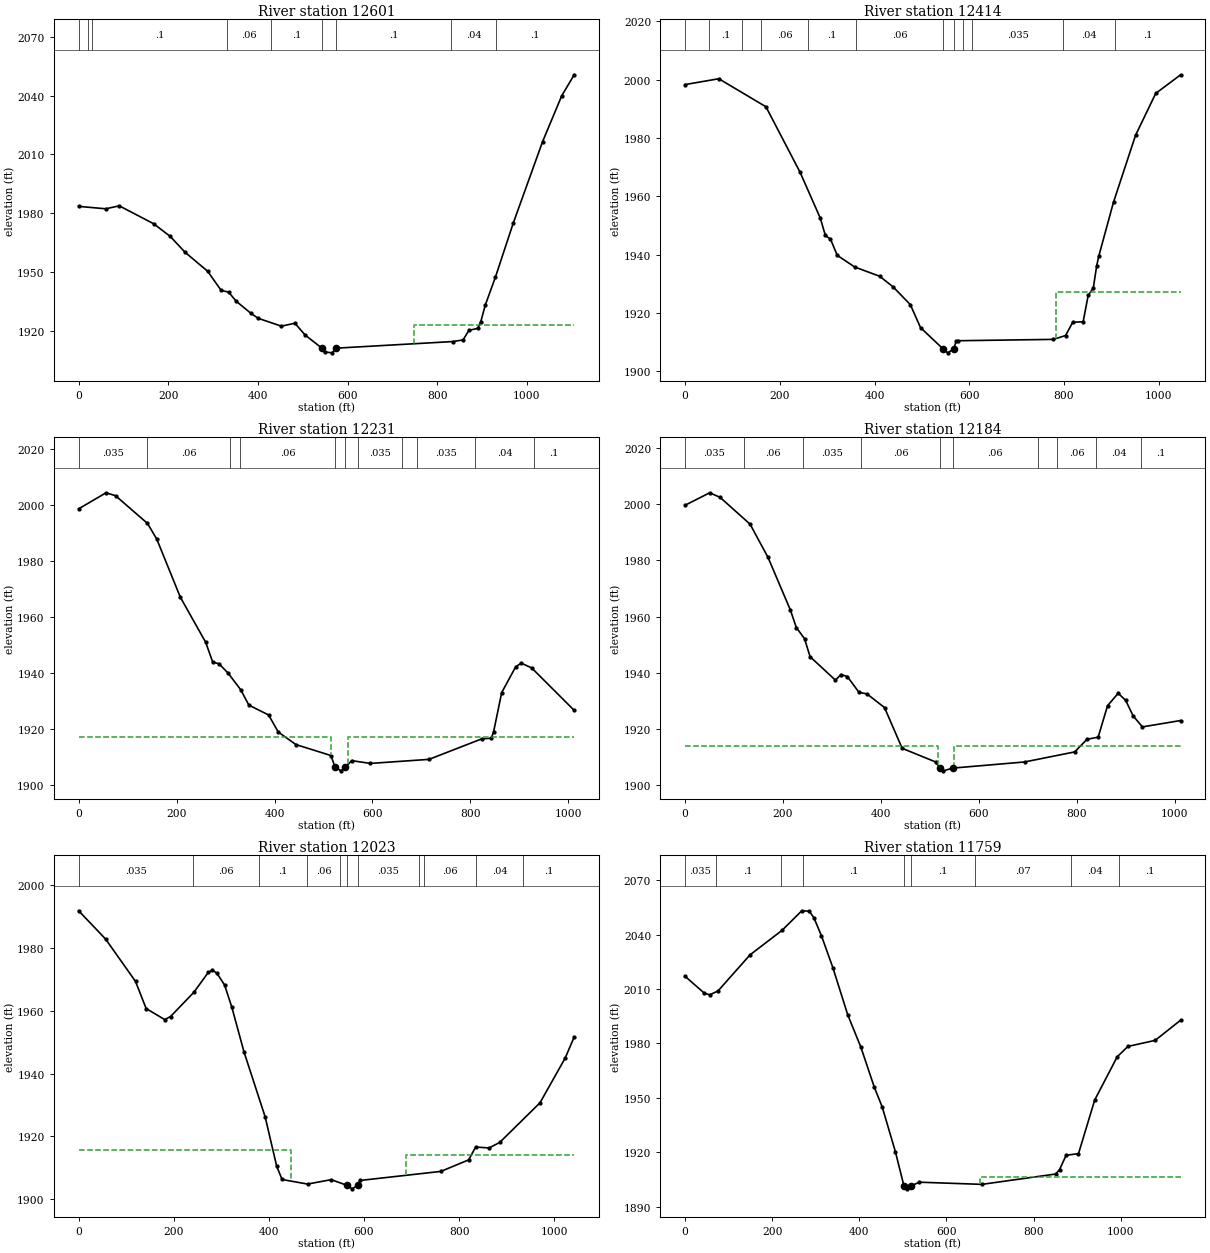
Type RM Length L Ch R = 1 ,12601   ,181.6,187.4,194.1
XS GIS Cut Line= 3
     2092704.249      184920.714     2092597.352      185471.546
      2092567.42       186015.03
#Sta/Elev= 30
       0 1983.52    60.6 1982.29    90.7  1983.8   167.5 1974.64   204.3 1968.21
   237.7 1960.05   287.8 1950.44   317.9 1940.66   334.6 1939.79   351.3 1935.18
   384.5 1928.95   400.4 1926.45   452.1 1922.43   482.5 1923.92   505.1 1917.92
   541.8 1911.38   548.5 1909.28   565.2 1908.82     575 1911.21   834.3 1914.57
   857.6 1915.41   870.7 1920.31   890.5  1921.3   897.2 1924.77   906.9 1933.04
   929.9 1947.54   969.3 1974.85    1035 2016.58  1077.7 2039.95  1105.4 2050.64
#Mann= 9 ,-1 , 0
       0      .1       0      20    .035       0      30      .1       0
     330     .06       0     430      .1       0   541.8    .045       0
     575      .1       0  831.11     .04       0  931.11      .1       0
#XS Ineff= 2 , 0
                          747.85         1922.96
Permanent Ineff=
       F       F
Bank Sta=541.8,575
XS Rating Curve= 0 ,0
Exp/Cntr=0.3,0.1

Type RM Length L Ch R = 1 ,12414   ,177.1,182.7,185.2
XS GIS Cut Line= 4
2092647.48577241184906.0352495152092479.62571103185287.317388925
2092381.30767508185507.9334695892092230.23361984185865.235600231
#Sta/Elev= 30
       0  1998.3    71.1 2000.29   170.6  1990.7   242.8 1968.23   285.4 1952.54
   296.1  1946.6   306.9 1945.34   321.2 1939.79   357.9  1935.8   410.8 1932.61
   439.4 1928.95   475.5 1922.88     497 1915.02  544.841907.686   554.5 1906.38
  566.831907.686   572.4 1910.37     576 1910.53   777.4 1910.99   803.2 1912.31
   818.3 1916.85   840.3 1917.04     851 1926.13   861.7 1928.54   868.8 1936.14
   873.3 1939.52   904.4 1958.02   950.9 1980.91   993.5 1995.27  1046.1 2001.65
#Mann= 12 ,-1 , 0
       0    .035       0      50      .1       0     120    .035       0
     160     .06       0     260      .1       0     360     .06       0
  544.84    .045       0  566.83     .06       0   586.6      .1       0
   606.6    .035       0  798.13     .04       0  908.13      .1       0
#XS Ineff= 2 , 0
                          782.23         1927.28
Permanent Ineff=
       F       F
Bank Sta=544.84,566.83
XS Rating Curve= 0 ,0
Exp/Cntr(USF)=0,0
Exp/Cntr=0.5,0.3

Type RM Length L Ch R = 1 ,12231   ,45.9,46.4,46.3
XS GIS Cut Line= 2
     2092581.295      184872.435     2092001.868      185701.863
#Sta/Elev= 30
       0 1998.74      56 2004.48    75.4 2003.43   140.5 1993.55   159.5 1987.95
   207.5 1967.23   259.5 1951.02   273.7 1944.01   286.6 1943.39   305.4 1940.01
     331 1934.08   347.6 1928.61   387.9 1925.09   407.6    1919   443.6 1914.52
   515.1  1910.6  523.561906.438   535.7 1905.13  544.471906.436   557.5 1908.78
   595.7 1907.78   715.4 1909.23   823.7  1916.6   842.6 1916.77   847.3 1919.09
   863.8 1933.08   892.4 1942.32   903.9 1943.61   925.1 1941.89  1011.8 1926.75
#Mann= 11 ,-1 , 0
       0    .035       0     140     .06       0     310    .035       0
     330     .06       0  523.56    .045       0  544.47     .06       0
     570    .035       0     660     .06       0     690    .035       0
     810     .04       0     930      .1       0
#XS Ineff= 2 , 0
          514.79 1917.26  549.91         1917.26
Permanent Ineff=
       F       F
Bank Sta=523.56,544.47
XS Rating Curve= 0 ,0
Exp/Cntr=0.5,0.3

Type RM Length L Ch R = 1 ,12184   ,160.6,161.7,161.2
XS GIS Cut Line= 2
     2092541.191      184849.779     2091961.764      185679.206
#Sta/Elev= 30
       0 1999.66    50.2  2004.1    71.4 2002.47   132.7 1992.91   169.3 1981.07
   215.1 1962.27   227.1 1956.09   243.8 1952.13   255.2  1945.7     307 1937.33
   318.2 1939.34   331.2 1938.64   355.2 1932.96   371.2 1932.46   407.2 1927.56
   443.2 1913.05   511.3 1908.21  520.191906.007   527.3 1905.03  546.541906.006
   693.1 1908.19   795.4 1911.77   820.6 1916.27   843.4 1917.02   862.5 1928.21
   884.3 1932.68   899.5 1930.15   914.9 1924.59   933.7 1920.68  1011.8 1922.96
#Mann= 10 ,-1 , 0
       0    .035       0     120     .06       0     240    .035       0
     360     .06       0  520.19    .045       0  546.54     .06       0
     720    .035       0     760     .06       0     840     .04       0
     930      .1       0
#XS Ineff= 2 , 0
          516.84 1913.98  548.85         1913.85
Permanent Ineff=
       F       F
Bank Sta=520.19,546.54
XS Rating Curve= 0 ,0
Exp/Cntr=0.5,0.3

Type RM Length L Ch R = 1 ,12023   ,259.9,263.6,260
XS GIS Cut Line= 4
2092429.26769262184754.961194277 2092141.5075874185150.631338947
2092012.01554006185323.2874020762091863.33948569185625.435512552
#Sta/Elev= 30
       0 1991.93    56.6 1982.92   119.6 1969.39   141.9 1960.75   180.9 1957.22
   193.3  1958.2   242.3 1965.93   272.6 1972.27   281.3    1973   290.7 1972.02
   306.9 1968.24     322  1961.2   347.8 1946.84   392.1  1926.2   416.4 1910.43
   427.7  1906.2   481.3 1904.74   530.9 1906.15  564.031904.353   575.2 1903.22
  586.291904.352     592  1905.9   761.5 1908.78     820 1912.46   834.6 1916.55
     863 1916.27   885.3 1918.03   969.9 1930.66  1022.9 1944.94  1041.8 1951.66
#Mann= 11 ,-1 , 0
       0    .035       0     240     .06       0     380      .1       0
     480     .06       0  549.25    .035       0  564.03    .045       0
  586.29    .035       0  715.07     .07       0  725.07     .06       0
  835.07     .04       0  935.07      .1       0
#XS Ineff= 2 , 0
          446.99 1915.67  687.68         1914.13
Permanent Ineff=
       F       F
Bank Sta=564.03,586.29
XS Rating Curve= 0 ,0
Exp/Cntr(USF)=0,0
Exp/Cntr=0.3,0.1

Type RM Length L Ch R = 1 ,11759   ,371.6,370.4,369.1
XS GIS Cut Line= 3
     2092241.932      184563.194     2091978.335      185030.139
     2091714.932      185570.872
#Sta/Elev= 30
       0 2016.99    44.4 2007.67    56.9 2006.82    75.7 2008.98   149.1 2028.85
   222.7 2042.39   267.9 2053.15   285.2 2052.91   295.9 2049.21   313.1 2039.35
   339.5 2021.62   373.4 1995.78   403.5 1977.99   434.5 1955.79   452.5    1945
   482.8 1920.29  502.481901.394     509 1899.82  518.281901.396   538.1 1903.48
   681.4 1902.29   850.8 1907.99   859.6  1910.4   874.8 1918.33   903.2 1919.23
   940.5 1948.85   992.1 1972.64  1016.6 1978.34  1079.2 1981.69  1137.7 1992.83
#Mann= 9 ,-1 , 0
       0    .035       0      70      .1       0     220    .035       0
     270      .1       0  502.48    .045       0  518.28      .1       0
  666.21     .07       0  886.21     .04       0  996.21      .1       0
#XS Ineff= 2 , 0
                          676.23         1906.62
Permanent Ineff=
       F       F
Bank Sta=502.48,518.28
XS Rating Curve= 0 ,0
Exp/Cntr=0.3,0.1

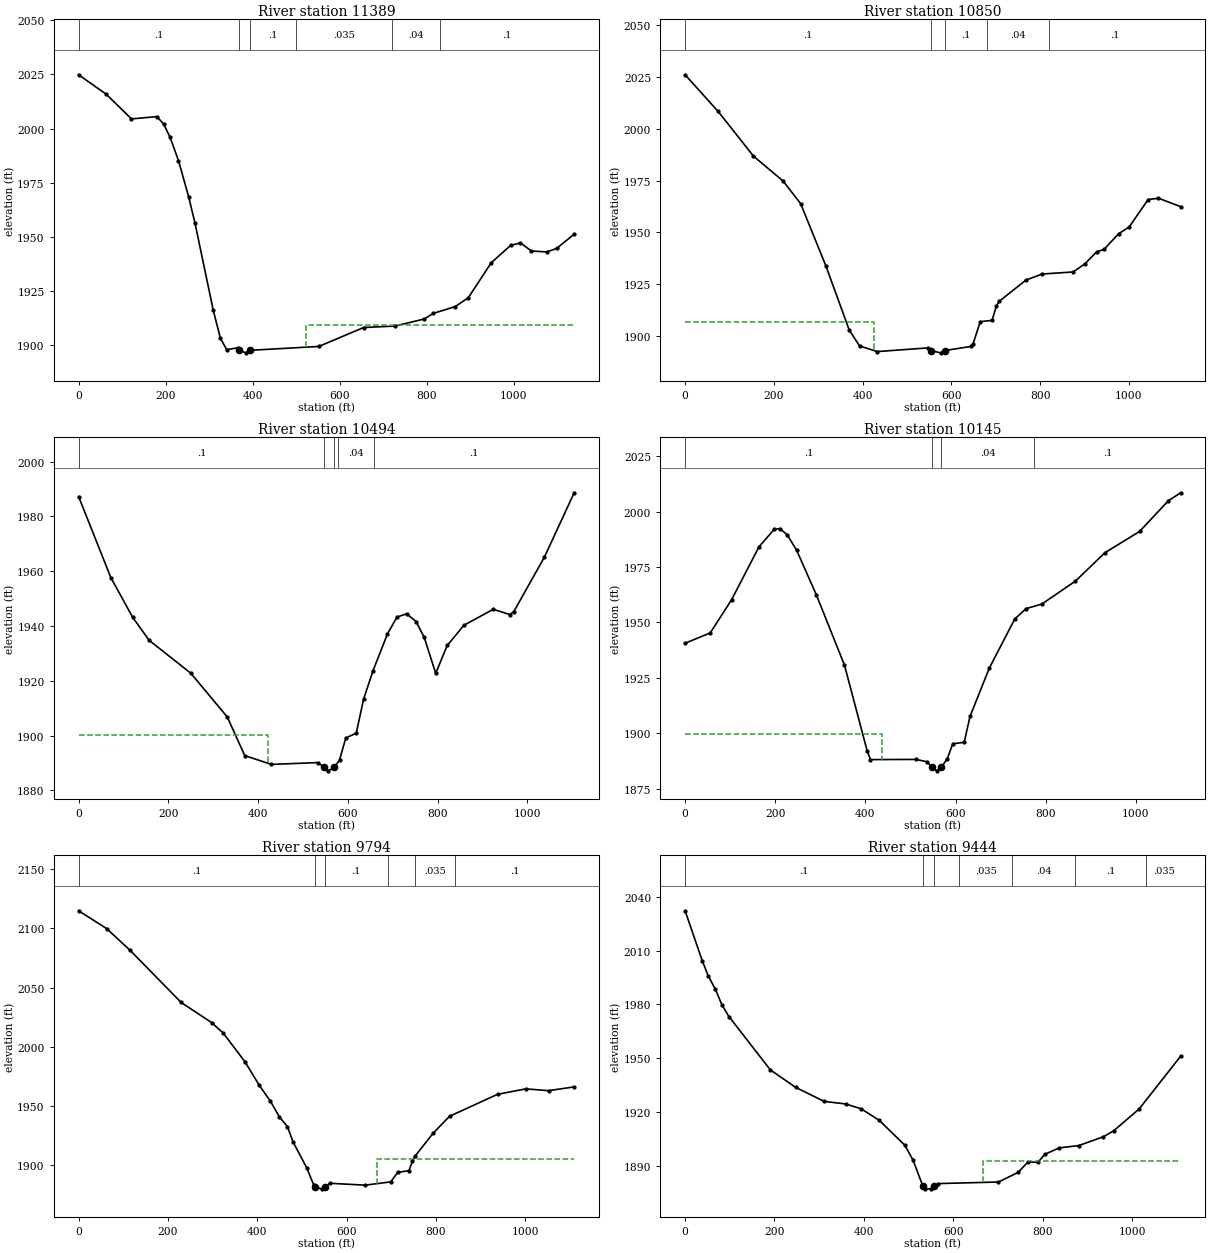
Type RM Length L Ch R = 1 ,11389   ,540.1,538.4,529.7
XS GIS Cut Line= 2
     2091827.891      184500.228     2091330.929      185524.534
#Sta/Elev= 30
       0 2024.83    63.1 2015.91   121.4 2004.46   179.8 2005.51     195 2002.18
   209.8 1996.12   229.4 1985.22   252.7 1968.55   267.3 1956.34   309.2 1916.19
   325.6 1903.22   340.2  1897.9   365.7 1898.75  369.031897.596     384 1896.43
  393.621897.594   551.7 1899.38   654.9 1908.13   726.7  1908.8   794.4 1912.08
   814.3 1914.61   865.3 1917.78   895.4 1921.93   948.1 1938.07   992.7 1946.05
  1015.1 1947.21  1040.3 1943.44  1075.8 1943.04  1098.4 1944.64  1138.5 1951.26
#Mann= 6 ,-1 , 0
       0      .1       0  369.03    .045       0  393.62      .1       0
     500    .035       0     720     .04       0     830      .1       0
#XS Ineff= 2 , 0
                          522.64         1909.32
Permanent Ineff=
       F       F
Bank Sta=369.03,393.62
XS Rating Curve= 0 ,0
Exp/Cntr=0.3,0.1

Type RM Length L Ch R = 1 ,10850   ,341.6,356,365.3
XS GIS Cut Line= 3
     2091225.965      184335.653     2091140.824      184899.535
     2091059.902      185439.782
#Sta/Elev= 30
       0 2026.07    74.5 2008.35   154.1 1986.76   220.5  1974.8   260.3 1963.85
   317.5 1933.58   369.8 1902.77     393 1895.09   432.9 1892.36   548.1 1894.15
  553.18 1892.86   575.5 1891.75  585.071892.861   645.2 1894.88   648.5 1895.95
   665.1 1906.81   691.6 1907.43   701.6 1914.59   708.2 1916.72   767.9 1926.89
   804.4 1929.82   874.1 1930.82   900.6 1934.71   927.2 1940.54   943.8 1941.72
   976.9  1949.3  1000.2 1952.47  1043.3 1965.79  1066.5 1966.44  1116.5 1962.37
#Mann= 5 ,-1 , 0
       0      .1       0  553.18    .045       0  585.07      .1       0
  680.27     .04       0  820.27      .1       0
#XS Ineff= 2 , 0
          426.36 1906.84
Permanent Ineff=
       F       F
Bank Sta=553.18,585.07
XS Rating Curve= 0 ,0
Exp/Cntr=0.3,0.1

Type RM Length L Ch R = 1 ,10494   ,343.4,349.8,348.4
XS GIS Cut Line= 3
      2091135.64      184299.403     2090838.685      184771.359
     2090489.206      185192.051
#Sta/Elev= 30
       0 1987.24    71.7 1957.72   120.5 1943.18     157 1934.81     250 1922.79
   331.4 1906.79   370.3 1892.72   429.8 1889.51     533 1890.17  547.331888.455
   555.9 1887.16  570.041888.454   581.6 1891.18   595.5 1899.18   618.8  1900.9
   635.1 1913.32   656.1 1923.67   688.3 1937.13   709.7  1943.3     731 1944.46
   752.3 1941.63   770.3 1935.84   795.9 1922.74   821.5 1932.91   858.8 1940.28
     924 1946.11   961.3  1944.2   969.9 1945.27  1038.1 1965.14  1104.5 1988.64
#Mann= 5 ,-1 , 0
       0      .1       0  547.33    .045       0  570.04      .1       0
  577.61     .04       0  657.61      .1       0
#XS Ineff= 2 , 0
          422.92 1900.13
Permanent Ineff=
       F       F
Bank Sta=547.33,570.04
XS Rating Curve= 0 ,0
Exp/Cntr=0.3,0.1

Type RM Length L Ch R = 1 ,10145   ,354.4,351.1,354.7
XS GIS Cut Line= 3
     2090980.959      184177.646      2090575.63      184556.672
     2090227.024      184974.924
#Sta/Elev= 30
       0  1940.6    55.8 1945.25   103.3 1960.27   163.9 1984.09   197.6 1991.96
   210.3 1992.31   226.6 1989.49   247.5 1982.51   291.2 1962.43   353.6 1930.72
   404.2 1891.83   411.3 1888.11   512.1 1888.19   537.6 1887.11  547.081884.594
   558.5 1883.04  568.181884.592   581.8 1888.53   593.8 1895.27   619.1 1895.89
   632.2 1907.62   674.9 1929.36   731.4 1951.54   756.5 1956.21   791.5 1958.27
     866 1968.62   931.2 1981.39  1008.2    1991  1072.1 2004.84  1099.4 2008.46
#Mann= 4 ,-1 , 0
       0      .1       0  547.08    .045       0  568.18     .04       0
  774.93      .1       0
#XS Ineff= 2 , 0
          436.68 1899.47
Permanent Ineff=
       F       F
Bank Sta=547.08,568.18
XS Rating Curve= 0 ,0
Exp/Cntr=0.3,0.1

Type RM Length L Ch R = 1 ,9794    ,348.1,350,345.4
XS GIS Cut Line= 3
     2090719.912      183827.361     2090398.651      184264.288
     2089958.873      184623.063
#Sta/Elev= 30
       0 2114.79    62.9 2099.72   114.5  2081.7   229.5 2037.47   297.6 2020.51
   323.6 2011.75   372.7 1987.29   404.7 1967.44   429.2 1954.35   449.5 1940.96
   467.6 1932.71   480.6 1919.44   510.6 1898.12   526.9 1883.11  530.13 1881.43
     544 1880.15  551.461881.432   562.6 1884.85   641.9 1883.26   699.1 1886.04
   714.7 1894.05   739.9 1895.47   747.7 1903.57   753.8 1907.91   793.5 1926.85
   830.8 1941.39   938.2 1959.91  1001.7 1964.52  1052.5 1962.99  1109.9 1966.19
#Mann= 6 ,-1 , 0
       0      .1       0  530.13    .045       0  551.46      .1       0
  692.32     .04       0  752.32    .035       0  842.32      .1       0
#XS Ineff= 2 , 0
                          668.77         1904.97
Permanent Ineff=
       F       F
Bank Sta=530.13,551.46
XS Rating Curve= 0 ,0
Exp/Cntr=0.3,0.1

Type RM Length L Ch R = 1 ,9444    ,349.6,350,354
XS GIS Cut Line= 3
     2090508.559      183595.426     2090163.104      184013.566
     2089790.254      184440.049
#Sta/Elev= 30
       0 2032.17    38.6 2004.18    51.5 1996.09    67.8 1988.39    82.4 1979.77
    98.2 1973.22   190.6 1943.59   247.2 1933.83     311    1926   359.1 1924.56
     394 1921.87   434.4 1915.44   491.9 1901.54     510 1893.29   532.41878.612
   536.2 1877.33   549.5 1877.28  557.931878.612   565.9  1880.2   701.3 1881.09
   745.5 1886.47   767.4 1892.28   789.6 1892.05   805.1  1896.5   837.1 1900.09
   880.7 1901.37   936.1  1906.3   959.4 1909.67  1015.8  1921.7  1108.9 1951.16
#Mann= 7 ,-1 , 0
       0      .1       0   532.4    .045       0  557.93      .1       0
  612.38    .035       0  732.38     .04       0  872.38      .1       0
 1032.38    .035       0
#XS Ineff= 2 , 0
                          667.05         1892.98
Permanent Ineff=
       F       F
Bank Sta=532.4,557.93
XS Rating Curve= 0 ,0
Exp/Cntr=0.3,0.1

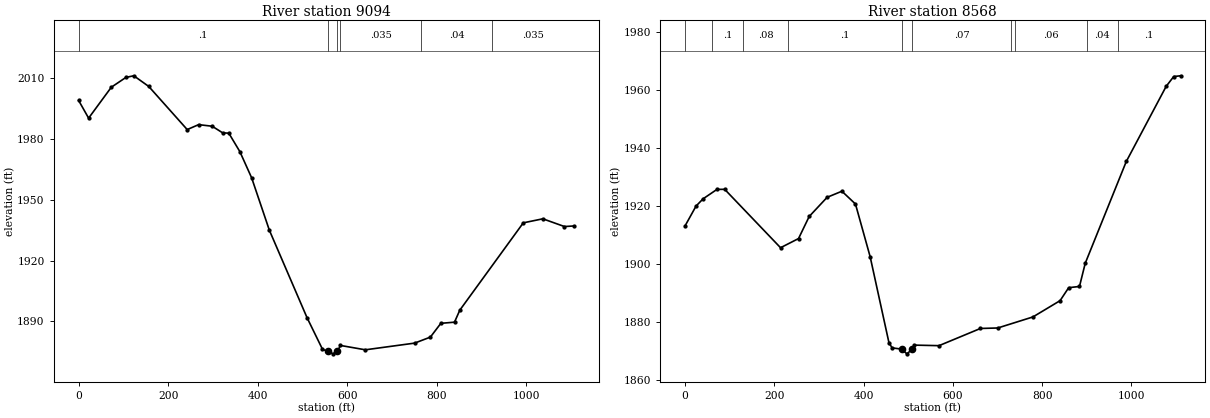
Type RM Length L Ch R = 1 ,9094    ,520.6,525.2,525.2
XS GIS Cut Line= 3
     2090237.309      183421.522     2089862.269      183843.546
     2089428.093      184169.178
#Sta/Elev= 30
       0 1999.06    22.3 1990.33      73 2005.58   105.7 2010.44   123.3 2011.24
   156.7 2005.97   242.6 1984.69   268.2 1987.12   298.4 1986.34   321.7 1983.09
   335.6  1982.9   360.3 1973.79   386.6 1960.87   426.2    1935   510.3 1891.88
   544.9 1876.24  556.45 1875.23   568.7 1873.99  578.16 1875.23   585.1 1878.13
   640.7 1875.98   750.8 1879.28     786 1882.25   809.4 1889.05   839.9 1889.62
   851.7 1895.53   993.6 1938.65  1037.3 1940.64  1085.5 1936.83  1107.3 1937.11
#Mann= 6 ,-1 , 0
       0      .1       0  556.45    .045       0  578.16      .1       0
  584.59    .035       0  764.59     .04       0  924.59    .035       0
Bank Sta=556.45,578.16
XS Rating Curve= 0 ,0
Exp/Cntr=0.3,0.1

Type RM Length L Ch R = 1 ,8568    ,117.1,115.6,112.7
XS GIS Cut Line= 2
     2089944.211      183141.721     2089041.433      183788.423
#Sta/Elev= 30
       0 1913.32    24.6 1920.14    40.3 1922.63    71.4 1925.88    88.7 1925.91
   213.9 1905.76   254.2 1908.92   278.1 1916.54   318.3 1923.15   351.4 1925.25
   381.8 1920.83   414.7 1902.66     457 1872.89   464.1 1871.21  485.461870.788
     497 1869.16  509.481870.788   513.4 1872.17     569 1871.98   661.8 1877.91
   700.7 1878.08   779.5 1881.89   840.3  1887.5   859.6 1891.98   883.8  1892.4
   896.7  1900.4   988.7 1935.51  1078.1 1961.43    1095 1964.81  1110.5 1965.07
#Mann= 10 ,-1 , 0
       0     .06       0      60      .1       0     130     .08       0
     230      .1       0  485.46    .045       0  509.48     .07       0
     730    .035       0     740     .06       0     900     .04       0
     970      .1       0
Bank Sta=485.46,509.48
XS Rating Curve= 0 ,0
Exp/Cntr=0.3,0.1