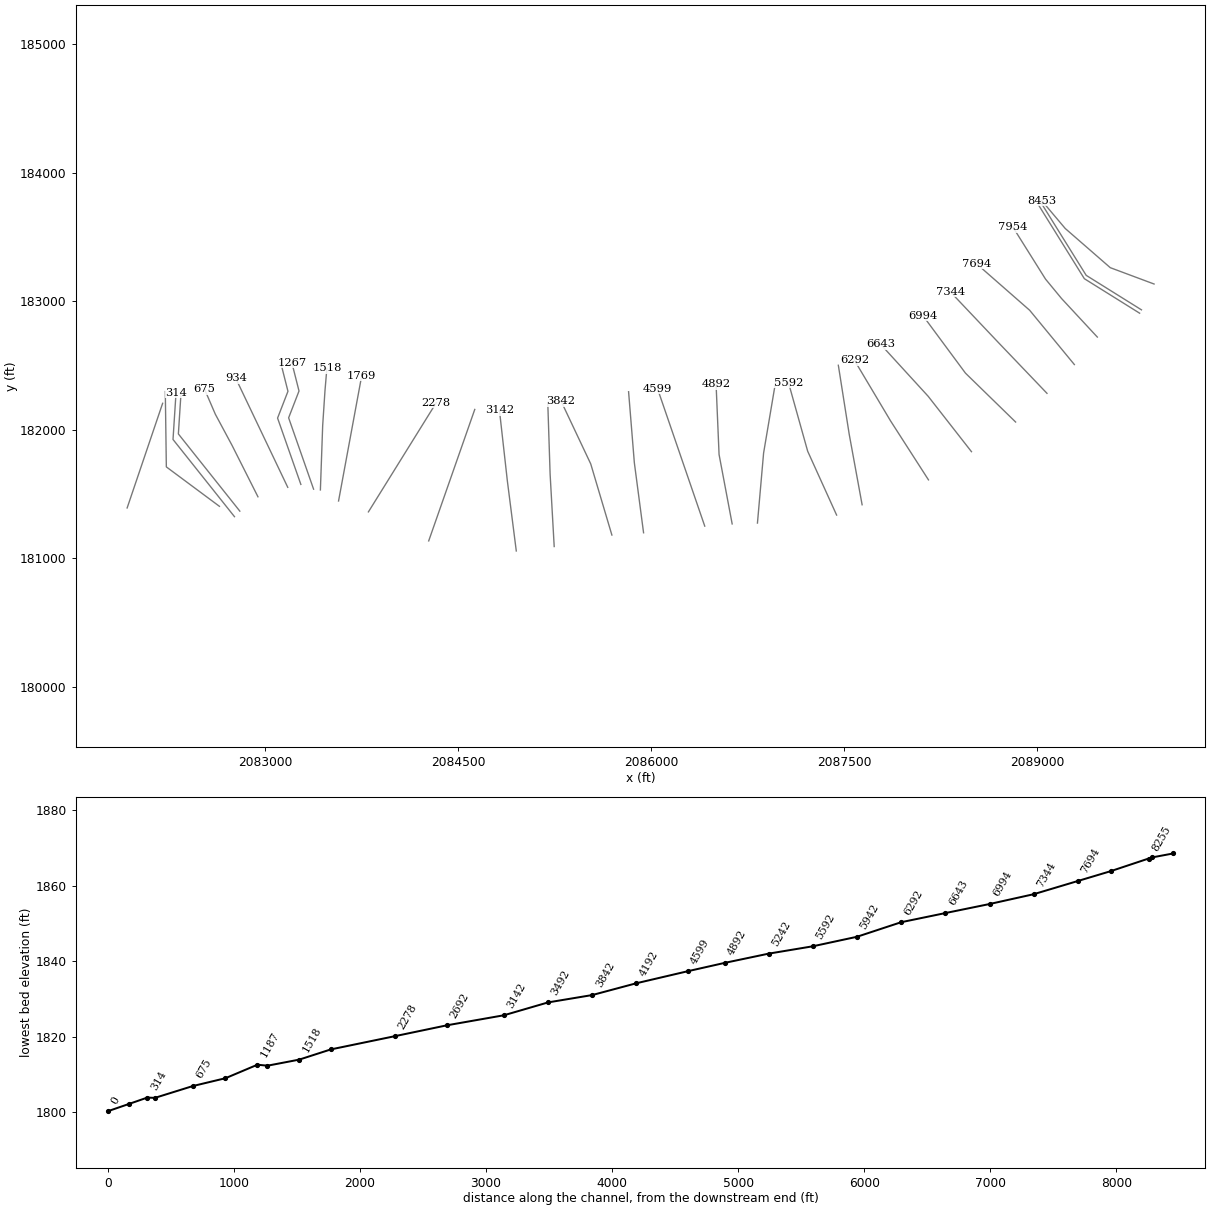
HEC-RAS study DRPLKCR.prj: DRPLKCR

--- DRPLKCR.g01 (geometry) --- (continued)

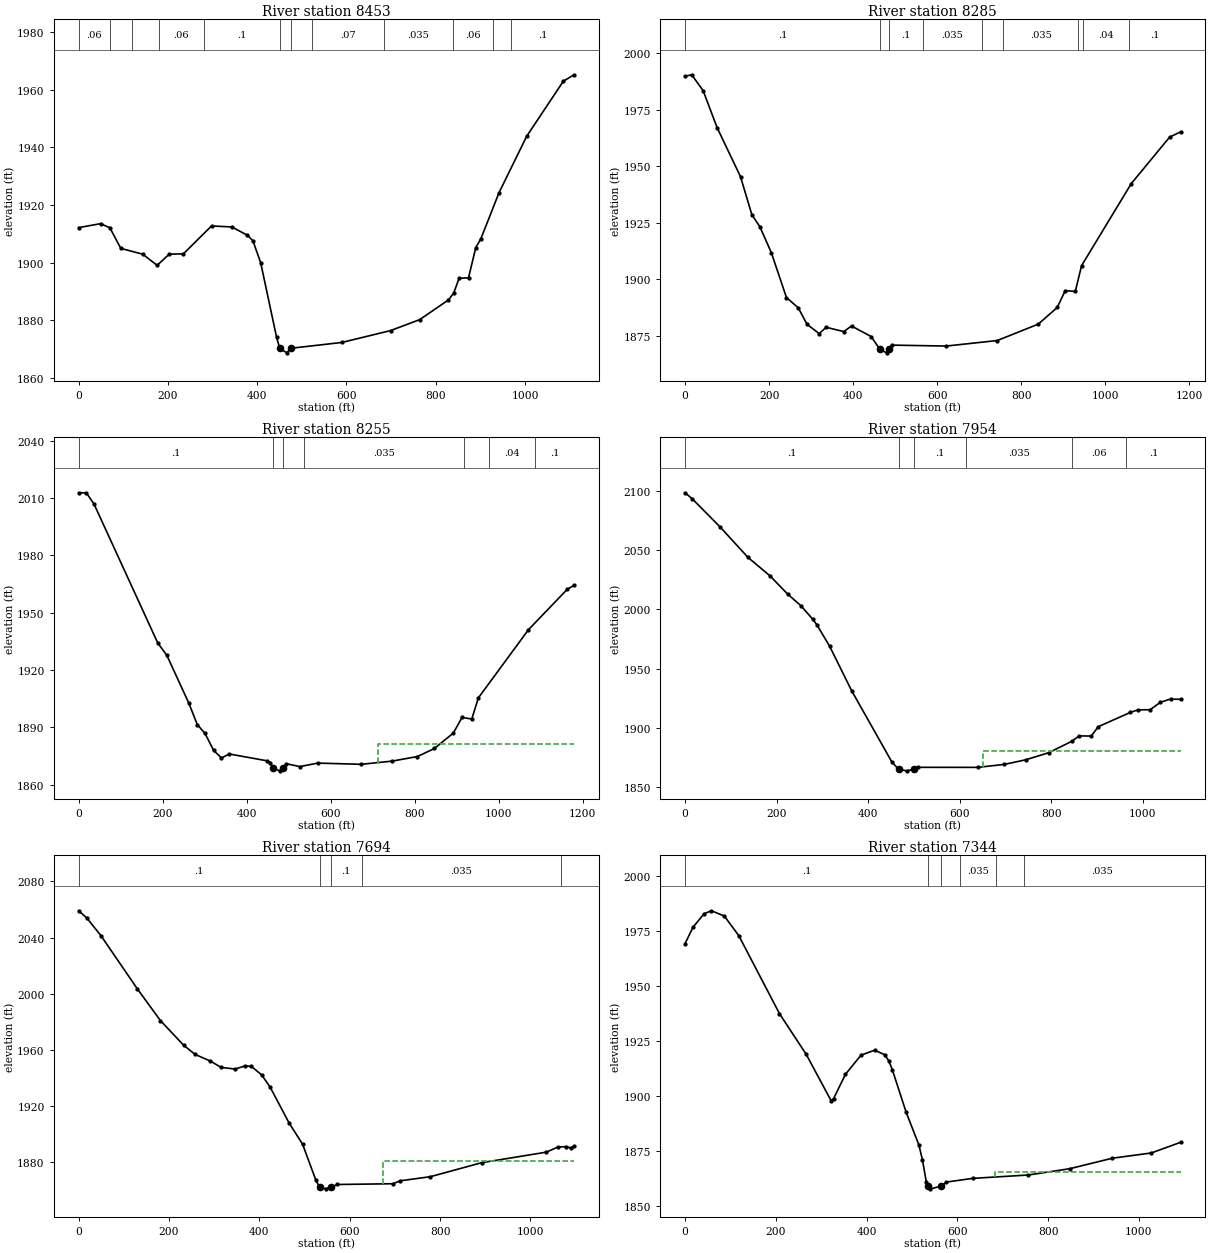
Type RM Length L Ch R = 1 ,8453    ,163.4,167.4,170.5
XS GIS Cut Line= 4
2089911.36677199183133.9126015662089570.85064748183261.006648036
2089220.74251947183565.5527593882089038.49445283183781.372838299
#Sta/Elev= 30
       0 1912.12      49 1913.51      70 1912.07    94.5  1904.9   143.5  1902.9
   175.9 1899.02     203 1902.91   234.6    1903   297.7 1912.72   343.1 1912.36
   377.9 1909.49   390.4 1907.56   407.8 1899.91   443.5 1873.93  450.451870.166
   466.2 1868.58  475.221870.167   589.5 1872.19   698.8 1876.32   763.9 1880.12
   828.3 1886.97   840.1 1889.36   852.3 1894.53   873.3 1894.66   889.6 1905.19
   901.1 1908.29   941.8 1924.33  1003.6 1943.89  1085.9 1963.09    1110 1965.29
#Mann= 12 ,-1 , 0
       0     .06       0      70      .1       0     120     .08       0
     180     .06       0     280      .1       0  450.45    .045       0
  475.22      .1       0  523.46     .07       0  683.46    .035       0
  837.49     .06       0  927.49     .04       0  967.49      .1       0
Bank Sta=450.45,475.22
XS Rating Curve= 0 ,0
Exp/Cntr(USF)=0,0
Exp/Cntr=0.5,0.3

Type RM Length L Ch R = 1 ,8285    ,29.8,30.3,29.8
XS GIS Cut Line= 3
     2089813.326      182933.113     2089383.639      183201.342
      2089028.17      183772.956
#Sta/Elev= 30
       0 1989.85    15.8 1990.49      43 1983.45    76.3 1967.07   131.9 1945.43
   158.9 1928.65   178.3  1923.2   205.4 1911.77   241.3 1891.98   269.2 1887.47
   290.4 1880.14   319.2 1876.03   335.9 1878.83   377.6 1876.93   396.2  1879.4
     443 1874.73  463.711869.053     480 1867.53  484.491869.053   491.6 1870.95
   621.6 1870.53   743.1 1872.97   840.8 1880.23   886.1 1887.63   904.9 1895.05
   928.9 1894.67   943.9  1906.1  1062.3  1942.4  1153.4  1962.9  1179.7 1965.26
#Mann= 9 ,-1 , 0
       0      .1       0  463.71    .045       0  484.49      .1       0
  566.54    .035       0  706.54     .07       0  756.54    .035       0
  936.54     .06       0  946.54     .04       0 1056.54      .1       0
#XS Ineff= 2 , 0
          454.82 1870.85  491.24         1870.85
Permanent Ineff=
       F       F
Bank Sta=463.71,484.49
XS Rating Curve= 0 ,0
Exp/Cntr=0.5,0.3

Type RM Length L Ch R = 1 ,8255    ,298.2,300.8,291.1
XS GIS Cut Line= 3
     2089799.003      182907.071     2089369.316        183175.3
     2089013.847      183746.915
#Sta/Elev= 30
       0 2012.69    18.3 2012.65    36.5 2006.86   188.5 1934.05     210 1927.63
     262  1902.8   282.5  1891.4   300.6 1886.87   321.5 1877.87   340.1 1873.93
   358.6 1876.03   447.6  1872.5   456.3 1871.54  462.881868.622   478.5 1867.21
  485.481868.622     494 1870.99   526.4 1869.42   568.9 1871.26   673.2 1870.63
   746.6 1872.31   806.4 1874.69     847  1878.9   892.2 1887.03   912.7 1895.16
   935.9 1894.32   951.7 1905.41  1070.8 1941.02  1163.8 1962.32  1179.7 1964.25
#Mann= 7 ,-1 , 0
       0      .1       0  462.88    .045       0  485.48      .1       0
  536.54    .035       0  916.54     .06       0  976.54     .04       0
 1086.54      .1       0
#XS Ineff= 2 , 0
          457.38 1870.48  713.47         1881.19
Permanent Ineff=
       F       F
Bank Sta=462.88,485.48
XS Rating Curve= 0 ,0
Exp/Cntr=0.5,0.3

Type RM Length L Ch R = 1 ,7954    ,258.8,260.8,262.5
XS GIS Cut Line= 4
2089470.13461066182721.4564507582089191.96650895183021.206560357
2089067.27046336183172.2806155942088813.08237042183577.542763772
#Sta/Elev= 30
       0 2098.16    15.5 2093.13    76.5 2069.36   137.4 2043.74   185.6 2028.13
   224.2 2012.78   253.2 2002.98   278.5 1991.81   287.8 1987.06   315.9 1968.87
   364.1 1931.32   451.9 1871.38   466.81865.122   484.7 1863.86  499.631865.121
   508.7 1866.81     640 1866.79     698  1869.3   744.5 1873.16   794.4 1879.08
   845.1 1888.72   861.3  1893.3   887.7 1893.17   903.2 1901.06   973.4 1913.13
   989.8 1915.22  1016.6 1915.37  1038.8 1921.58  1061.2 1924.39  1083.2  1924.1
#Mann= 6 ,-1 , 0
       0      .1       0   466.8    .045       0  499.63      .1       0
  614.82    .035       0  844.82     .06       0  964.82      .1       0
#XS Ineff= 2 , 0
                          651.58         1880.91
Permanent Ineff=
       F       F
Bank Sta=466.8,499.63
XS Rating Curve= 0 ,0
Exp/Cntr(USF)=0,0
Exp/Cntr=0.3,0.1

Type RM Length L Ch R = 1 ,7694    ,348,350,347.5
XS GIS Cut Line= 3
     2089291.561      182507.775     2088944.149      182929.757
     2088530.224      183292.229
#Sta/Elev= 30
       0 2059.14    17.8 2054.11    49.3 2041.48   129.7 2003.69     181    1981
   232.6 1963.39   257.9 1956.88   291.5 1952.22   315.2 1947.67   346.8  1946.5
     368 1948.77   382.3 1948.38   404.8 1942.43   423.4 1933.91   465.7 1908.18
   495.7 1892.99   525.2 1867.31  533.39 1862.45   546.6 1861.25  557.971862.449
   572.5 1864.34   695.6 1864.88     712 1866.98   778.5 1869.89   891.8 1879.84
  1035.2 1887.36  1060.8    1891  1079.3  1891.3  1089.3 1890.34  1096.8 1891.75
#Mann= 5 ,-1 , 0
       0      .1       0  533.39    .045       0  557.97      .1       0
  626.59    .035       0 1066.59     .04       0
#XS Ineff= 2 , 0
                          673.93         1880.91
Permanent Ineff=
       F       F
Bank Sta=533.39,557.97
XS Rating Curve= 0 ,0
Exp/Cntr=0.3,0.1

Type RM Length L Ch R = 1 ,7344    ,348.9,349.6,346.7
XS GIS Cut Line= 3
     2089078.742      182283.934     2088701.315      182678.489
     2088325.807      183074.857
#Sta/Elev= 30
       0 1969.36    17.4 1976.78    41.8 1982.92      58 1984.27    86.4 1981.88
   118.4 1972.93     208 1937.46   266.9 1918.95   321.5 1897.94   327.2 1898.79
   353.3 1909.84   387.6 1918.57   417.7 1920.83   439.6 1918.77   448.7 1916.06
   456.6    1912   487.3 1892.49   515.2 1877.73     523 1870.98   531.4 1861.04
  534.981858.974   540.7 1857.75  564.881858.975   575.5 1860.82   633.5 1862.51
   756.5 1864.05   847.3  1866.9   941.7 1871.69  1027.6 1874.08    1092 1878.93
#Mann= 6 ,-1 , 0
       0      .1       0  534.98    .045       0  564.88      .1       0
  606.01    .035       0  686.01      .1       0  746.01    .035       0
#XS Ineff= 2 , 0
                          682.55         1865.54
Permanent Ineff=
       F       F
Bank Sta=534.98,564.88
XS Rating Curve= 0 ,0
Exp/Cntr=0.3,0.1

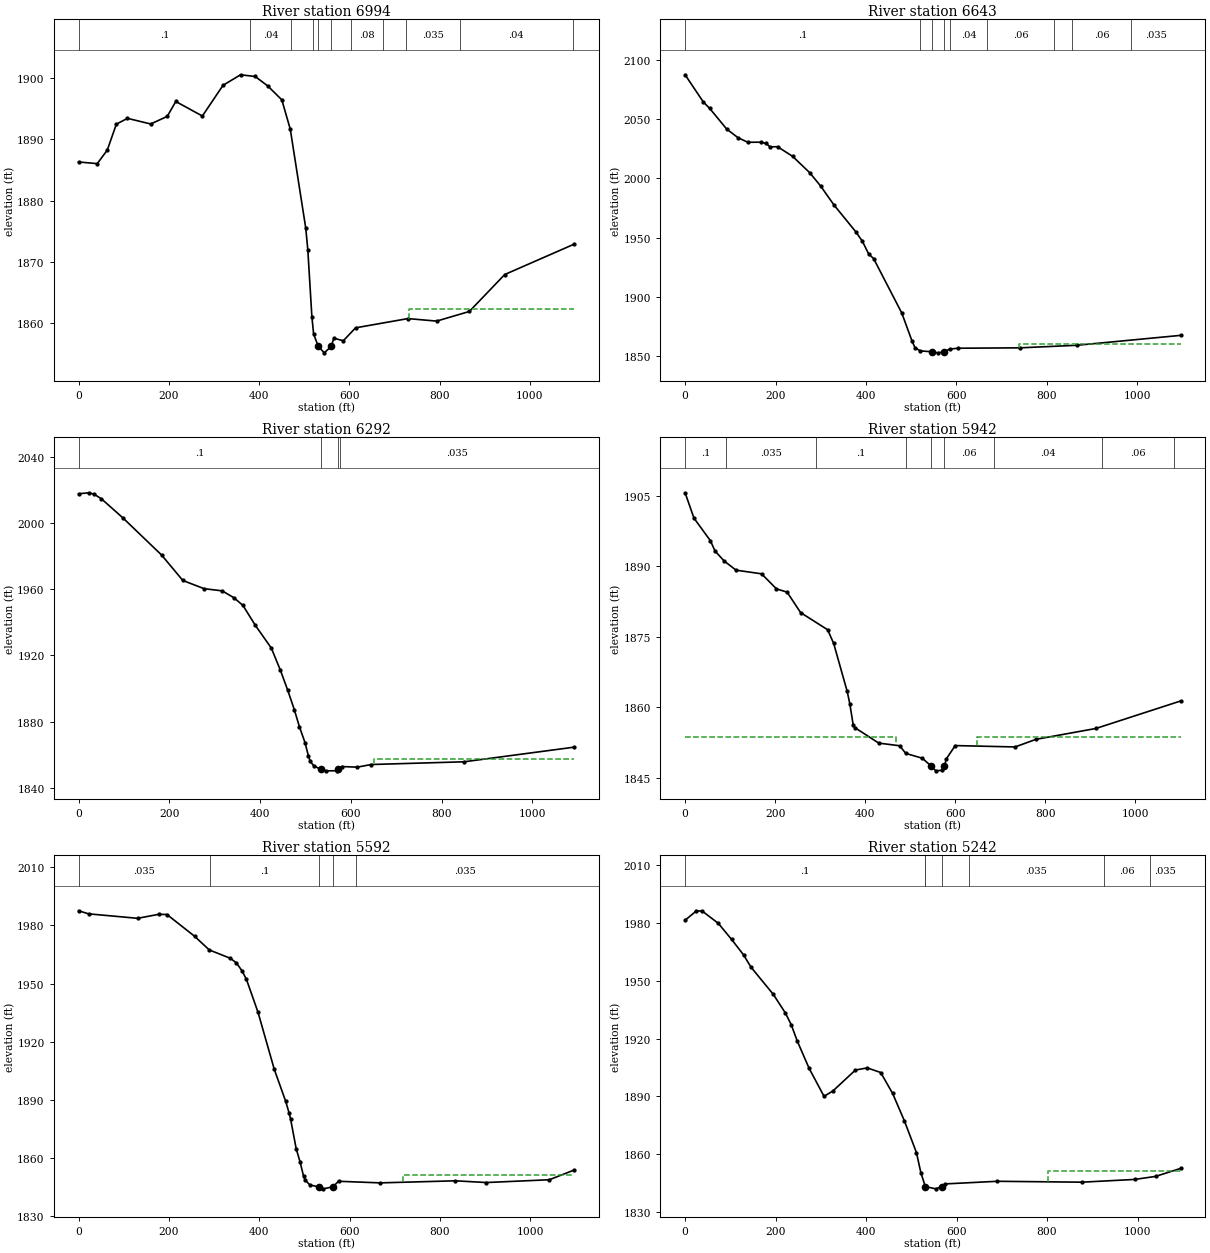
Type RM Length L Ch R = 1 ,6994    ,350.9,350.4,351.3
XS GIS Cut Line= 3
     2088834.842      182060.927     2088444.799      182441.097
     2088115.583      182886.106
#Sta/Elev= 30
       0  1886.3    41.3 1886.03    63.5 1888.24    83.6 1892.47   108.2 1893.42
   159.7  1892.5   196.4 1893.74   215.3 1896.17   274.2  1893.8     320 1898.81
   358.8 1900.53   391.3 1900.25   419.1 1898.71   450.3 1896.44   469.1 1891.63
   503.3 1875.52   507.9 1871.98     517 1860.97   520.8 1858.21  531.081856.208
   544.4 1855.15  559.931856.209   565.5 1857.54   586.6 1857.12   613.7 1859.23
   729.7 1860.74   793.3 1860.33   865.8  1861.9   944.3 1867.93  1098.2 1872.89
#Mann= 11 ,-1 , 0
       0      .1       0     380     .04       0     470      .1       0
     520     .06       0  531.08    .045       0  559.93     .06       0
  604.67     .08       0  674.67     .06       0  724.67    .035       0
  844.67     .04       0 1094.67    .035       0
#XS Ineff= 2 , 0
                          733.13         1862.26
Permanent Ineff=
       F       F
Bank Sta=531.08,559.93
XS Rating Curve= 0 ,0
Exp/Cntr=0.3,0.1

Type RM Length L Ch R = 1 ,6643    ,354.6,351.1,346.2
XS GIS Cut Line= 3
      2088491.58      181830.324     2088154.975      182261.016
     2087784.241      182666.223
#Sta/Elev= 30
       0 2087.57    40.5  2064.5    54.5  2059.1      92 2041.71   116.9 2034.48
   138.6 2030.57   166.9 2030.64   179.4 2029.61   187.7  2026.7   204.4 2026.84
   237.7 2018.69   275.2 2005.02   299.6 1993.69   329.3 1977.57     377  1955.2
   391.8 1947.12   406.1 1936.15   416.8  1932.4   479.2 1886.32     502  1862.5
   508.3 1857.25   519.6 1854.41   545.3 1853.67   559.1 1852.75   573.2 1853.62
   584.8 1855.91   603.4 1856.65   740.4 1856.98   865.6 1859.12  1095.8  1867.5
#Mann= 9 ,-1 , 0
       0      .1       0     520     .06       0   545.3    .045       0
   573.2     .06       0  586.62     .04       0  666.62     .06       0
  816.62    .035       0  856.62     .06       0  986.62    .035       0
#XS Ineff= 2 , 0
                          737.67         1860.58
Permanent Ineff=
       F       F
Bank Sta=545.3,573.2
XS Rating Curve= 0 ,0
Exp/Cntr=0.3,0.1

Type RM Length L Ch R = 1 ,6292    ,357.9,350,336.9
XS GIS Cut Line= 3
     2088157.264      181611.154     2087862.046      182070.379
     2087582.449      182539.809
#Sta/Elev= 30
       0 2017.64      23 2018.24    34.7 2017.29    50.3 2014.58    97.1  2003.2
   182.9 1980.64   229.7 1965.27   276.5 1960.34   316.3 1959.01   342.4 1954.84
   362.3 1950.17   389.6 1938.14   424.7 1924.48   444.9 1910.97   461.1 1898.86
   475.4 1887.28   486.6 1877.02   499.1 1867.27   506.6 1859.19   510.5 1856.02
   518.3 1853.37  534.27 1851.13   545.6 1850.32   568.5 1850.36   572.3 1851.13
     580 1852.91   614.3 1852.55   644.9 1854.14   849.5 1855.78  1092.3 1864.62
#Mann= 4 ,-1 , 0
       0      .1       0  534.27    .045       0   572.3      .1       0
  575.93    .035       0
#XS Ineff= 2 , 0
                          650.51         1857.64
Permanent Ineff=
       F       F
Bank Sta=534.27,572.3
XS Rating Curve= 0 ,0
Exp/Cntr=0.3,0.1

Type RM Length L Ch R = 1 ,5942    ,345,350,353.3
XS GIS Cut Line= 3
     2087641.376      181417.554     2087541.174      181964.738
     2087456.506      182502.122
#Sta/Elev= 30
       0 1905.68    19.7 1900.28    56.2 1895.47    66.4 1893.29    86.4 1891.18
   113.1  1889.2   169.8 1888.42   202.9 1885.21   226.5 1884.52   256.5 1880.16
   316.5 1876.51   329.9 1873.59   359.9 1863.38   365.8 1860.72   373.2 1856.25
   376.5 1855.69   429.9 1852.37   476.4  1851.8     490 1850.17   526.6 1849.15
  546.741847.452   556.7 1846.46   569.9 1846.58  575.891847.452   579.9 1848.99
   599.8 1851.84   732.7 1851.55   779.1 1853.17     912 1855.48  1100.3 1861.34
#Mann= 9 ,-1 , 0
       0      .1       0      90    .035       0     290      .1       0
     490     .06       0  546.74    .045       0  575.89     .06       0
  686.28     .04       0  926.28     .06       0 1086.28     .04       0
#XS Ineff= 2 , 0
          467.85  1853.6  648.44          1853.6
Permanent Ineff=
       F       F
Bank Sta=546.74,575.89
XS Rating Curve= 0 ,0
Exp/Cntr=0.3,0.1

Type RM Length L Ch R = 1 ,5592    ,361.4,350,336.8
XS GIS Cut Line= 3
     2087442.975      181337.519     2087218.047      181833.946
     2087069.151      182365.859
#Sta/Elev= 30
       0 1987.57    22.1 1985.98   130.7 1983.68   177.5 1985.75   195.6 1985.64
   256.8 1974.41   289.2 1967.36     336 1963.02   349.3 1960.68   361.7  1956.6
   371.6 1952.15   397.3 1935.13   433.3 1905.64   458.5 1889.18   465.8 1883.33
   469.3 1880.12   481.8 1864.65   490.6 1857.68   498.1 1850.47   501.7 1848.38
   512.5  1845.9  532.531844.948   541.3 1843.94  562.871844.947   575.6 1847.85
   667.6 1847.02   834.5 1848.09   902.7  1847.2  1042.3 1848.63  1097.4 1853.66
#Mann= 5 ,-1 , 0
       0    .035       0     290      .1       0  532.53    .045       0
  562.87      .1       0  615.01    .035       0
#XS Ineff= 2 , 0
                          719.16         1850.98
Permanent Ineff=
       F       F
Bank Sta=532.53,562.87
XS Rating Curve= 0 ,0
Exp/Cntr=0.3,0.1

Type RM Length L Ch R = 1 ,5242    ,343,350,355.7
XS GIS Cut Line= 3
     2086827.543      181275.328     2086875.351       181819.83
     2086966.692      182360.873
#Sta/Elev= 30
       0 1981.47    23.9 1986.12      37 1986.38    73.3 1979.88   102.9 1971.47
   129.3 1963.45   145.7 1957.09   195.1 1942.94   221.5 1933.36   234.6 1927.23
   247.8  1918.8   274.2 1904.53   307.1 1890.02   326.9 1892.85   376.5 1903.68
   402.6 1904.79   432.3  1902.4   458.6 1891.57   484.8 1877.24   511.3 1860.84
   521.2 1850.31  530.941843.175   554.1 1841.99  567.441843.176   574.1 1844.54
   690.2 1845.91   876.9 1845.45   993.4 1846.87    1040 1848.45  1095.3  1852.6
#Mann= 7 ,-1 , 0
       0      .1       0     530     .07       0  530.94    .045       0
  567.44     .07       0   626.6    .035       0   926.6     .06       0
  1026.6    .035       0
#XS Ineff= 2 , 0
                          801.24         1851.08
Permanent Ineff=
       F       F
Bank Sta=530.94,567.44
XS Rating Curve= 0 ,0
Exp/Cntr=0.3,0.1

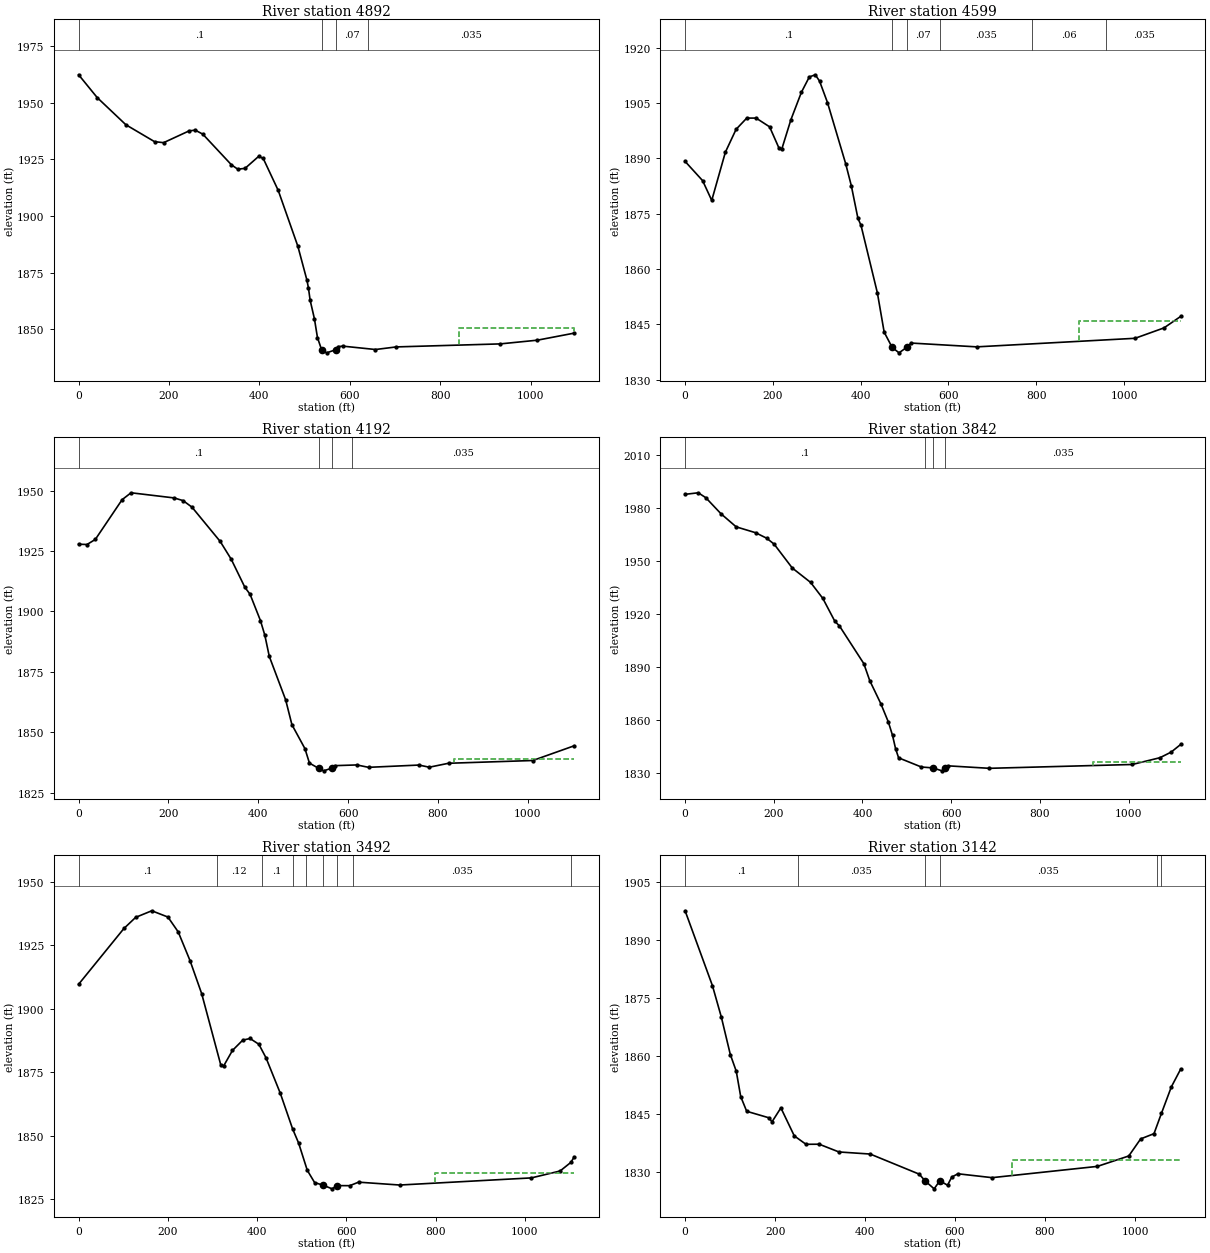
Type RM Length L Ch R = 1 ,4892    ,290,293.8,301.2
XS GIS Cut Line= 3
     2086630.944      181268.588     2086529.084      181808.439
     2086505.843       182355.14
#Sta/Elev= 30
       0 1962.43    41.1 1952.35   104.5 1940.35   167.9 1932.88     188 1932.42
   244.7 1937.65   258.1 1937.95   274.8 1936.18   338.2 1922.62   352.2  1920.7
   368.3 1921.07   398.3 1926.35   408.4 1925.49   441.7 1911.31   485.1 1886.67
   505.1 1871.73   508.5 1868.29   512.3 1862.79   521.8 1854.58   528.5 1846.29
  537.661840.906   548.8 1839.53  568.941840.905   574.8  1842.3   584.7 1842.49
   656.9    1841   703.1 1842.15   932.8 1843.48    1015 1845.12  1096.6 1848.24
#Mann= 4 ,-1 , 0
       0      .1       0  537.66    .045       0  568.94     .07       0
  639.38    .035       0
#XS Ineff= 2 , 0
                          840.69         1850.38
Permanent Ineff=
       F       F
Bank Sta=537.66,568.94
XS Rating Curve= 0 ,0
Exp/Cntr=0.3,0.1

Type RM Length L Ch R = 1 ,4599    ,409.1,406.2,395.8
XS GIS Cut Line= 2
     2086417.735       181251.53     2086050.982      182319.239
#Sta/Elev= 30
       0 1889.17    39.9 1883.96    60.7 1878.61    91.8 1891.68   116.2 1897.87
   140.5 1900.91   161.7 1900.91   192.5 1898.54   213.3 1892.93   220.3 1892.52
   241.1 1900.49     265 1907.91     283 1912.06   296.6 1912.64   306.3 1910.93
   324.4 1905.11   365.7  1888.6   378.6 1882.62   393.7 1873.76   400.7 1871.86
     438 1853.58   453.5 1842.92  471.651838.792   487.4 1837.31  504.721838.792
   515.1 1839.96   664.3 1838.93  1025.1 1841.25    1091 1844.07  1128.9 1847.17
#Mann= 6 ,-1 , 0
       0      .1       0  471.65    .045       0  504.72     .07       0
     580    .035       0     790     .06       0     960    .035       0
#XS Ineff= 2 , 0
                          897.42         1845.83
Permanent Ineff=
       F       F
Bank Sta=471.65,504.72
XS Rating Curve= 0 ,0
Exp/Cntr=0.3,0.1

Type RM Length L Ch R = 1 ,4192    ,343.3,350,355.6
XS GIS Cut Line= 3
     2085942.071      181199.839     2085870.407      181743.906
     2085825.586      182296.429
#Sta/Elev= 30
       0  1927.8    18.7 1927.68    37.2 1929.79    96.8 1946.21   116.7 1949.06
   212.6 1946.93   232.5 1945.82   252.3 1943.12   315.2 1928.93   339.7 1921.58
   370.1 1909.98   381.6 1907.11   404.7 1896.25   414.5 1890.18   424.4 1881.44
   460.8  1863.5   474.8  1853.2   503.8 1843.29   513.8 1837.33     534 1835.19
   545.5 1834.13   563.6 1835.25   569.9 1836.27   619.3 1836.57   645.3 1835.58
   757.5 1836.52   780.6 1835.63   823.4 1837.26    1011  1838.4  1103.1 1844.48
#Mann= 4 ,-1 , 0
       0      .1       0     534    .045       0   563.6      .1       0
  608.77    .035       0
#XS Ineff= 2 , 0
                           836.3         1838.95
Permanent Ineff=
       F       F
Bank Sta=534,563.6
XS Rating Curve= 0 ,0
Exp/Cntr=0.3,0.1

Type RM Length L Ch R = 1 ,3842    ,353.8,350,339.8
XS GIS Cut Line= 3
     2085695.746      181182.068     2085531.351       181735.11
     2085300.539      182223.889
#Sta/Elev= 30
       0 1987.64    29.7 1988.52    46.8 1985.71      81 1976.61   115.2 1969.22
   158.9  1965.9     184 1962.78   200.8 1959.42   241.7  1945.9     283 1937.75
   310.6 1928.68   337.7 1915.72     348 1913.12     403 1891.75   416.4 1882.11
   441.4 1869.04   458.4 1858.65   467.8 1851.06   474.6  1843.6   481.5 1838.37
   532.8 1833.17   558.6 1832.67   579.5    1831   586.9 1832.51   591.9 1833.85
   686.2 1832.43  1008.4  1834.6  1070.8 1838.43  1096.2 1841.63  1117.5 1845.93
#Mann= 4 ,-1 , 0
       0      .1       0     540    .035       0   558.6    .045       0
   586.9    .035       0
#XS Ineff= 2 , 0
                          919.54         1835.94
Permanent Ineff=
       F       F
Bank Sta=558.6,586.9
XS Rating Curve= 0 ,0
Exp/Cntr=0.3,0.1

Type RM Length L Ch R = 1 ,3492    ,346.1,350,349.3
XS GIS Cut Line= 3
     2085247.193      181092.776     2085215.461      181655.896
     2085197.587      182201.869
#Sta/Elev= 30
       0 1909.61   101.5 1931.57   127.8 1935.95   163.9 1938.54   200.1 1936.07
   223.1 1930.23   249.6 1918.91   275.7 1905.91   318.8 1877.63   324.9 1877.44
   344.7 1883.55   367.7  1887.6   384.1 1888.25   403.8 1885.98   419.8 1880.66
   451.8 1866.71   479.4 1852.67   492.9 1847.08   512.3 1836.35   528.7 1831.53
   548.4 1830.44   568.1 1829.05     578 1830.32   607.5  1830.3   627.2 1831.68
   719.5 1830.55  1014.5 1833.36  1078.7 1836.07  1103.2 1839.51  1110.3 1841.63
#Mann= 9 ,-1 , 0
       0      .1       0     310     .12       0     410      .1       0
     480     .12       0     510      .1       0   548.4    .045       0
     578      .1       0  614.01    .035       0 1104.01     .04       0
#XS Ineff= 2 , 0
                          798.76         1835.41
Permanent Ineff=
       F       F
Bank Sta=548.4,578
XS Rating Curve= 0 ,0
Exp/Cntr=0.3,0.1

Type RM Length L Ch R = 1 ,3142    ,460.6,450.3,437.6
XS GIS Cut Line= 3
      2084952.42       181058.35     2084883.039      181602.641
     2084821.546      182151.946
#Sta/Elev= 30
       0 1897.49    60.8 1878.13    80.6    1870   100.5 1860.35   113.7 1856.04
   123.6 1849.48   136.9 1845.68   186.5 1843.99   193.1 1842.94   212.9 1846.56
   242.7 1839.32   268.7 1837.15   298.1 1837.17   341.9 1835.17   411.4 1834.63
   520.5 1829.43   533.7 1827.66   553.6 1825.64     566 1827.72   583.3 1826.58
   592.7 1828.68   606.4 1829.53   682.3 1828.53   916.3 1831.44   986.1 1834.13
  1012.5 1838.54  1042.2  1839.9  1058.7 1845.14  1080.8    1852  1101.4 1856.56
#Mann= 6 ,-1 , 0
       0      .1       0     250    .035       0   533.7    .045       0
     566    .035       0  1048.7     .06       0  1058.7     .04       0
#XS Ineff= 2 , 0
                           725.7         1833.11
Permanent Ineff=
       F       F
Bank Sta=533.7,566
XS Rating Curve= 0 ,0
Exp/Cntr=0.3,0.1

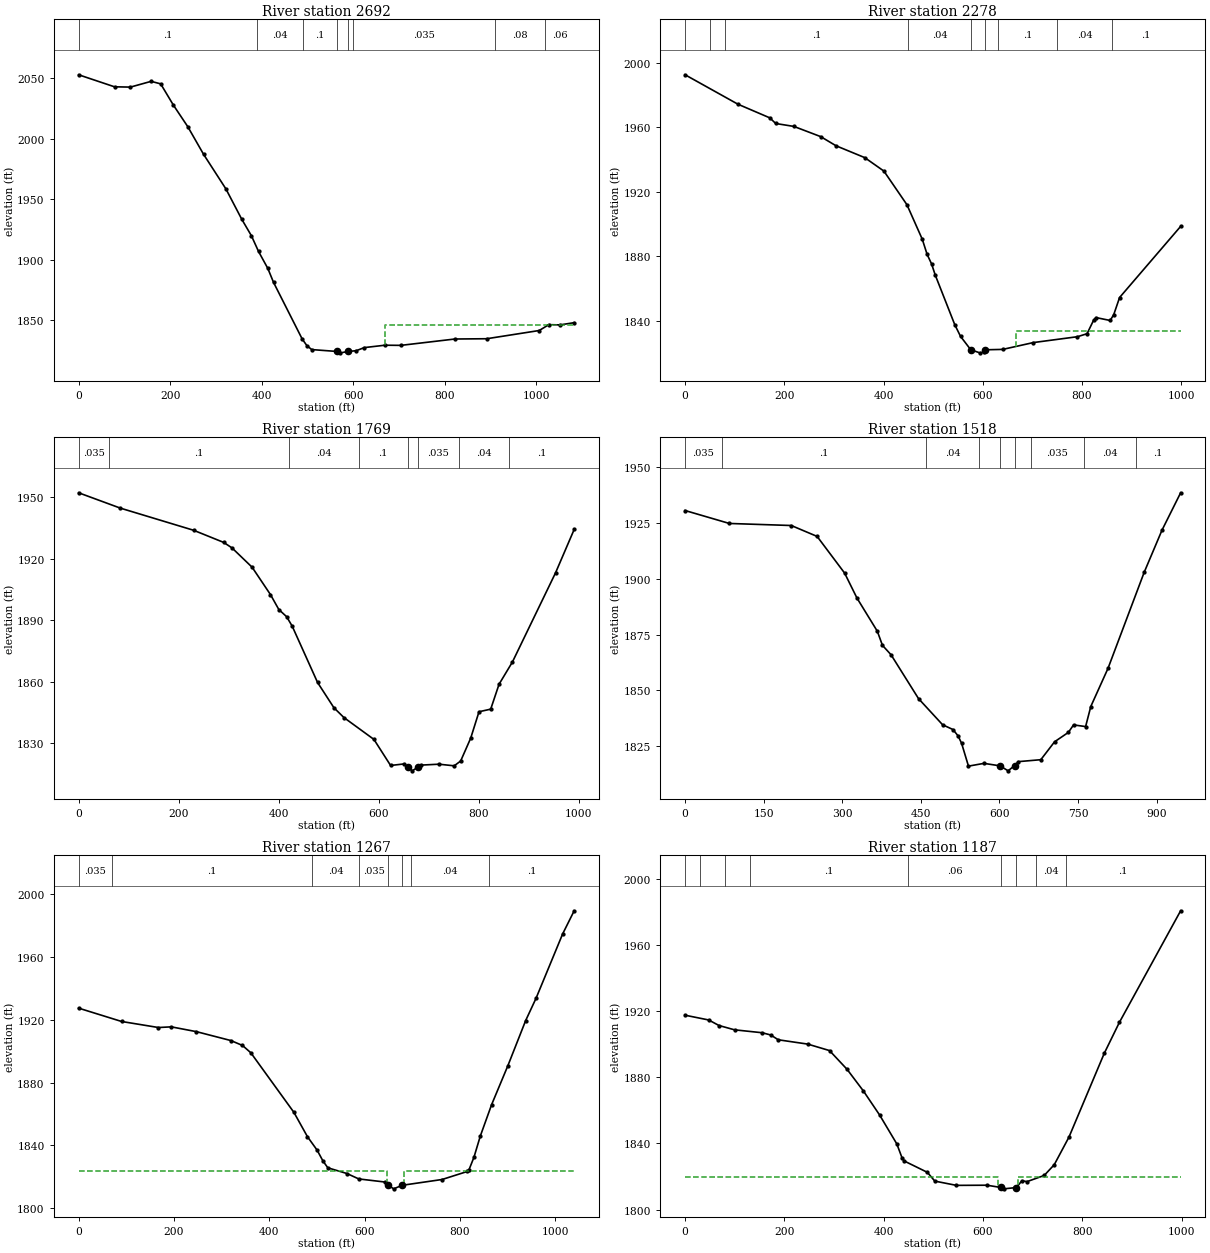
Type RM Length L Ch R = 1 ,2692    ,416.7,413.6,406.5
XS GIS Cut Line= 2
     2084271.468      181136.513     2084629.541      182158.648
#Sta/Elev= 30
       0 2052.66    78.4 2042.73   113.2 2042.48   158.4 2047.23   179.3 2045.16
     207 2027.66   238.5 2009.81   273.1 1986.94   321.8 1958.44   356.5 1933.33
   377.5 1919.78   393.2 1906.72   413.5 1892.69     426 1881.15   488.6 1834.39
     499 1828.87   509.5 1825.68   565.1 1824.12   572.1 1822.99   589.4  1824.1
   606.8 1824.77   624.2 1827.31   669.4 1829.29   704.2 1829.16   822.3 1834.41
   891.9 1834.64  1006.6 1841.43  1027.5 1846.25  1051.8 1846.07    1083 1847.91
#Mann= 8 ,-1 , 0
       0      .1       0     390     .04       0     490      .1       0
   565.1    .045       0   589.4      .1       0     600    .035       0
     910     .08       0    1020     .06       0
#XS Ineff= 2 , 0
                          668.77          1845.7
Permanent Ineff=
       F       F
Bank Sta=565.1,589.4
XS Rating Curve= 0 ,0
Exp/Cntr=0.3,0.1

Type RM Length L Ch R = 1 ,2278    ,501.7,509.3,516.5
XS GIS Cut Line= 2
     2083802.718      181362.207     2084330.061      182210.732
#Sta/Elev= 30
       0 1992.46   106.5 1974.22   170.8 1965.75   182.7 1962.26   219.3 1960.45
   273.4 1954.12   304.3 1948.45   362.2  1941.1   400.8 1932.76   447.2 1911.92
   478.1 1890.55     488 1881.06   496.9 1875.22   504.3 1868.31   543.7 1837.51
   555.3  1830.3   575.8 1822.05     594  1820.1   601.7 1820.47   605.6 1821.99
   640.3 1822.23   702.1 1826.47     791  1830.1   810.3 1831.95   823.6 1840.35
   828.3 1841.96   856.9 1840.16   864.1 1843.74   875.9 1854.39     999 1898.48
#Mann= 9 ,-1 , 0
       0      .1       0      50    .035       0      80      .1       0
     450     .04       0   575.8    .045       0   605.6     .04       0
     630      .1       0     750     .04       0     860      .1       0
#XS Ineff= 2 , 0
                          666.19         1833.51
Permanent Ineff=
       F       F
Bank Sta=575.8,605.6
XS Rating Curve= 0 ,0
Exp/Cntr=0.3,0.1

Type RM Length L Ch R = 1 ,1769    ,247.2,251,253
XS GIS Cut Line= 2
     2083570.513      181446.843     2083750.634      182421.235
#Sta/Elev= 30
       0 1952.24    83.3 1944.76     230 1933.94   290.2 1928.01   306.8 1925.32
   346.9 1915.92   383.6 1902.57   400.3 1895.29   415.9 1891.78     427  1887.2
   477.8 1859.68   510.4 1847.39   530.4 1842.59   590.5 1831.91   623.8  1819.2
   650.5 1819.94     658 1818.39   667.2 1816.58   677.7 1818.31   683.9 1819.37
   720.6 1819.82     751 1819.03   763.9 1821.37     784 1832.53   800.6 1845.41
     824 1846.68   840.7 1858.84   867.4 1869.67   953.7 1913.21   990.9 1934.35
#Mann= 8 ,-1 , 0
       0    .035       0      60      .1       0     420     .04       0
     560      .1       0     658    .045       0   677.7    .035       0
     760     .04       0     860      .1       0
Bank Sta=658,677.7
XS Rating Curve= 0 ,0
Exp/Cntr=0.3,0.1

Type RM Length L Ch R = 1 ,1518    ,258.2,251.5,243.4
XS GIS Cut Line= 4
2083429.31086257181532.8658950122083447.07383202182033.189534737
2083464.83680148182302.5945715132083479.63927603 182477.26377118
#Sta/Elev= 30
       0 1930.61    84.5 1924.81   202.7 1923.89     252    1919   304.5 1902.55
   328.1 1891.34   366.9 1876.49   376.7 1870.16   393.1 1865.93   445.6 1846.25
   491.6 1834.52   511.3  1832.4   521.2  1829.5   527.8 1826.21   540.9 1815.98
   570.5 1817.22   601.2 1816.11   616.6 1813.87   628.9 1816.24   636.3    1818
     679 1818.87   705.3 1826.91   731.6 1831.11   741.5 1834.47   764.5 1833.72
   774.4 1842.72   807.3 1859.85   876.4 1902.96   910.4 1921.85   945.9 1938.57
#Mann= 9 ,-1 , 0
       0    .035       0      70      .1       0     460     .04       0
  560.64      .1       0   601.2    .045       0   628.9      .1       0
  660.64    .035       0  760.64     .04       0  860.63      .1       0
Bank Sta=601.2,628.9
XS Rating Curve= 0 ,0
Exp/Cntr(USF)=0,0
Exp/Cntr=0.5,0.3

Type RM Length L Ch R = 1 ,1267    ,79.5,79.7,79.4
XS GIS Cut Line= 4
     2083376.347      181538.929     2083182.336      182093.616
     2083263.066      182301.949     2083207.076      182523.304
#Sta/Elev= 30
       0 1927.39    90.1 1918.89   167.4 1915.04   194.3 1915.47   247.2  1912.4
   319.4 1906.73   343.7 1903.61   361.1 1898.98   451.5 1861.01     480 1845.46
   500.2 1836.93   512.4 1830.05   522.7 1825.66   562.7 1822.03   587.6 1818.57
   643.1 1816.58   649.7 1814.55   660.8 1812.26   678.6 1814.52   762.3 1818.21
   815.6 1823.36   818.9 1824.51   829.1 1832.29   842.6 1845.96   866.3 1865.95
   900.2 1890.61   937.7  1919.5   959.5 1933.72  1015.2 1974.66  1039.4 1989.42
#Mann= 8 ,-1 , 0
       0    .035       0      70      .1       0     490     .04       0
  587.64    .035       0   649.7    .045       0   678.6    .035       0
  697.64     .04       0  861.07      .1       0
#XS Ineff= 2 , 0
          647.62 1823.32  683.04         1823.39
Permanent Ineff=
       F       F
Bank Sta=649.7,678.6
XS Rating Curve= 0 ,0
Exp/Cntr=0.5,0.3

Type RM Length L Ch R = 1 ,1187    ,234.8,253.5,275.8
XS GIS Cut Line= 4
     2083277.389      181575.821     2083096.399      182091.446
     2083177.128      182299.779     2083121.139      182521.133
#Sta/Elev= 30
       0 1917.53    47.5 1914.65    68.3  1911.3    99.6 1908.69   155.3 1906.93
   172.7 1905.55   187.6 1902.67     247 1900.06   290.9 1896.14   326.3 1884.79
   359.3 1871.65   391.7 1857.23   426.5 1839.68   436.9 1831.34   441.6 1829.33
     488  1822.5     503  1817.2   546.5 1814.62     608 1814.71   636.2 1813.34
   642.1 1812.52   667.5 1813.31   678.4 1817.41   688.9  1816.9   723.3  1820.6
   743.6 1827.11   773.3 1843.84   844.3 1894.45   874.8 1913.19   998.2 1980.69
#Mann= 9 ,-1 , 0
       0    .035       0      30      .1       0      80     .06       0
     130      .1       0     450     .06       0   636.2    .045       0
   667.5      .1       0  706.47     .04       0  766.47      .1       0
#XS Ineff= 2 , 0
          630.84 1819.92  671.58         1819.75
Permanent Ineff=
       F       F
Bank Sta=636.2,667.5
XS Rating Curve= 0 ,0
Exp/Cntr=0.5,0.3

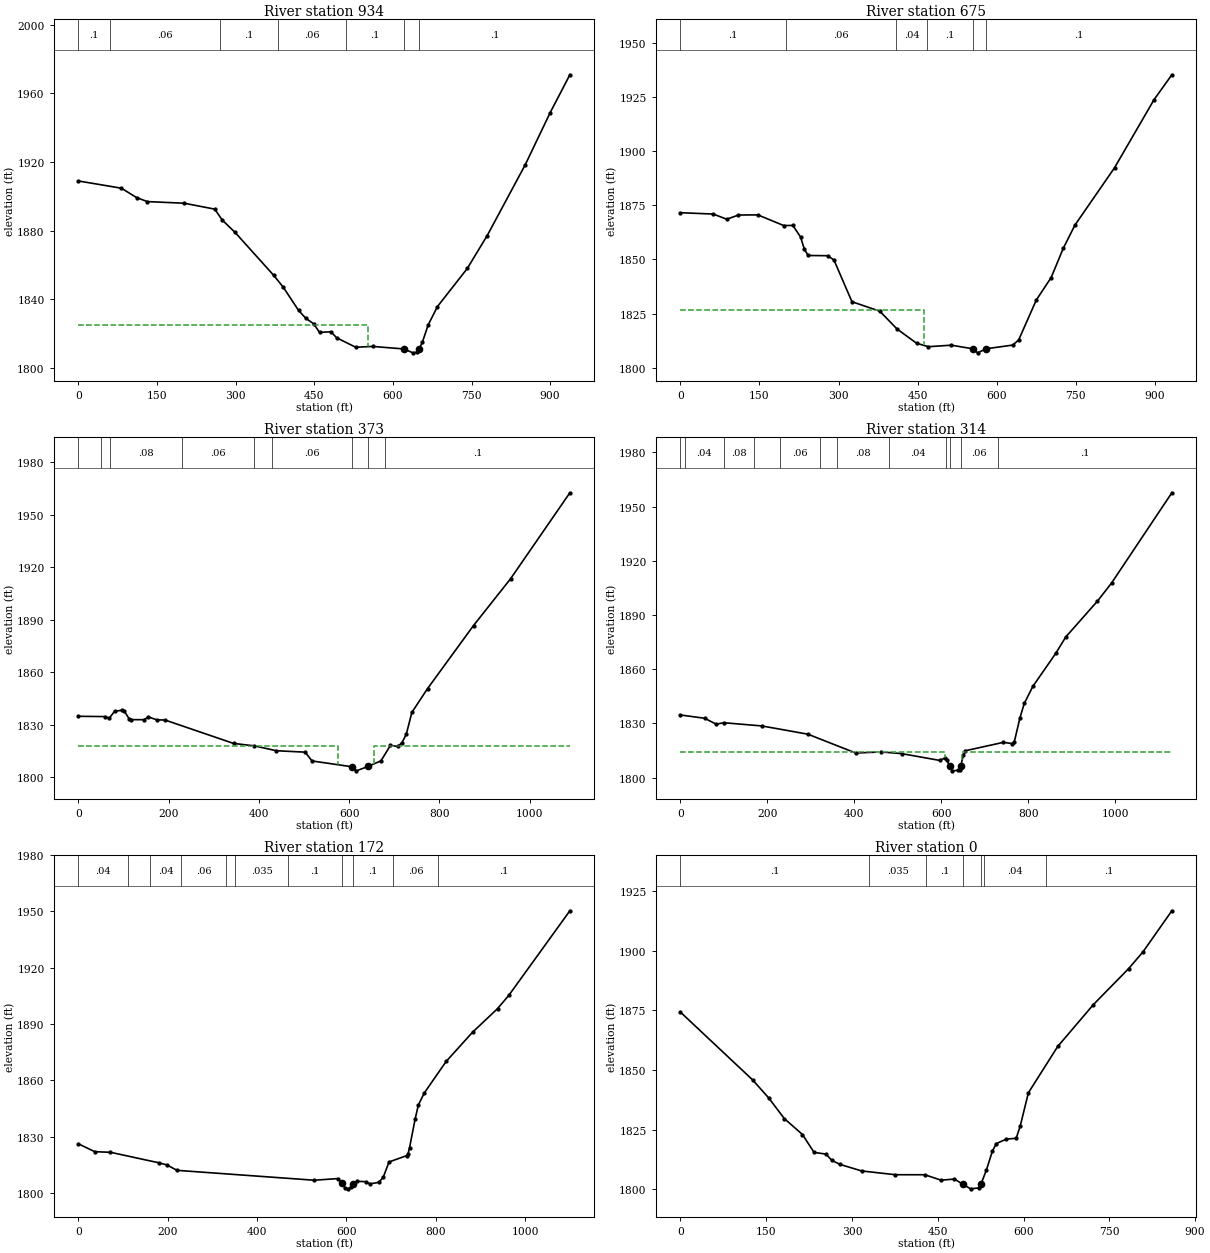
Type RM Length L Ch R = 1 ,934     ,257.5,259,260.1
XS GIS Cut Line= 2
     2083175.547      181553.179     2082771.902      182399.534
#Sta/Elev= 30
       0 1909.01      82  1904.8   111.1 1899.31   131.6    1897   201.9 1896.05
   260.1 1892.61   274.6 1886.21   298.9 1879.05   372.7 1854.03     391 1847.08
     420 1833.64   433.6 1829.14   449.1 1825.77     460 1820.84   481.8 1821.21
   492.7 1817.69   529.1  1812.2   561.8 1812.67   621.3 1811.19   638.1 1808.94
   645.4 1809.29  650.18 1811.24   656.3 1815.14   667.2 1825.13   685.1 1835.91
   741.9 1858.05   779.9 1877.18   852.4 1918.38   899.8 1948.62   937.7 1970.84
#Mann= 7 ,-1 , 0
       0      .1       0      60     .06       0     270      .1       0
     380     .06       0     510      .1       0   621.3    .045       0
  650.18      .1       0
#XS Ineff= 2 , 0
          553.01 1825.03
Permanent Ineff=
       F       F
Bank Sta=621.3,650.18
XS Rating Curve= 0 ,0
Exp/Cntr=0.3,0.1

Type RM Length L Ch R = 1 ,675     ,296.7,301.1,307.1
XS GIS Cut Line= 4
2082943.78969739181479.5769866392082742.47604353181879.243799437
2082612.21426751182122.0043820262082529.32041004182314.436551151
#Sta/Elev= 30
       0  1871.5    62.4 1870.88    88.1 1868.48   110.2 1870.44   146.9  1870.5
     196 1865.59   213.4 1865.62     228 1860.29   235.2 1854.68   242.4 1851.77
   279.2 1851.66   291.3 1849.73   325.5 1830.44   378.3 1826.07     411 1817.88
   448.1 1811.29   470.5 1809.69     514 1810.39  554.651808.738     564 1806.86
  580.131808.737   630.6 1810.44   641.8 1812.79   675.4 1831.26   703.5  1841.6
   726.4 1855.04   748.6 1865.79   823.7 1892.22   898.7 1923.64   932.5 1935.13
#Mann= 6 ,-1 , 0
       0      .1       0     200     .06       0     410     .04       0
  467.51      .1       0  554.65    .045       0  580.13      .1       0
#XS Ineff= 2 , 0
          461.32 1826.58
Permanent Ineff=
       F       F
Bank Sta=554.65,580.13
XS Rating Curve= 0 ,0
Exp/Cntr(USF)=0,0
Exp/Cntr=0.5,0.3

Type RM Length L Ch R = 1 ,373     ,59.7,59.9,59.7
XS GIS Cut Line= 3
     2082802.909      181368.008     2082325.045      181968.269
     2082345.878      182289.883
#Sta/Elev= 30
       0 1834.85    58.7 1834.69    68.4 1833.76    80.1  1837.7    96.5  1838.3
   101.7 1837.77   112.3 1833.51   117.4 1832.94   145.5 1832.91   155.1 1834.51
   173.5 1832.84   192.2 1832.71   343.9 1819.36     390 1817.98   438.9 1815.19
   502.7 1814.39   517.9 1809.36   605.4 1806.08   616.4 1803.72   641.6 1806.21
   670.7 1809.42   691.8 1818.29   707.5 1817.63   717.1  1819.7   726.9 1824.62
   739.1 1837.03   773.9 1850.64   875.9 1886.67   958.1 1913.39  1089.5 1962.43
#Mann= 9 ,-1 , 0
       0     .06       0      50      .1       0      70     .08       0
     230     .06       0     390     .08       0     430     .06       0
   605.4    .045       0   641.6     .06       0     680      .1       0
#XS Ineff= 2 , 0
          575.45 1817.82  655.68         1817.82
Permanent Ineff=
       F       F
Bank Sta=605.4,641.6
XS Rating Curve= 0 ,0
Exp/Cntr=0.5,0.3

Type RM Length L Ch R = 1 ,314     ,157.2,142.1,127.5
XS GIS Cut Line= 3
     2082761.243       181325.04     2082283.378        181925.3
     2082306.816      182287.279
#Sta/Elev= 30
       0 1834.72    55.9 1832.89    82.3 1829.61    99.7 1830.43   187.6 1828.64
     293 1824.09   403.2 1813.65   461.7 1814.27   508.9 1813.32   595.9 1809.59
   608.7 1810.89   613.4 1809.61  618.781806.271   625.2  1803.8   639.1  1804.1
     642 1804.49  644.331806.265   650.4  1812.3   655.4 1814.94   742.6 1819.56
   763.6 1818.87   767.7  1819.8   780.8  1833.2   790.7 1841.11   810.4 1850.56
     863  1868.8     886 1877.86   958.4 1897.58   991.3 1907.71    1130 1957.69
#Mann= 12 ,-1 , 0
       0     .06       0      10     .04       0     100     .08       0
     170     .04       0     230     .06       0     320     .04       0
     360     .08       0     480     .04       0     610     .06       0
  618.78    .045       0  644.33     .06       0     730      .1       0
#XS Ineff= 2 , 0
          608.66 1814.02  648.07         1814.02
Permanent Ineff=
       F       F
Bank Sta=618.78,644.33
XS Rating Curve= 0 ,0
Exp/Cntr=0.5,0.3

Type RM Length L Ch R = 1 ,172     ,172,171.5,156.2
XS GIS Cut Line= 3
2082644.35613199181405.3965040812082231.51691437 181711.98497741
     2082223.482      182297.696
#Sta/Elev= 30
       0 1826.14    36.7 1821.95    71.7 1821.63   179.4 1816.07   198.4 1814.86
   220.6 1812.01   527.9 1806.74   580.4 1807.62   590.2 1805.19   596.1 1802.75
   603.3 1802.15   609.9 1802.98     614 1804.73     623 1806.18   642.7 1805.97
   652.5  1804.8   672.2  1805.6   682.1 1808.25   695.2 1816.47   734.6 1819.84
   737.8 1820.88   741.1 1824.01   753.7 1839.45   760.8 1846.78   773.9 1853.17
   823.2 1870.11   882.2 1885.64     938 1898.19   963.3 1905.29    1100 1950.37
#Mann= 11 ,-1 , 0
       0     .04       0     110      .1       0     160     .04       0
     230     .06       0     330     .08       0     350    .035       0
     470      .1       0   590.2    .045       0     614      .1       0
  704.23     .06       0  804.23      .1       0
Bank Sta=590.2,614
XS Rating Curve= 0 ,0
Exp/Cntr=0.3,0.1

Type RM Length L Ch R = 1 ,0       ,0,0,0
XS GIS Cut Line= 2
     2081926.707      181392.712     2082202.748      182206.514
#Sta/Elev= 30
       01874.282 126.3371845.839 154.053 1838.38 181.7681829.626 213.4641822.947
 233.7351815.448 254.5221814.753 264.9151812.094 278.773 1810.45 316.8811807.682
 375.7771806.099  427.411806.084 455.8671803.797 479.1491804.286  494.081802.056
 507.4251800.178 521.2831800.546  525.431802.052 535.1411808.119 545.5341815.973
 552.4631819.147 569.6921821.019 587.1071821.379 594.0361826.334 608.4961840.449
 659.861 1859.89  722.22 1877.44 783.9031892.535 808.8311899.509 859.344 1916.75
#Mann= 7 ,-1 , 0
       0      .1       0     330    .035       0     430      .1       0
  494.08    .045       0  525.43      .1       0     530     .04       0
     640      .1       0
Bank Sta=494.08,525.43
XS Rating Curve= 0 ,0
Exp/Cntr(USF)=0,0
Exp/Cntr=0.3,0.1
LCMann Table=0

Chan Stop Cuts=-1
Use User Specified Reach Order=0
Composite Channel Slope=5